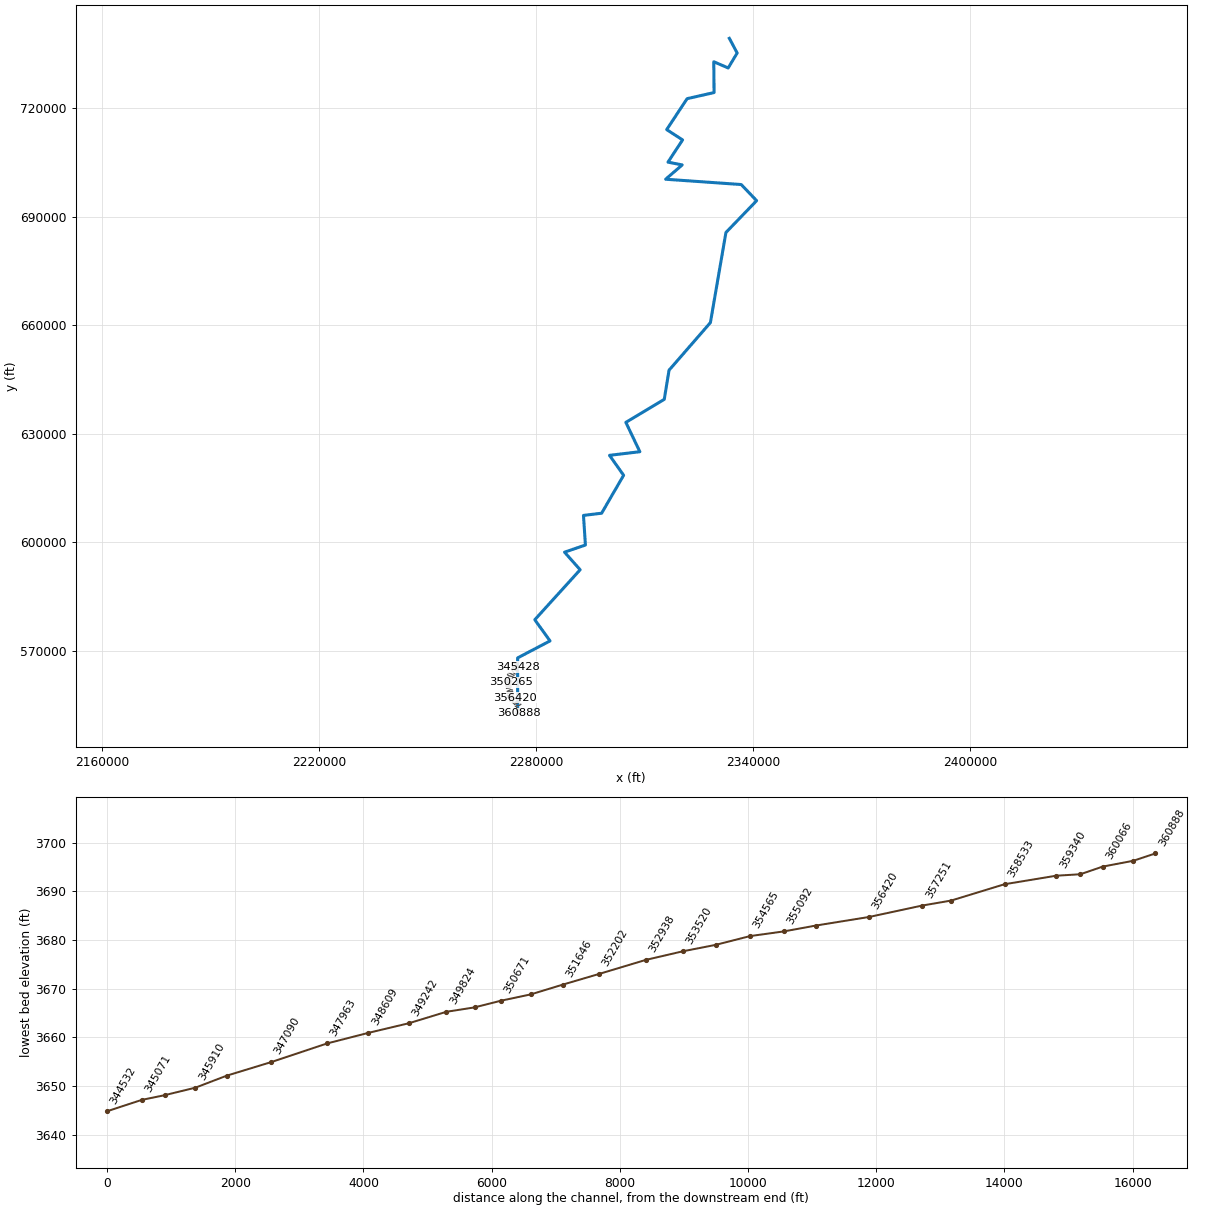
--- SHAVERSFK.prj (project) ---

Proj Title=SHAVERSFK
Current Plan=p01
Default Exp/Contr=0,0
English Units
Geom File=g01
Flow File=f01
Plan File=p01
BEGIN DESCRIPTION:
----------MODEL BY WOOD PLC 2022----------
AFH study
Randolph County, WV
HEC-RAS Version: RAS 6.2
Vertical Datum: NAVD88
Projection: NAD 1983 StatePlane West Virginia S FIPS 4702 (US Feet)
Terrain: 1-meter LIDAR (FEMA Region III 3DEP collected 2016-2018)
Land Use: 2019 NLCD
Hydrologic Method:
WV SIR2010-5033 regression equations
Additional Model Notes:
Model ties in to Pocahontas model at US extent
END DESCRIPTION:
DSS File=dss
DSS Export Rating Curves= 0
DSS Export Rating Curve Sorted= 0
DSS Export Volume Flow Curves= 0
DXF OffsetX= 0
DXF OffsetY= 0
DXF ScaleX= 0
DXF ScaleY= 0

--- SHAVERSFK.p01 (plan) ---

Plan Title=Floodplain
Program Version=6.20
Short Identifier=Floodplain
Geom File=g01
Flow File=f01
Subcritical Flow
K Sum by GR= 0
Std Step Tol= 0.01
Critical Tol= 0.01
Num of Std Step Trials= 20
Max Error Tol= 0.3
Flow Tol Ratio= 0.001
Split Flow NTrial= 30
Split Flow Tol= 0.02
Split Flow Ratio= 0.02
Log Output Level= 0
Friction Slope Method= 1
Unsteady Friction Slope Method= 2
Unsteady Bridges Friction Slope Method= 1
Parabolic Critical Depth
Global Vel Dist= 0 , 0 , 0
Global Log Level= 0
CheckData=True
Encroach Param=-1 ,0,0, 0
Computation Interval=0.1SEC
Output Interval=1SEC
Instantaneous Interval=Max Profile
Mapping Interval=1HOUR
Computation Time Step Use Courant=        0
Computation Time Step Use Time Series=    0
Computation Time Step Count To Double=0
Computation Time Step Max Doubling=0
Computation Time Step Max Halving=0
Computation Time Step Residence Courant=0
Run HTab= 0
Run UNet= 0
Run Sediment= 0
Run PostProcess= 0
Run WQNet= 0
Run RASMapper=-1
UNET Theta= 0
UNET Theta Warmup= 0
UNET ZTol= 0
UNET ZSATol= 0
UNET MxIter= 0
UNET Max Iter WO Improvement= 0
UNET MaxInSteps= 0
UNET DtIC= 0
UNET DtMin= 0
UNET MaxCRTS= 0
UNET WFStab= 0
UNET SFStab= 0
UNET WFX= 1
UNET SFX= 1
UNET Gravity=32.174
UNET 1D Methodology=Finite Difference
UNET DSS MLevel= 1
UNET Pardiso=0
UNET DZMax Abort= 0
UNET Use Existing IB Tables= 0
UNET Froude Reduction=False
UNET Froude Limit= 0
UNET Froude Power= 0
UNET D1 Cores= 0
UNET WindReference=Eulerian
UNET WindDragFormulation=Hsu (1988)
UNET D2 Coriolis=0
UNET D2 Cores= 0
UNET D2 Theta= 1
UNET D2 Theta Warmup= 1
UNET D2 Z Tol= 0.01
UNET D2 Volume Tol= 0.01
UNET D2 Max Iterations= 20
UNET D2 Equation= 0
UNET D2 RampUpFraction=0.1
UNET D2 TimeSlices= 1
UNET D2 Turbulence Formulation=Non-Conservative (original)
UNET D2 Eddy Viscosity=0.3
UNET D2 Transverse Eddy Viscosity=0.1
UNET D2 Smagorinsky Mixing=0
UNET D2 BCVolumeCheck=0
UNET D2 Cores=0
UNET D2 SolverType=PARDISO (Direct)
UNET D2 Minimum Iterations= 2147483647
UNET D2 Maximum Iterations= 2147483647
UNET D2 Restart Number= 10
UNET D2 Relaxation Coeff=1.3
UNET D2 SOR Precondition Iterations= 10
UNET D2 ILUT Maximum Fill= 8
UNET D2 ILUT Tolerance=1E-08
UNET D1D2 MaxIter= 0
UNET D1D2 ZTol=0.01
UNET D1D2 QTol=0.1
UNET D1D2 MinQTol=1
DSS File=dss
Write IC File= 0
Write IC File at Fixed DateTime=0
Write IC File at Sim End=0
Echo Input=False
Echo Parameters=False
Echo Output=False
Write Detailed= 0
HDF Write Warmup=0
HDF Write Time Slices=0
HDF Flush=0
HDF Compression= 1
HDF Chunk Size= 1
HDF Spatial Parts= 1
HDF Use Max Rows=0
HDF Fixed Rows= 1
Calibration Method= 0
Calibration Iterations= 20
Calibration Max Change=0.05
Calibration Tolerance=0.2
Calibration Maximum=1.5
Calibration Minimum=0.5
Calibration Optimization Method= 1
WQ AD Non Conservative
WQ ULTIMATE=-1
WQ Max Comp Step=1HOUR
WQ Output Interval=15MIN
WQ Output Selected Increments= 0
WQ Output face flow=0
WQ Output face velocity=0
WQ Output face area=0
WQ Output face dispersion=0
WQ Output cell volume=0
WQ Output cell surface area=0
WQ Output cell continuity=0
WQ Output cumulative cell continuity=0
WQ Output face conc=0
WQ Output face dconc_dx=0
WQ Output face courant=0
WQ Output face peclet=0
WQ Output face adv mass=0
WQ Output face disp mass=0
WQ Output cell mass=0
WQ Output cell source sink temp=0
WQ Output nsm pathways=0
WQ Output nsm derived pathways=0
WQ Create Restart=0
WQ Fixed Restart=0
WQ System Summary=0
WQ Write To DSS=0
Sorting and Armoring Iterations= 10
XS Update Threshold= 0.02
Bed Roughness Predictor= 0
Hydraulics Update Threshold= 0.02
Energy Slope Method= 1
Volume Change Method= 1
Sediment Retention Method= 0
Sediment TS Multiplier= 1
Warm Up Method= 0
XS Weighting Method= 0
Number of US Weighted Cross Sections= 1
Number of DS Weighted Cross Sections= 1
Upstream XS Weight=0
Main XS Weight=1
Downstream XS Weight=0
Number of DS XS's Weighted with US Boundary= 1
Upstream Boundary Weight= 1
Weight of XSs Associated with US Boundary= 0
Number of US XS's Weighted with DS Boundary= 1
Downstream Boundary Weight= 0.5
Weight of XSs Associated with DS Boundary= 0.5
Percentile Method= 0
Sediment Output Level= 3
Mass or Volume Output= 0
Output Increment Type= 1
Profile and TS Output Increment= 1
Transport Output Increment 1
XS Output Flag= 0
XS Output Increment= 10
Read HDF5 Sediment Hotstart= 0
Sediment Hotstart Type= 0
Write Gradation File= 0
Read Gradation Hotstart= 0
Write HDF5 File= 1
Write Binary Output= 1
Write DSS Sediment File= 0
DSS Sediment Output Type= 1
SV Curve= 0
Specific Gage Flag= 0
Subcell Erosion Methods= 0
Subcell Deposition Methods= 0
Advection Scheme= 1
Matrix Solver= 0
Implicit Weighting Factor= 1
Maximum Outer Loop Convergence Iterations= 5
Convergence Maximum Absolute= 0.001
Convergence RMSE= 0.0001
Grain Fractions Max Abs Error= 0.001
Max Subgrid Regions= 1
Max Subgrid Length Scale= 3.402823E+38
Initial Layer Thickness= 3.402823E+38
Min Layer Thickness= 3.402823E+38
Max Layer Thickness= 3.402823E+38
Number of Layers= 5

--- SHAVERSFK.f01 (steady flow) ---

Flow Title=Flow
Program Version=6.20
Number of Profiles= 1
Profile Names=P100yr
River Rch & RM=SHAVERSFK,Main            ,360888
    4610
River Rch & RM=SHAVERSFK,Main            ,347090
    5900
River Rch & RM=SHAVERSFK,Main            ,331980
    6990
River Rch & RM=SHAVERSFK,Main            ,331189
    7800
River Rch & RM=SHAVERSFK,Main            ,313478
    8670
River Rch & RM=SHAVERSFK,Main            ,302166
   10600
River Rch & RM=SHAVERSFK,Main            ,294619
   12300
River Rch & RM=SHAVERSFK,Main            ,280850
   13700
River Rch & RM=SHAVERSFK,Main            ,263253
   15700
River Rch & RM=SHAVERSFK,Main            ,240632
   17500
River Rch & RM=SHAVERSFK,Main            ,206553
   19500
River Rch & RM=SHAVERSFK,Main            ,174528
   21700
River Rch & RM=SHAVERSFK,Main            ,148548
   24200
River Rch & RM=SHAVERSFK,Main            ,118951
   26900
Boundary for River Rch & Prof#=SHAVERSFK,Main            , 1
Up Type= 0
Dn Type= 3
Dn Slope=0.0068
DSS Import GetInterval= 0
DSS Import GetPeak= 0
DSS Import FillOption= 0

--- SHAVERSFK.g01 (geometry) ---

Geom Title=Geometry
Program Version=6.20

River Reach=SHAVERSFK       ,Main
Reach XY= 30
2274910.00893386552636.7902783012274911.06400003567969.062000021
2283867.26000001572667.3760000172279652.59200001578521.039000019
2292192.01600003592343.7479999962287875.50900002597203.178000003
2293649.60900001599174.4500000032293116.40300001607371.819000006
2298130.43200001607974.5610000042304215.88699998618464.687999994
2300318.80200003623982.952999994     2308702.912624980.314999998
     2304832.043633099.3290000262315453.66100001639461.561000019
2316775.60800003 647523.314000012328210.21199998660674.996999994
2332507.17799999685599.5410000092340994.77000003694394.876000002
2336734.54099999698856.3419999932315840.25000004700326.158000007
2320411.19800001704280.7620000242316478.92699999705052.555000007
2320516.81800002711198.714000031     2316122.549714045.105000004
2321770.20600004722603.2080000042329223.46900001724288.100999996
2329143.70000003732809.2560000122333131.74100001731088.842999995
     2335612.015735224.0770000072333451.16799998739283.444999993

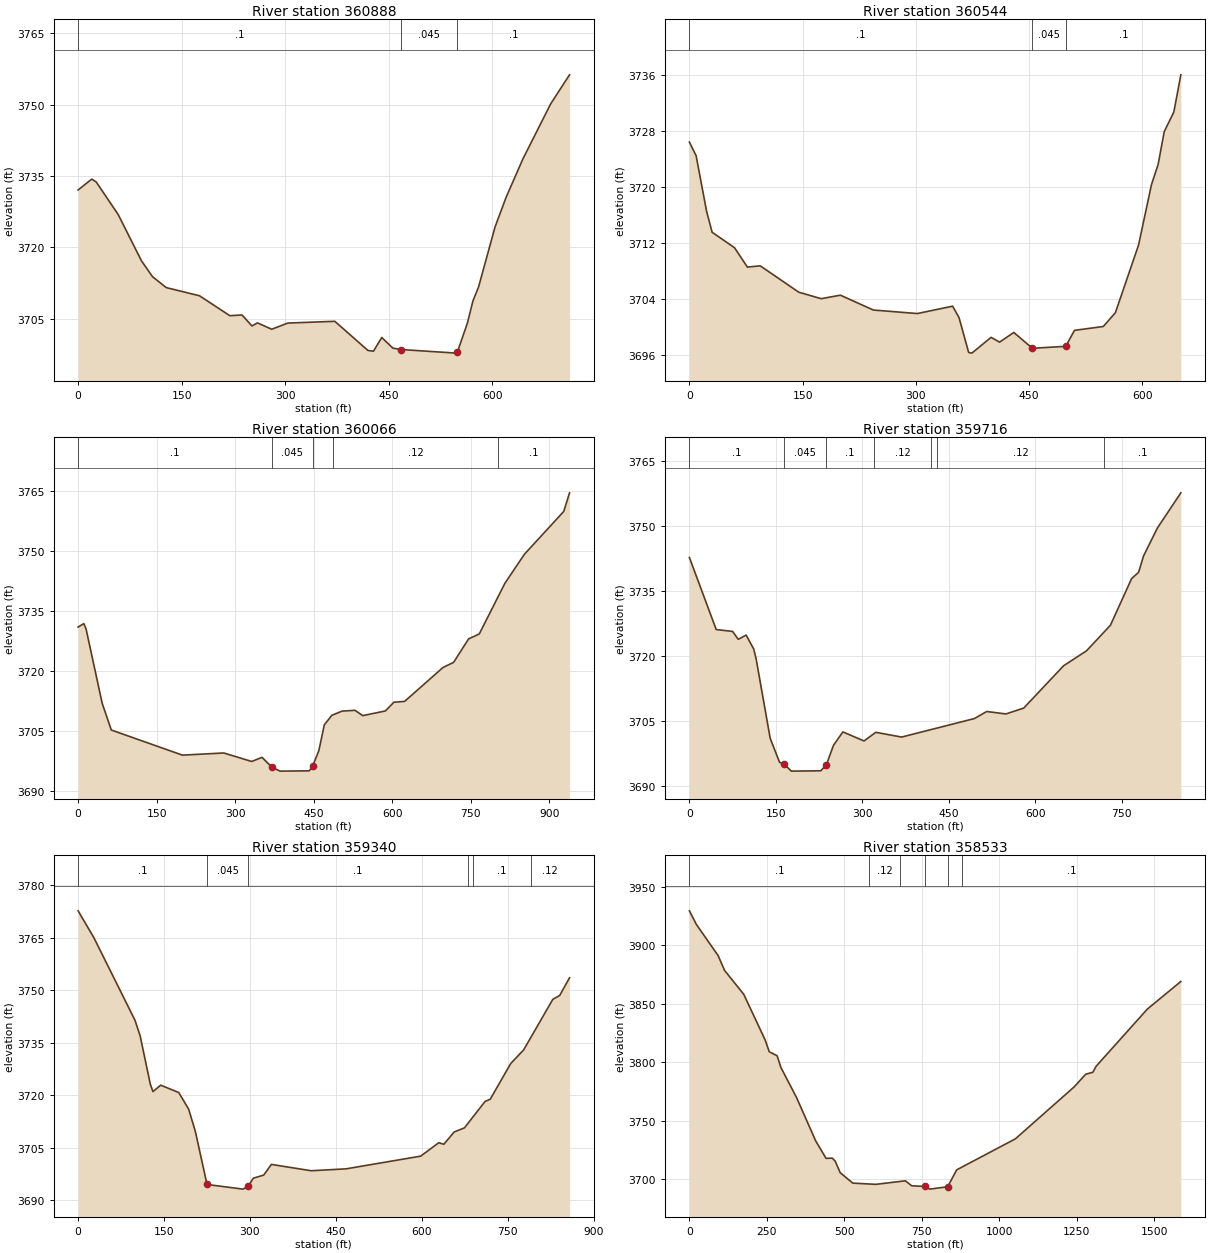
Type RM Length L Ch R = 1 ,360888  ,353.2,344.3,332.1
BEGIN DESCRIPTION:
Shared XS with Pocahontas model
END DESCRIPTION:
XS GIS Cut Line= 2
 2274412.4428885552648.2725716522275124.07890319552631.850202082
#Sta/Elev= 30
       0 3732.07    19.7 3734.35    26.2 3733.76      58 3726.92    91.8 3717.17
   107.8 3713.84   127.6 3711.55   175.8 3709.83   219.8 3705.64   237.4 3705.79
   251.8 3703.48   259.8 3704.13   280.4 3702.79   303.7 3704.09   371.8 3704.46
   419.8 3698.33   427.8 3698.18   439.8 3701.06   455.9 3698.82   467.5 3698.53
   547.9 3697.77   549.53698.058   563.9 3704.09   571.9 3708.76   579.9 3711.62
   603.9 3724.29   619.9 3730.52   643.9 3738.49   684.6 3750.21   711.8 3756.28
#Mann= 3 ,-1,0
       0      .1       0   467.5    .045       0   549.5      .1       0
Bank Sta=467.5,549.5
XS Rating Curve= 0 ,0
Exp/Cntr=0.3,0.1

Type RM Length L Ch R = 1 ,360544  ,445.6,478.4,500.2
BEGIN DESCRIPTION:
Shared XS with Pocahontas model
END DESCRIPTION:
XS GIS Cut Line= 2
2274543.82184506553129.9954123672275156.92364233 552911.03048477
#Sta/Elev= 30
       0 3726.38     8.9 3724.43    22.8 3716.48    30.1 3713.51    59.8  3711.3
    76.8 3708.54    93.8 3708.72   144.8 3704.96   174.5 3704.03     200 3704.53
   243.7 3702.41   301.9 3701.91   348.7 3702.96   357.2 3701.32   369.9 3696.36
   374.2 3696.26   399.6 3698.51   410.9 3697.83   429.7 3699.21   454.4 3696.95
   498.5 3697.23   510.1 3699.51   548.3 3700.06   564.3 3702.03     595 3711.69
     612 3720.27   620.9 3723.18     629 3727.87   641.7 3730.66     651 3735.98
#Mann= 3 ,-1,0
       0      .1       0   454.4    .045       0   498.5      .1       0
Bank Sta=454.4,498.5
XS Rating Curve= 0 ,0
Exp/Cntr=0.3,0.1

Type RM Length L Ch R = 1 ,360066  ,380.9,349.5,321.5
BEGIN DESCRIPTION:
Shared XS with Pocahontas model
END DESCRIPTION:
XS GIS Cut Line= 4
2274538.34772187553181.9995826722274727.20497192553266.848492116
2275031.01880896553485.8134197142275381.36269312 553417.38687984
#Sta/Elev= 30
       0 3731.01    10.8 3731.89    15.2 3730.55    45.9 3712.02    63.4 3705.32
   199.3 3699.05   278.2 3699.59   331.5 3697.47   351.2  3698.5   369.93696.051
   385.7 3695.06   441.5 3695.13     4483696.348   459.7 3700.15   470.2 3706.62
   484.5 3708.99   504.1 3710.03   528.7 3710.25   543.5 3708.91   586.8 3710.08
   603.1 3712.26   623.5 3712.46   696.8 3720.92   717.2 3722.22   745.7 3728.06
   766.1 3729.29     815 3741.93   852.4  3749.2   927.4 3759.87   938.5 3764.52
#Mann= 5 ,-1,0
       0      .1       0   369.9    .045       0     448      .1       0
  487.04     .12       0  801.54      .1       0
Bank Sta=369.9,448
XS Rating Curve= 0 ,0
Exp/Cntr=0.3,0.1

Type RM Length L Ch R = 1 ,359716  ,386,375.8,365.5
BEGIN DESCRIPTION:
Shared XS with Pocahontas model
END DESCRIPTION:
XS GIS Cut Line= 2
2274546.55890665553734.8860248562275384.09975471553573.399390753
#Sta/Elev= 30
       0 3742.79    46.5 3726.17      75 3725.73    84.8 3723.91    98.5 3724.89
   111.6 3721.67   115.7 3719.48   140.2 3701.08   156.4 3695.54   164.6 3695.11
   176.8 3693.49   228.2 3693.57   237.9 3695.01   250.1 3699.46   266.4 3702.54
   303.1 3700.45   323.5 3702.45   368.3 3701.35   494.6 3705.62   516.1 3707.25
   549.3 3706.69   580.3 3708.04   649.4  3717.8   689.3 3721.26   730.8 3727.16
   767.5 3737.91   779.7 3739.37   788.3 3743.16   812.3  3749.6     853 3757.72
#Mann= 7 ,-1,0
       0      .1       0   164.6    .045       0   237.9      .1       0
     320     .12       0     420      .1       0     430     .12       0
     720      .1       0
Bank Sta=164.6,237.9
XS Rating Curve= 0 ,0
Exp/Cntr=0.3,0.1

Type RM Length L Ch R = 1 ,359340  ,783.8,806.9,836.8
BEGIN DESCRIPTION:
Shared XS with Pocahontas model
END DESCRIPTION:
XS GIS Cut Line= 2
2274647.83018567554164.6046952672275411.47037066553773.204887186
#Sta/Elev= 30
       0 3772.67    27.4 3765.04    99.3 3741.42   108.3 3736.98   126.2 3723.08
   130.7 3721.05   144.2 3722.88   175.7 3720.78     193 3716.05   204.9 3709.54
   225.1 3694.52     288 3693.19   296.9 3693.98     306 3696.32     324 3697.19
   337.5 3700.25   406.9 3698.44   467.8 3698.98   598.2 3702.61   629.7 3706.44
   638.7 3706.01   656.6 3709.51   674.6 3710.69   710.6 3718.23   719.6 3718.86
   755.5 3729.08     778 3732.96   828.9 3747.39   840.9  3748.5   858.1 3753.55
#Mann= 6 ,-1,0
       0      .1       0   225.1    .045       0   296.9      .1       0
     680     .12       0     690      .1       0     790     .12       0
Bank Sta=225.1,296.9
XS Rating Curve= 0 ,0
Exp/Cntr=0.3,0.1

Type RM Length L Ch R = 1 ,358533  ,823.6,832.1,837.8
XS GIS Cut Line= 3
2274298.59386535554587.7344088012275420.74103552554885.103408897
2275774.21739413555120.754314634
#Sta/Elev= 30
       0 3929.35    22.3  3917.8    92.7 3891.04   113.4 3878.44   175.4 3857.95
   244.5 3818.89   257.6 3808.89     283 3805.44   295.4 3795.35     346 3769.56
   407.2 3732.84   440.8 3717.77     461 3717.93   470.3 3715.37   486.6 3705.48
   527.2 3696.57   601.7 3695.53   696.8 3698.55   717.5 3694.29   760.2 3693.75
   775.5 3691.44   833.3 3693.48   862.4  3707.9  1051.9 3734.44  1241.3  3778.8
  1278.8 3789.69  1301.9 3791.35  1312.4 3796.49  1477.8 3845.41  1585.7 3868.93
#Mann= 6 ,-1,0
       0      .1       0     580     .12       0     680      .1       0
   760.2    .045       0   833.3     .12       0     880      .1       0
Bank Sta=760.2,833.3
XS Rating Curve= 0 ,0
Exp/Cntr(USF)=0,0
Exp/Cntr=0.3,0.1

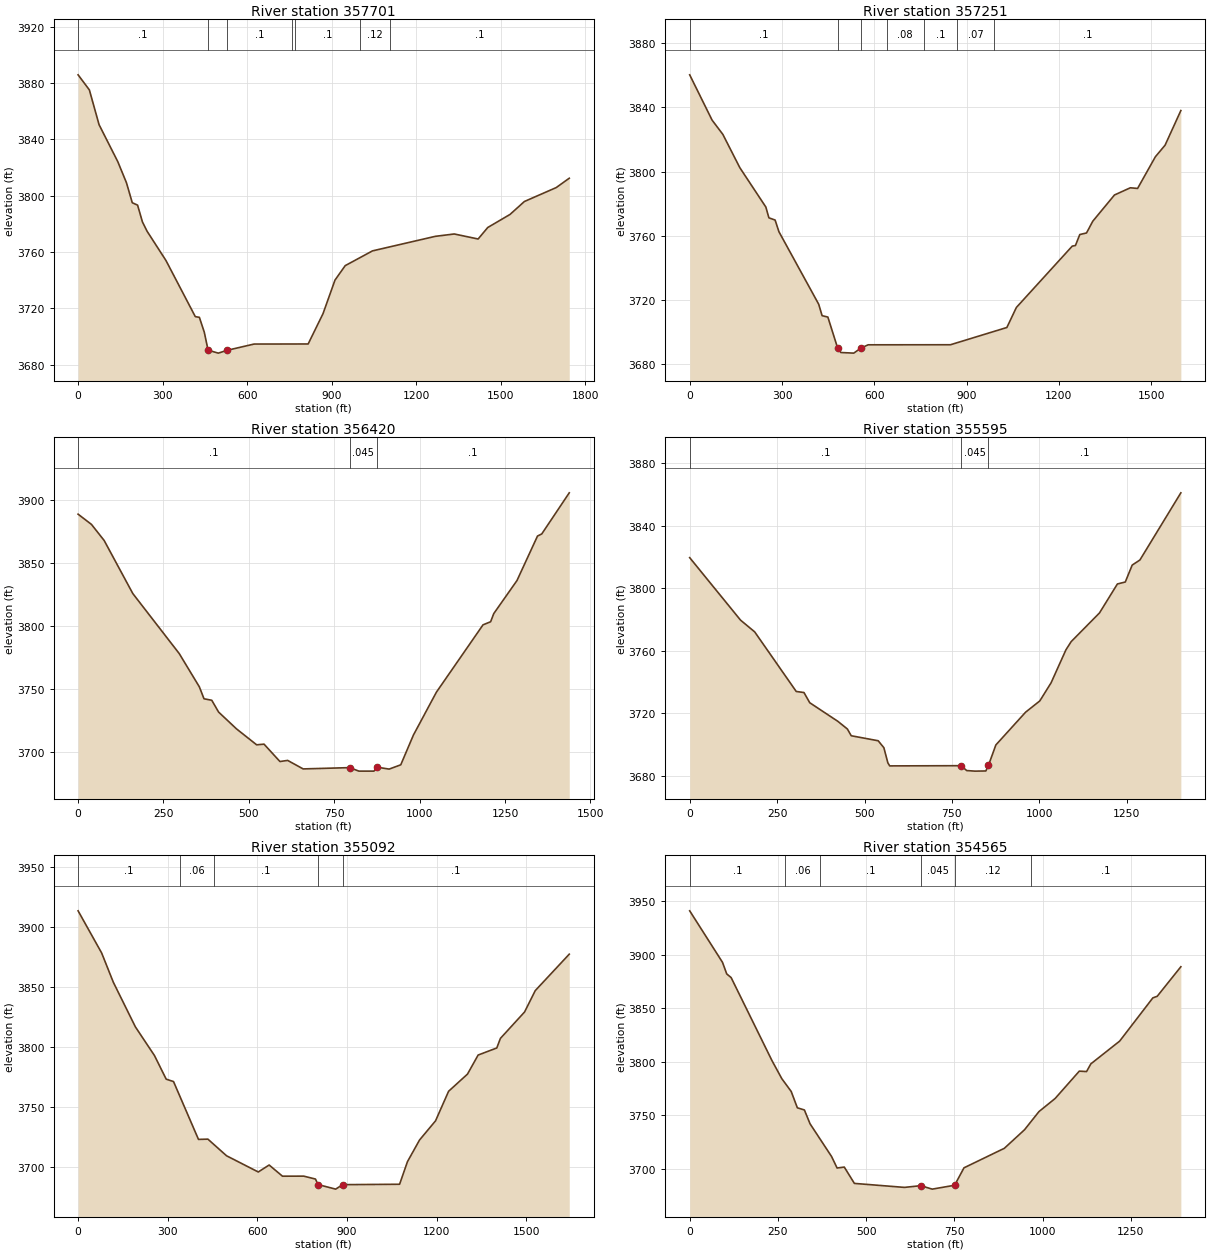
Type RM Length L Ch R = 1 ,357701  ,447.2,450.1,455
XS GIS Cut Line= 3
2274051.72148791555115.1435787832275033.60026181555558.391711002
2275504.90207329556029.693522476
#Sta/Elev= 30
       0 3885.84      40 3875.13    74.5  3850.4     141 3824.11   171.7 3809.16
   192.4 3794.95   211.2 3793.25   228.5 3781.29   244.8 3774.75   312.1 3753.85
   416.1 3714.03   430.6 3713.52   448.1 3702.91   461.5 3690.19   497.8 3688.09
     528 3690.04   624.8 3694.54   816.8 3694.59   869.5 3716.11     912 3739.96
   948.3 3750.25  1045.2 3760.74  1267.8 3771.06  1335.5 3772.75  1420.3 3769.19
  1454.4 3777.35  1533.5 3786.64  1584.5 3795.83  1697.5 3805.72  1743.8 3812.37
#Mann= 7 ,-1,0
       0      .1       0   461.5    .045       0     528      .1       0
     760     .08       0     770      .1       0    1000     .12       0
 1107.29      .1       0
Bank Sta=461.5,528
XS Rating Curve= 0 ,0
Exp/Cntr(USF)=0,0
Exp/Cntr=0.3,0.1

Type RM Length L Ch R = 1 ,357251  ,805.3,831.3,848.4
XS GIS Cut Line= 3
2273816.07058217555429.3447864322274769.89567682556007.250579072
2275022.37879011556416.834296186
#Sta/Elev= 30
       0 3860.26    72.8 3832.06   107.7 3823.22     163 3802.46   247.5 3777.99
   257.4 3771.28   277.6 3769.89   290.1  3762.6   419.3  3717.5   430.4 3710.37
   449.1 3709.51   480.5 3690.45   491.2 3687.45   533.3 3687.07   556.2 3690.17
   580.1 3692.25   847.5 3692.28  1030.9 3703.02  1061.8 3715.49  1243.3 3753.64
  1253.8 3754.06  1267.9 3760.87  1289.8 3761.85  1310.1 3769.15  1380.6 3785.47
  1432.2 3789.96  1455.8 3789.56  1513.6 3809.27  1545.1 3816.47  1596.4 3838.03
#Mann= 7 ,-1,0
       0      .1       0   480.5    .045       0   556.2      .1       0
     640     .08       0     760      .1       0     870     .07       0
     990      .1       0
Bank Sta=480.5,556.2
XS Rating Curve= 0 ,0
Exp/Cntr(USF)=0,0
Exp/Cntr=0.3,0.1

Type RM Length L Ch R = 1 ,356420  ,830.4,824.9,809.8
XS GIS Cut Line= 2
2273440.15128016555648.1634846162274119.05031812556916.189786914
#Sta/Elev= 30
       0 3888.39    39.2 3880.26    76.3 3867.54   160.3 3825.44   296.1 3777.92
   355.1 3751.52   368.7 3742.06   391.4 3740.89   411.5 3731.52   463.9  3718.2
   522.9 3705.57   544.5 3706.11     591 3692.34   613.7 3693.21     659 3686.47
   795.2 3687.49   822.3 3684.72   866.6 3684.73  874.853687.868   910.9 3686.33
   944.9 3689.73   981.9 3713.28  1049.3 3747.32  1185.8 3800.68  1208.1 3803.13
  1217.1 3809.53  1285.2 3835.78  1345.3 3871.03  1357.8 3872.74  1438.3 3905.31
#Mann= 3 ,-1,0
       0      .1       0   795.2    .045       0  874.85      .1       0
Bank Sta=795.2,874.85
XS Rating Curve= 0 ,0
Exp/Cntr(USF)=0,0
Exp/Cntr=0.3,0.1

Type RM Length L Ch R = 1 ,355595  ,513.9,502.8,484.3
XS GIS Cut Line= 3
2272811.74886487556052.1364658792272912.74211018556456.109447142
2273591.64114814557174.283636054
#Sta/Elev= 30
       0 3819.64   145.4 3779.65   185.9 3772.12   304.7 3733.97   326.8 3733.29
   343.3 3726.77   423.4  3714.9   450.9 3709.96     462 3705.62     539 3702.42
   555.3 3697.99   566.7  3688.3     572 3686.32   776.1 3686.45   792.2 3683.33
   815.7 3682.97   846.9 3683.07  854.353686.596   875.6 3699.73   960.8 3720.73
  1001.3 3727.92  1033.6 3739.53    1076 3760.62    1091 3765.88    1172 3784.25
  1223.2 3802.79  1245.8 3804.05  1265.5 3814.88  1287.6 3818.14  1404.7 3861.15
#Mann= 3 ,-1,0
       0      .1       0   776.1    .045       0  854.35      .1       0
Bank Sta=776.1,854.35
XS Rating Curve= 0 ,0
Exp/Cntr(USF)=0,0
Exp/Cntr=0.3,0.1

Type RM Length L Ch R = 1 ,355092  ,528.9,527,511.2
XS GIS Cut Line= 3
2272116.01761936557135.0084850982272447.05103456556899.357579361
2273557.97673303557443.598956896
#Sta/Elev= 30
       0  3913.8    78.8 3878.66     118 3854.19   191.7 3817.04   255.5 3793.15
   294.8 3773.44   319.3 3771.44   402.8 3723.22   434.3 3723.44   496.7 3709.57
   602.9 3696.05   639.2 3701.87   683.8 3692.55     755 3692.59   794.2 3690.17
  802.673685.577   861.9 3681.76   885.1 3685.48  1075.7 3685.82  1102.1 3704.69
  1142.5 3722.73    1196  3738.7  1239.7 3763.37  1302.9 3777.67  1338.5 3793.55
  1400.9 3799.45  1413.1 3807.46  1493.8 3829.43  1529.6 3847.26  1643.4 3877.66
#Mann= 5 ,-1,0
       0      .1       0     340     .06       0  456.34      .1       0
  802.67    .045       0   885.1      .1       0
Bank Sta=802.67,885.1
XS Rating Curve= 0 ,0
Exp/Cntr(USF)=0,0
Exp/Cntr=0.3,0.1

Type RM Length L Ch R = 1 ,354565  ,539.6,539.7,529.3
XS GIS Cut Line= 3
2272127.23909106557550.202938063 2272514.0819374557545.337020638
2273497.78130203557749.624019546
#Sta/Elev= 30
       0 3941.24    92.9 3893.08   104.9 3882.21   117.4 3878.77     233 3801.16
     261 3784.16   287.6 3772.21     305 3756.91     325 3754.88     341 3741.94
     402 3711.31   417.6 3700.57     438 3701.43   466.6 3686.16   608.4 3682.42
   654.6 3684.02   687.2  3680.8   750.7 3684.44   777.1 3700.73   891.5    3719
   948.7 3736.37   989.6 3753.37  1035.3 3765.59  1103.9 3791.22  1124.4 3790.83
  1136.6 3798.02  1218.3 3819.34  1312.3 3859.79  1324.6 3861.26  1391.6 3888.91
#Mann= 6 ,-1,0
       0      .1       0     270     .06       0     370      .1       0
   654.6    .045       0   750.7     .12       0  966.87      .1       0
Bank Sta=654.6,750.7
XS Rating Curve= 0 ,0
Exp/Cntr(USF)=0,0
Exp/Cntr=0.3,0.1

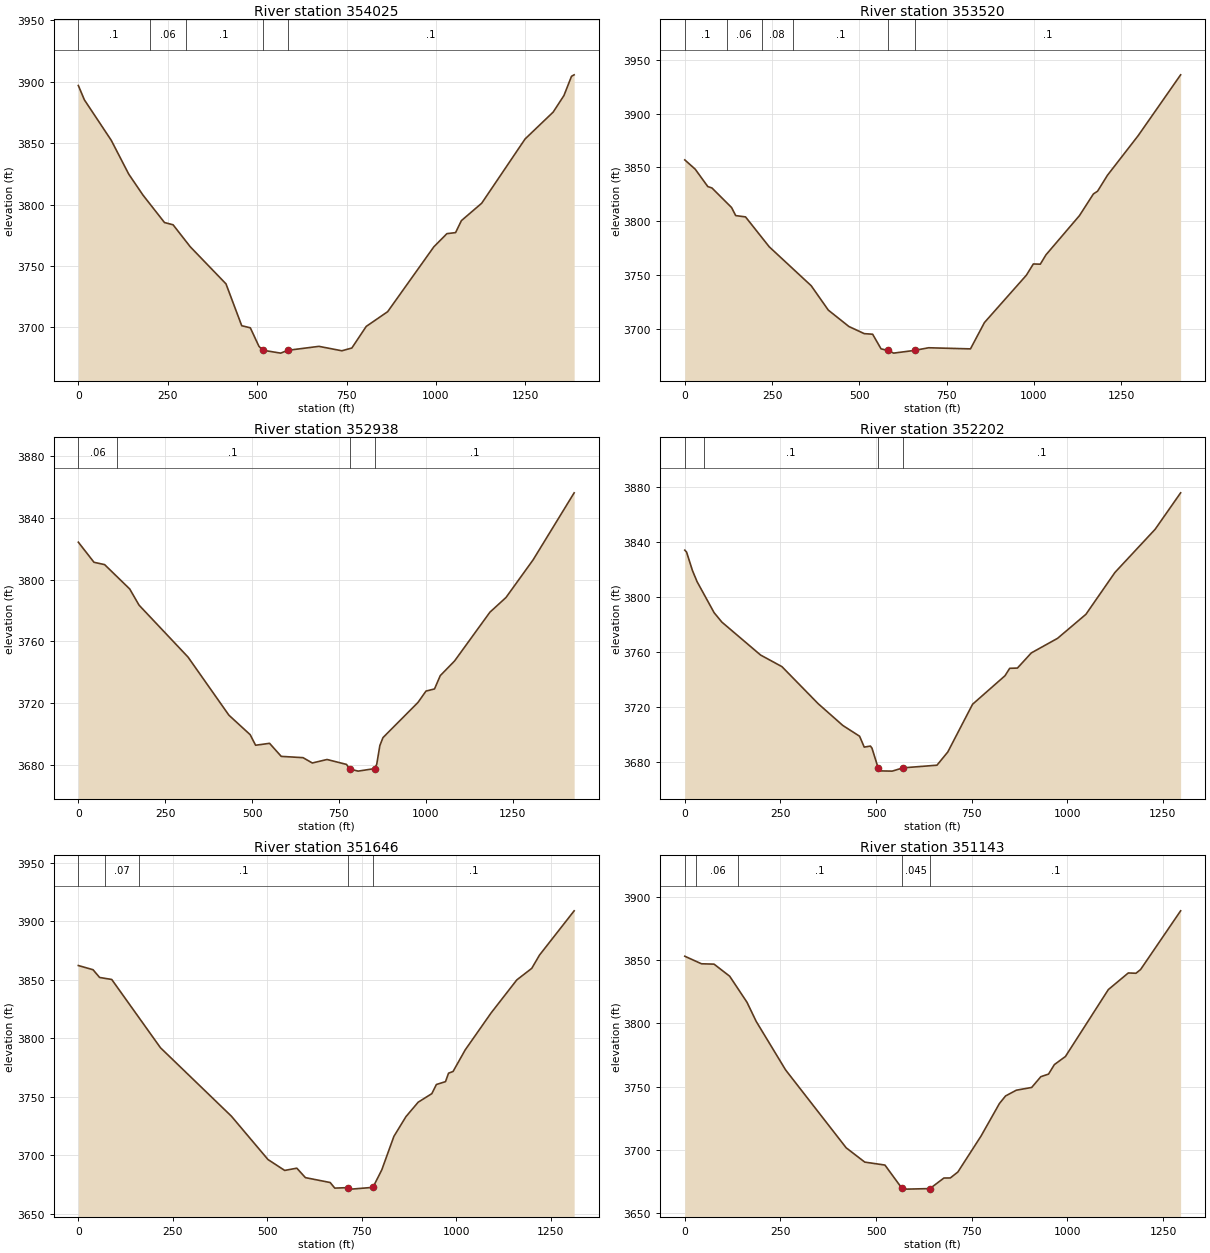
Type RM Length L Ch R = 1 ,354025  ,501.5,505.1,506.1
XS GIS Cut Line= 3
 2272099.1854118558111.2765231512272996.90314794558100.055051449
2273479.42643112558178.605353361
#Sta/Elev= 30
       0 3896.99      17 3885.27      92 3852.38     141 3824.79   180.8 3807.72
     241 3785.36     265 3783.53     313 3765.64     413  3735.4     457  3701.3
     481 3699.63     505 3684.61  515.653681.372     566 3678.99     585 3681.24
     673 3684.51     737  3680.9     765 3683.16   805.1 3700.73   865.1 3712.74
   994.3 3765.58  1030.8  3776.3  1055.1 3777.16  1071.3  3786.9  1128.2 3801.12
  1249.6 3853.48    1328 3875.32  1358.2 3888.85  1379.3 3904.48  1386.7 3905.68
#Mann= 5 ,-1,0
       0      .1       0     200     .06       0     300      .1       0
  515.65    .045       0     585      .1       0
Bank Sta=515.65,585
XS Rating Curve= 0 ,0
Exp/Cntr(USF)=0,0
Exp/Cntr=0.3,0.1

Type RM Length L Ch R = 1 ,353520  ,563,582.7,592.8
XS GIS Cut Line= 2
2272082.35320425558579.8639617912273501.86937452  558635.9713203
#Sta/Elev= 30
       0 3857.03    29.8 3848.43    65.9  3832.3    77.9 3830.95     134 3812.83
   145.9 3805.33     174 3804.13     242 3776.35   362.1 3740.26   411.2 3717.61
   470.2  3702.4   514.2 3695.77   538.2 3695.23   562.3 3681.66   582.3 3680.16
   598.3 3677.69   658.3 3680.21   698.4 3682.67   818.5 3681.63   858.5 3706.06
   978.6 3749.99   998.6 3760.43  1018.6 3760.25  1034.6 3768.84  1130.7 3805.29
  1170.7 3825.43  1182.7    3828  1210.8  3842.7  1298.8 3879.47  1420.6 3935.99
#Mann= 6 ,-1,0
       0      .1       0     120     .06       0     220     .08       0
     310      .1       0   582.3    .045       0   658.3      .1       0
Bank Sta=582.3,658.3
XS Rating Curve= 0 ,0
Exp/Cntr(USF)=0,0
Exp/Cntr=0.3,0.1

Type RM Length L Ch R = 1 ,352938  ,737.6,736,718.3
XS GIS Cut Line= 3
2272099.87074944558759.9857156722272979.18441937559199.642550639
2273411.26096408559097.308632155
#Sta/Elev= 30
       0 3824.42    45.1 3811.37    75.7 3809.86   147.9 3794.06   174.8 3783.57
   315.7  3749.9   433.4  3712.2   494.6 3699.55   510.2  3692.7   550.4 3693.95
     584 3685.48   646.7 3684.64   673.5 3681.19   715.9 3683.46   771.9 3680.26
   780.8 3677.32   805.3 3675.91   853.8 3677.58     859 3680.52   867.9 3692.54
   876.9 3697.66   977.6 3720.47  1000.6 3727.82  1025.2 3729.23  1041.7 3737.85
  1082.8 3747.34  1184.7 3779.02  1230.8 3788.51  1308.9 3812.94  1427.1 3856.43
#Mann= 4 ,-1,0
       0     .06       0     110      .1       0   780.8    .045       0
   853.8      .1       0
Bank Sta=780.8,853.8
XS Rating Curve= 0 ,0
Exp/Cntr(USF)=0,0
Exp/Cntr=0.3,0.1

Type RM Length L Ch R = 1 ,352202  ,555.4,555.4,550.9
XS GIS Cut Line= 3
2271852.31303437559575.6785802292272772.47371391559715.946976501
2273081.06418571559912.322731282
#Sta/Elev= 30
       0 3834.19     4.7 3832.73    20.1 3819.25    32.2 3811.16    76.7 3788.56
      97 3781.69   198.1  3757.7     254 3749.22   348.8 3722.19   413.4 3706.27
   457.1 3698.45   469.2 3690.53   485.4 3691.27   489.5 3689.75   505.6 3675.37
   513.7 3673.16   542.3    3673   570.9  3675.4   659.4 3677.32   687.7 3686.94
   752.5 3721.77   837.4  3742.6   849.6    3748   869.8 3748.17   906.2 3759.23
   974.9 3769.88    1049  3787.4  1124.8 3817.91  1229.9 3849.39  1296.6    3876
#Mann= 4 ,-1,0
       0     .06       0      50      .1       0   505.6    .045       0
   570.9      .1       0
Bank Sta=505.6,570.9
XS Rating Curve= 0 ,0
Exp/Cntr(USF)=0,0
Exp/Cntr=0.3,0.1

Type RM Length L Ch R = 1 ,351646  ,502.4,503.5,504.7
XS GIS Cut Line= 2
2271740.09831735560131.141429466 2273047.3997706560243.356146483
#Sta/Elev= 30
       0 3861.97    38.9 3858.38    56.3 3851.77    88.4 3850.05   217.4 3791.67
     405 3733.21   501.9 3696.14   546.1 3686.83   578.2 3688.76   600.9 3680.68
   666.5 3676.49   678.6 3671.72   714.7 3672.14   722.7 3670.85   779.6 3672.36
     803 3687.29   835.1 3715.96   867.1 3732.86   899.4 3745.16   935.5 3752.48
   947.5 3760.27   971.6 3762.71   979.7 3769.95   991.7 3771.43  1023.8 3789.86
  1092.1 3821.36  1160.3 3849.67  1199.9 3859.56  1220.5 3870.94  1312.1 3908.72
#Mann= 5 ,-1,0
       0      .1       0      70     .07       0     160      .1       0
   714.7    .045       0   779.6      .1       0
Bank Sta=714.7,779.6
XS Rating Curve= 0 ,0
Exp/Cntr(USF)=0,0
Exp/Cntr=0.3,0.1

Type RM Length L Ch R = 1 ,351143  ,488.3,471.5,448.6
XS GIS Cut Line= 4
2271669.54217025560539.4505264082271819.54240137 560572.00614272
2272410.66265002  560670.21886072272952.64614237560706.332849273
#Sta/Elev= 30
       0  3853.2    43.6 3847.23    76.4 3846.95   117.3 3837.39   162.6 3816.74
   186.6 3801.62   263.6 3763.14   421.8 3701.54   470.4 3690.22   523.1 3687.88
   567.7 3669.41   579.9 3668.83   640.7 3669.26   677.2 3677.62     694 3677.68
   713.7 3682.38   774.3 3710.87   822.4 3736.63   838.4 3742.61   866.5 3747.15
   906.6 3749.32   930.6 3757.85   950.7  3759.9   965.9 3767.41   994.8 3773.82
    1107 3826.81  1159.1 3839.96  1179.2 3839.73  1191.2 3842.66  1295.9 3889.15
#Mann= 5 ,-1,0
       0      .1       0      30     .06       0     140      .1       0
   567.7    .045       0   640.7      .1       0
Bank Sta=567.7,640.7
XS Rating Curve= 0 ,0
Exp/Cntr(USF)=0,0
Exp/Cntr=0.3,0.1

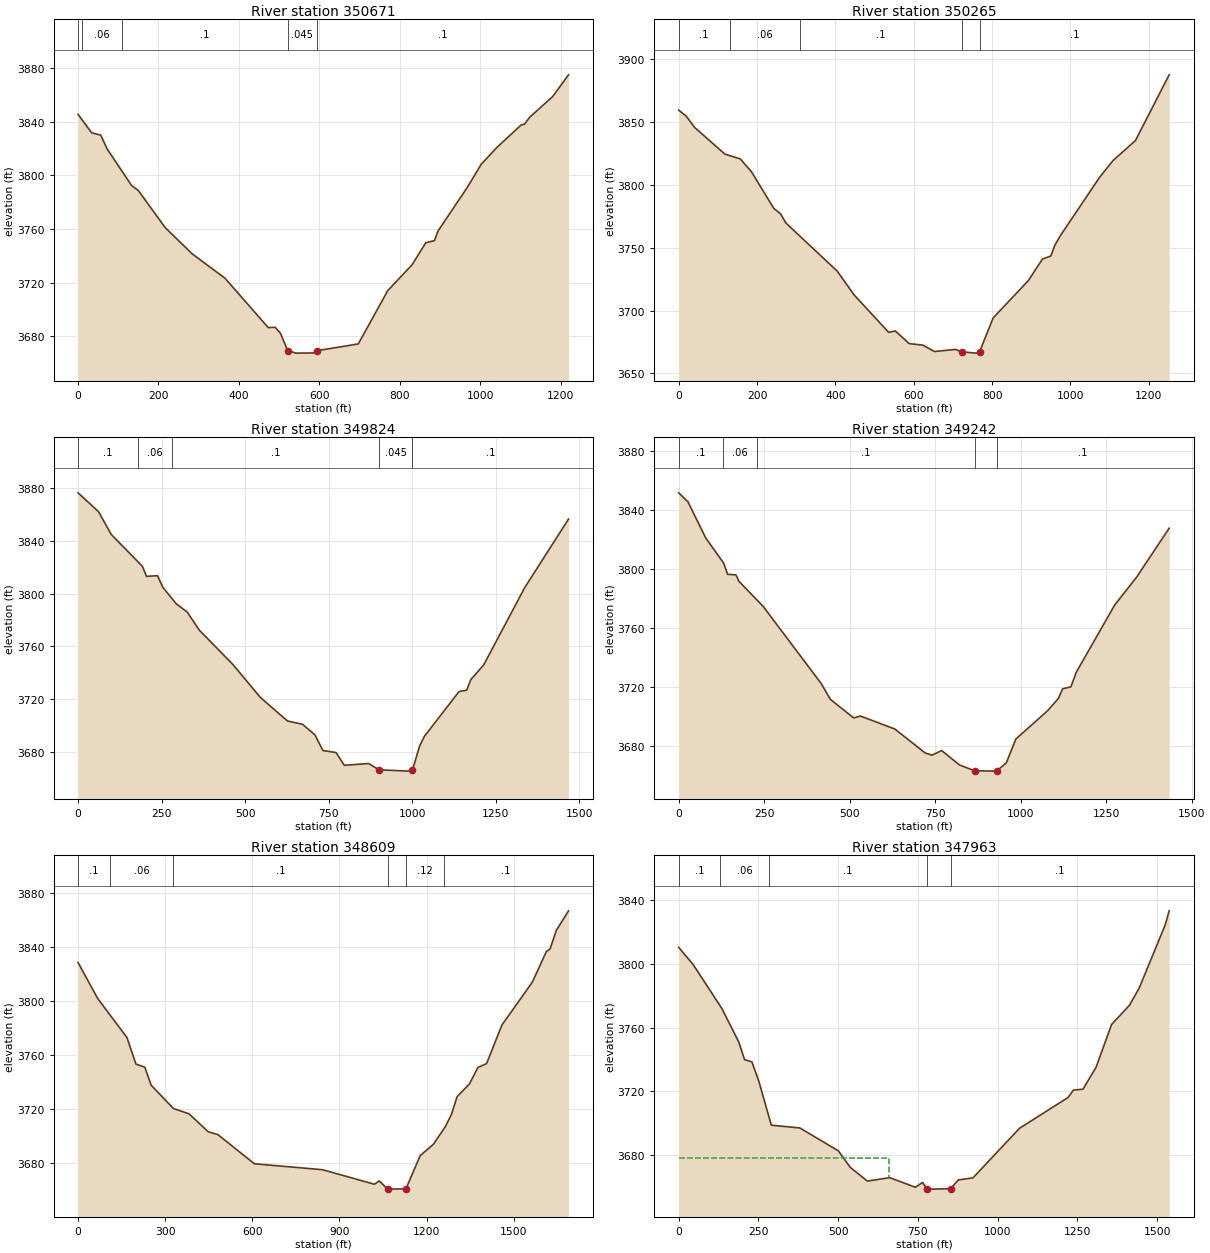
Type RM Length L Ch R = 1 ,350671  ,411.9,406.2,396.4
XS GIS Cut Line= 2
2271796.65913911561310.7533875062272929.91253269560859.726117152
#Sta/Elev= 30
       0 3845.55    33.9 3831.78    56.3 3830.04    72.7 3819.56   132.9 3792.58
   150.2 3788.65   216.4 3761.18   283.6 3741.59   365.4 3723.36     473 3686.51
   490.3 3686.78   503.2  3682.4   521.3 3669.36   541.9 3667.51     585 3667.62
   593.6  3669.3   696.9 3674.37   770.1 3714.09   830.4 3733.31   864.8 3749.82
   886.3 3751.41     895 3758.47   967.8 3790.99  1002.6 3808.33  1041.3 3820.81
  1101.6 3837.56  1110.2  3838.2  1123.1 3843.37  1180.3 3858.83  1219.7 3875.01
#Mann= 5 ,-1,0
       0      .1       0      10     .06       0     110      .1       0
   521.3    .045       0   593.6      .1       0
Bank Sta=521.3,593.6
XS Rating Curve= 0 ,0
Exp/Cntr(USF)=0,0
Exp/Cntr=0.3,0.1

Type RM Length L Ch R = 1 ,350265  ,445.5,441.3,437.8
XS GIS Cut Line= 2
2271918.26816491561676.9700068862273062.79386894561169.230617156
#Sta/Elev= 30
       0 3859.39    19.2 3854.67    40.7 3845.67   117.9 3824.47   157.3 3820.62
   185.9 3810.35   242.8 3781.26   260.3 3776.94   273.4 3769.76   404.7 3731.39
   448.4 3712.24     536 3682.71     553  3683.8   588.5 3673.74   623.5 3672.51
     653 3667.43   706.6 3669.13   722.7 3667.19   759.2 3666.16   768.2 3667.28
   802.9 3694.21   892.5  3723.8   928.8 3741.04   950.1 3743.42   960.4 3752.02
   973.5 3759.16  1074.3  3805.9  1109.2 3819.47  1166.1 3835.24  1252.1  3887.5
#Mann= 5 ,-1,0
       0      .1       0     130     .06       0     310      .1       0
   722.7    .045       0   768.2      .1       0
Bank Sta=722.7,768.2
XS Rating Curve= 0 ,0
Exp/Cntr(USF)=0,0
Exp/Cntr=0.3,0.1

Type RM Length L Ch R = 1 ,349824  ,552,581.6,611.5
XS GIS Cut Line= 3
2271918.26816491562013.6141579382272580.33499531561901.399440921
2273260.54332339 561487.66886099
#Sta/Elev= 30
       0 3876.45      61 3862.22    99.5 3844.82   192.6 3820.66   204.8 3813.06
   237.9 3813.57   253.5 3804.82     294  3792.2   326.5 3786.02     363 3772.19
   463.4 3746.18   545.6 3721.15   626.7 3703.31   671.6 3700.81   708.8 3692.78
   732.7 3680.88     772 3679.36   796.7 3669.68   869.5 3671.02   900.7 3666.26
   989.7 3665.25  1000.5 3665.93  1022.5 3684.61  1036.5 3691.69  1140.2 3725.67
  1162.9 3726.67  1175.2 3734.63  1214.4 3746.07  1336.1 3804.31  1467.7 3856.51
#Mann= 5 ,-1,0
       0      .1       0     180     .06       0     280      .1       0
   900.7    .045       0  1000.5      .1       0
Bank Sta=900.7,1000.5
XS Rating Curve= 0 ,0
Exp/Cntr(USF)=0,0
Exp/Cntr=0.3,0.1

Type RM Length L Ch R = 1 ,349242  ,640.5,632.9,616
XS GIS Cut Line= 4
2271973.05335139562249.2908274942272482.26792271562270.062882601
2273123.06160435562334.6648145562273403.23959995562348.768672137
#Sta/Elev= 30
       0 3851.59    27.1  3845.5    79.2 3820.93   131.2 3804.06   143.2 3796.31
   167.3 3795.98     176 3791.66   247.3 3774.51   416.6 3722.32   443.5  3711.6
   511.6 3698.99   531.7 3700.23   632.2 3691.45   720.6 3675.26   740.7 3673.72
   768.9 3676.87   821.1 3667.09   865.3 3663.15   921.6 3662.91   929.7 3663.08
   957.8 3668.39   985.9 3684.67  1078.4 3703.78  1110.6  3712.3  1122.6 3718.72
  1146.8 3720.03  1162.8 3730.03  1274.9 3775.51    1339 3794.43  1434.2  3827.6
#Mann= 5 ,-1,0
       0      .1       0     130     .06       0     230      .1       0
   865.3    .045       0   929.7      .1       0
Bank Sta=865.3,929.7
XS Rating Curve= 0 ,0
Exp/Cntr(USF)=0,0
Exp/Cntr=0.3,0.1

Type RM Length L Ch R = 1 ,348609  ,651.3,646.7,637.6
XS GIS Cut Line= 4
2272151.15878941 563399.221156822272284.33969488563099.220694579
2273299.88288389562824.2946378862273569.09514945562674.268642946
#Sta/Elev= 30
       0 3828.76    67.9 3802.03   168.5 3773.18   199.2 3753.56   229.8 3751.26
   251.7  3737.9   328.2 3720.68     382 3716.71   448.2 3703.43   481.4 3701.33
     607  3679.7   841.9 3675.31  1020.1 3664.55  1036.7 3667.04  1065.7 3660.93
  1128.7 3661.14    1178 3685.79  1223.2 3694.11  1264.6 3707.33  1285.3 3716.19
  1304.8 3729.39  1347.5 3738.89  1376.5 3751.05  1406.4 3753.92  1459.3 3782.52
  1563.8 3814.23  1612.2 3836.87    1625 3838.87  1646.3  3852.5  1688.5 3867.08
#Mann= 6 ,-1,0
       0      .1       0     110     .06       0  328.23      .1       0
  1065.7    .045       0  1128.7     .12       0 1258.23      .1       0
Bank Sta=1065.7,1128.7
XS Rating Curve= 0 ,0
Exp/Cntr(USF)=0,0
Exp/Cntr=0.3,0.1

Type RM Length L Ch R = 1 ,347963  ,873.9,872.2,838.5
XS GIS Cut Line= 4
2272521.57041084563836.9358446462272766.86297806 563744.45531743
 2273653.3592425 563301.207185212273869.25019461563116.143075499
#Sta/Elev= 30
       0 3810.25    45.5 3799.45   135.3 3771.98   188.1  3751.1   206.7 3739.86
   229.4 3738.53   250.7 3726.74   290.4 3698.84   379.9 3697.08   500.6 3682.74
   537.8  3672.4   591.5 3663.79   661.6 3665.94   742.1 3659.91   764.5 3662.96
   777.9 3659.12   797.2 3658.75   852.9 3659.09   876.8 3664.52   922.4 3665.78
  1068.6 3696.89  1220.7 3716.18  1237.5 3720.83  1267.5 3721.37  1308.6 3735.18
  1357.1 3761.92  1413.1 3773.95  1443.9 3784.84  1525.7 3824.58  1537.6 3833.16
#Mann= 5 ,-1,0
       0      .1       0     130     .06       0  282.15      .1       0
   777.9    .045       0   852.9      .1       0
#XS Ineff= 2 , 0
          659.64 3678.28
Permanent Ineff=
       F       F
Bank Sta=777.9,852.9
XS Rating Curve= 0 ,0
Exp/Cntr(USF)=0,0
Exp/Cntr=0.3,0.1

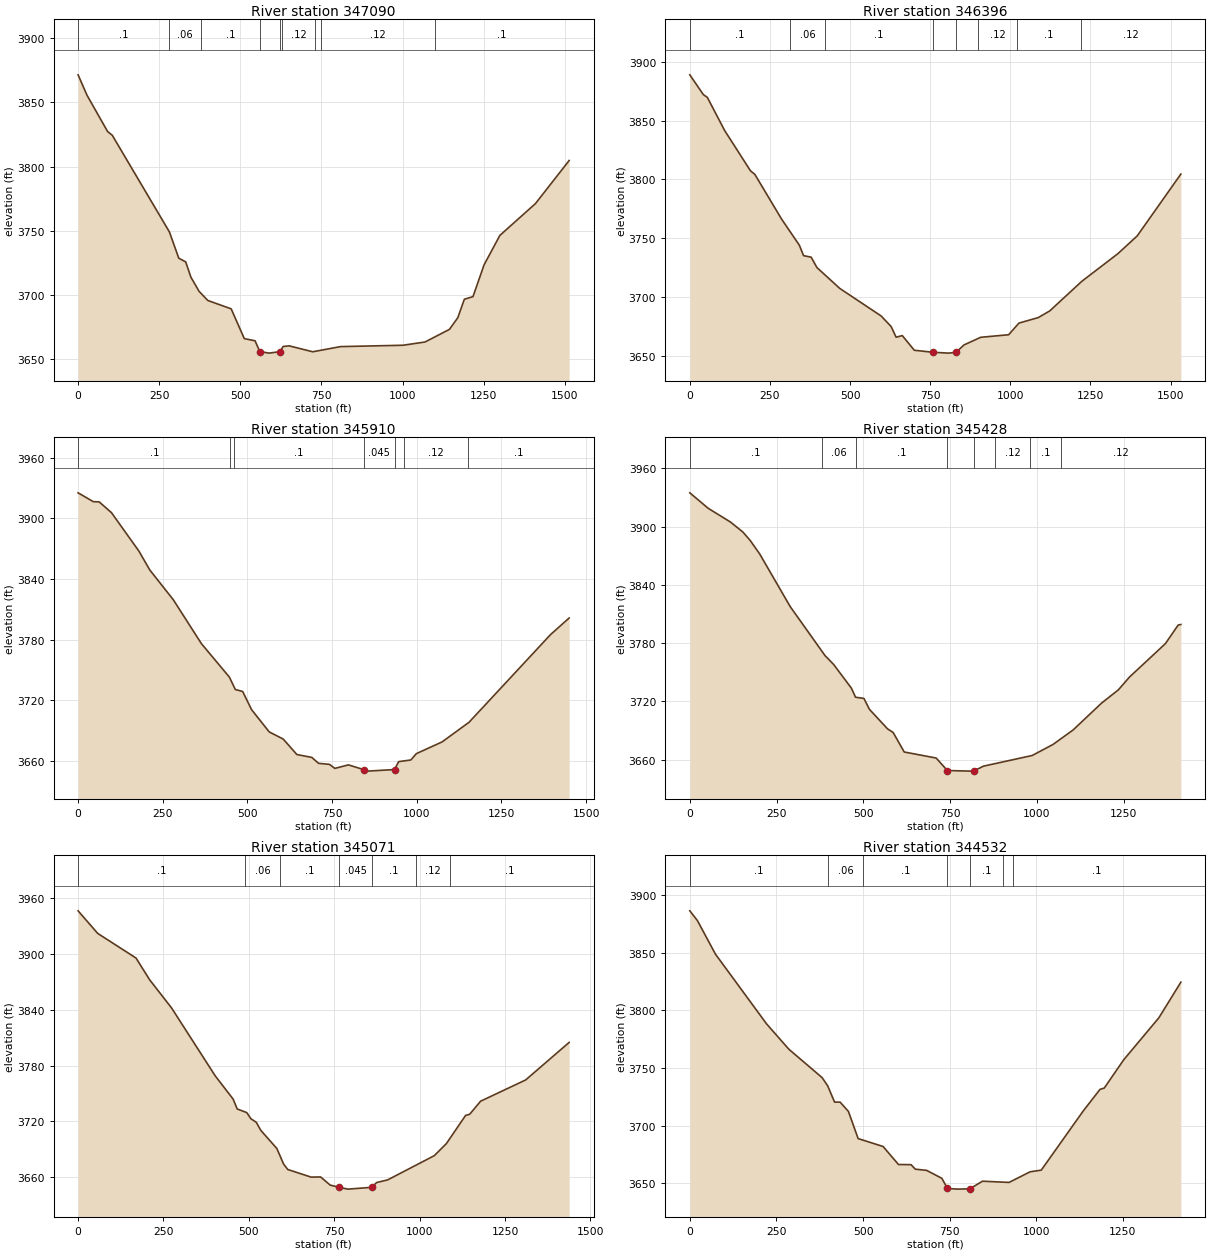
Type RM Length L Ch R = 1 ,347090  ,685.1,694.6,706.3
XS GIS Cut Line= 3
2273268.91434048564707.9736011982273935.19244325563702.316829955
2274190.38431014563531.247355096
#Sta/Elev= 30
       0 3871.29    27.6 3855.38      91 3827.19   105.4 3824.29   281.4 3749.19
   310.4 3728.73   331.8 3725.84   347.8 3713.93   372.8 3703.01   399.8 3695.87
   471.9 3689.34   512.3 3666.21   545.6  3664.5   559.9 3656.17   588.7 3654.92
   622.3  3656.1   631.9 3660.08   650.9 3660.57   723.1 3655.97   809.5    3660
  1001.4 3661.04  1069.3 3663.57  1144.4 3673.34  1170.4 3682.43  1190.6 3696.82
  1217.2 3698.84  1251.5 3723.61  1300.1 3746.44  1409.8 3771.19  1513.6 3804.66
#Mann= 9 ,-1,0
       0      .1       0     280     .06       0     380      .1       0
   559.9    .045       0   622.3      .1       0     630     .12       0
     730      .1       0     750     .12       0    1100      .1       0
Bank Sta=559.9,622.3
XS Rating Curve= 0 ,0
Exp/Cntr(USF)=0,0
Exp/Cntr=0.3,0.1

Type RM Length L Ch R = 1 ,346396  ,464.5,485.2,517.1
XS GIS Cut Line= 5
2273491.55512037564965.5564771372273618.12695391 564900.54918027
2274061.98348012564677.1693258942274331.73771953564452.432929425
2274872.01641965564491.705266946
#Sta/Elev= 30
       0 3889.12    42.3 3872.26    54.7 3869.91   108.6 3841.73   189.4 3807.34
   202.8 3804.39   286.3 3766.28   341.6 3744.09     355 3735.13   378.7 3733.83
   396.5 3725.02     468  3707.2   596.9 3683.77   628.2 3674.73   643.6 3665.71
   662.9 3667.05   700.4 3654.57759.35423652.857   807.9 3652.13     831 3652.88
   855.5 3659.12   907.6 3665.62   994.7 3667.78  1026.8  3677.7    1087 3682.38
  1123.1 3688.11  1223.3 3713.36  1335.4 3736.79  1395.8 3751.95    1532  3804.6
#Mann= 8 ,-1,0
       0      .1       0  312.29     .06       0  422.29      .1       0
759.3542    .045       0     831      .1       0  899.19     .12       0
 1020.29      .1       0 1220.29     .12       0
Bank Sta=759.3542,831
XS Rating Curve= 0 ,0
Exp/Cntr(USF)=0,0
Exp/Cntr=0.3,0.1

Type RM Length L Ch R = 1 ,345910  ,483.6,482.9,486.5
XS GIS Cut Line= 4
2273553.71393302565253.7819070442274088.19771189565023.767500978
2274576.37037665564993.0050681212274955.06284181564977.598087872
#Sta/Elev= 30
       0  3925.3      45 3916.54    62.2 3916.35    98.5 3905.69   179.4 3867.69
   211.7 3848.93   281.4 3819.29   364.1 3775.97   446.8 3742.79   464.3 3730.52
     486 3728.55   512.2  3710.6   564.4 3688.51   605.9 3681.39     646 3666.12
   690.1 3663.28   710.1 3657.39   742.2 3656.39   758.2  3652.4   798.3 3655.86
   844.3 3651.09   854.4 3649.68   934.6 3651.25   946.6 3659.09   982.6 3660.73
   998.7 3666.97  1074.8 3678.61  1154.5 3698.08  1395.1  3784.9    1450 3801.33
#Mann= 7 ,-1,0
       0      .1       0     450     .06       0     460      .1       0
   844.3    .045       0   934.6      .1       0  961.88     .12       0
 1151.02      .1       0
Bank Sta=844.3,934.6
XS Rating Curve= 0 ,0
Exp/Cntr(USF)=0,0
Exp/Cntr=0.3,0.1

Type RM Length L Ch R = 1 ,345428  ,352.9,357.1,361.9
XS GIS Cut Line= 2
2273587.36546622565527.2698545232274999.93584671565455.729751947
#Sta/Elev= 30
       0 3934.77    52.9 3918.84     117 3904.72     153 3894.35   174.3 3885.53
   201.2 3871.87   289.2 3817.57   389.3  3767.2   414.5  3757.9   465.4 3733.58
   477.4 3724.22   501.5 3723.03   517.4 3711.79   569.5 3691.68   585.6 3687.96
   617.6 3667.84   709.7 3661.59   741.8 3648.75   808.7 3648.13   817.9 3648.28
   845.9 3653.25   986.1 3664.22  1046.1  3675.6    1104 3690.52  1186.3 3718.27
  1234.1 3731.74  1266.4 3745.02  1369.8 3779.41  1406.6 3798.56  1414.4 3799.17
#Mann= 8 ,-1,0
       0      .1       0     380     .06       0     480      .1       0
   741.8    .045       0   817.9      .1       0     880     .12       0
     980      .1       0    1070     .12       0
Bank Sta=741.8,817.9
XS Rating Curve= 0 ,0
Exp/Cntr(USF)=0,0
Exp/Cntr=0.3,0.1

Type RM Length L Ch R = 1 ,345071  ,542,538.2,532.1
XS GIS Cut Line= 2
 2273574.8347044565809.2447562812275011.15731841565870.924204911
#Sta/Elev= 30
       0 3946.36    57.4  3922.1   169.5 3895.63   209.5 3872.24   273.6 3841.98
   401.7 3768.82   453.8 3744.01   465.8 3733.35   493.8 3729.44   505.8 3722.86
   521.8 3718.99   534.8 3710.39   581.9 3690.85   601.9 3673.95   613.9 3668.27
     682 3660.09     710 3660.26     738  3651.5   765.2 3649.02   790.1 3647.16
  859.023649.049   874.1 3654.25   906.2 3657.07  1043.1  3683.2  1078.3 3696.14
  1134.4 3726.38  1146.4 3727.65  1178.4 3741.69  1310.3 3764.53  1437.6 3804.89
#Mann= 7 ,-1,0
       0      .1       0     490     .06       0     590      .1       0
   765.2    .045       0  859.02      .1       0     990     .12       0
    1090      .1       0
Bank Sta=765.2,859.02
XS Rating Curve= 0 ,0
Exp/Cntr(USF)=0,0
Exp/Cntr=0.3,0.1

Type RM Length L Ch R = 1 ,344532  ,518.8,518,518.6
XS GIS Cut Line= 3
2273566.35032488566403.9441107452274129.85212505566402.555999116
2274975.16117981566282.924669369
#Sta/Elev= 30
       0 3886.51    21.8 3878.13    73.8    3849   221.8 3788.23   285.8 3766.35
   381.8 3741.67   397.8 3734.61   417.8 3720.42   433.8 3720.39   457.8 3712.32
   485.8 3688.72   557.8 3681.87   602.2 3666.23   638.6 3666.08   650.7 3662.18
   683.6 3661.12   727.4 3654.23   743.6  3645.4   773.1 3644.84   808.2 3645.09
   844.6 3651.73   921.4 3650.66     982 3659.87  1014.3 3661.33  1135.5 3712.74
  1183.9 3731.47  1196.1  3732.6  1252.6 3757.29  1353.6 3793.57  1417.2 3824.52
#Mann= 7 ,-1,0
       0      .1       0     400     .06       0     500      .1       0
   743.6    .045       0   808.2      .1       0   903.5     .12       0
   933.5      .1       0
Bank Sta=743.6,808.2
XS Rating Curve= 0 ,0
Exp/Cntr(USF)=0,0
Exp/Cntr=0.3,0.1