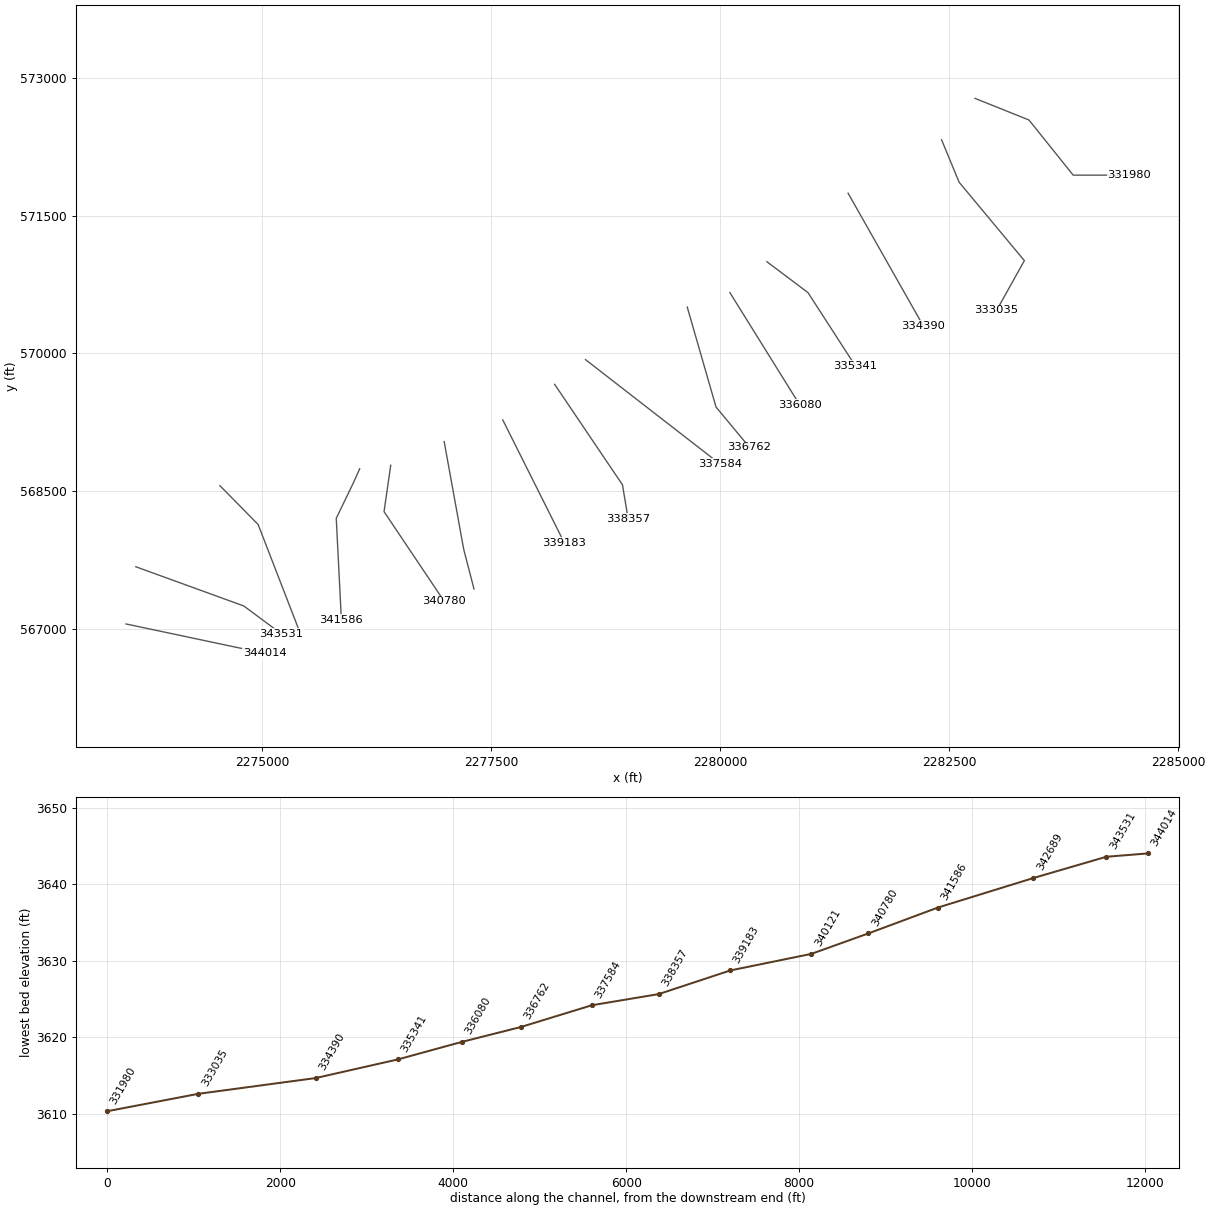
HEC-RAS study SHAVERSFK.prj: SHAVERSFK

--- SHAVERSFK.g01 (geometry) --- (continued)

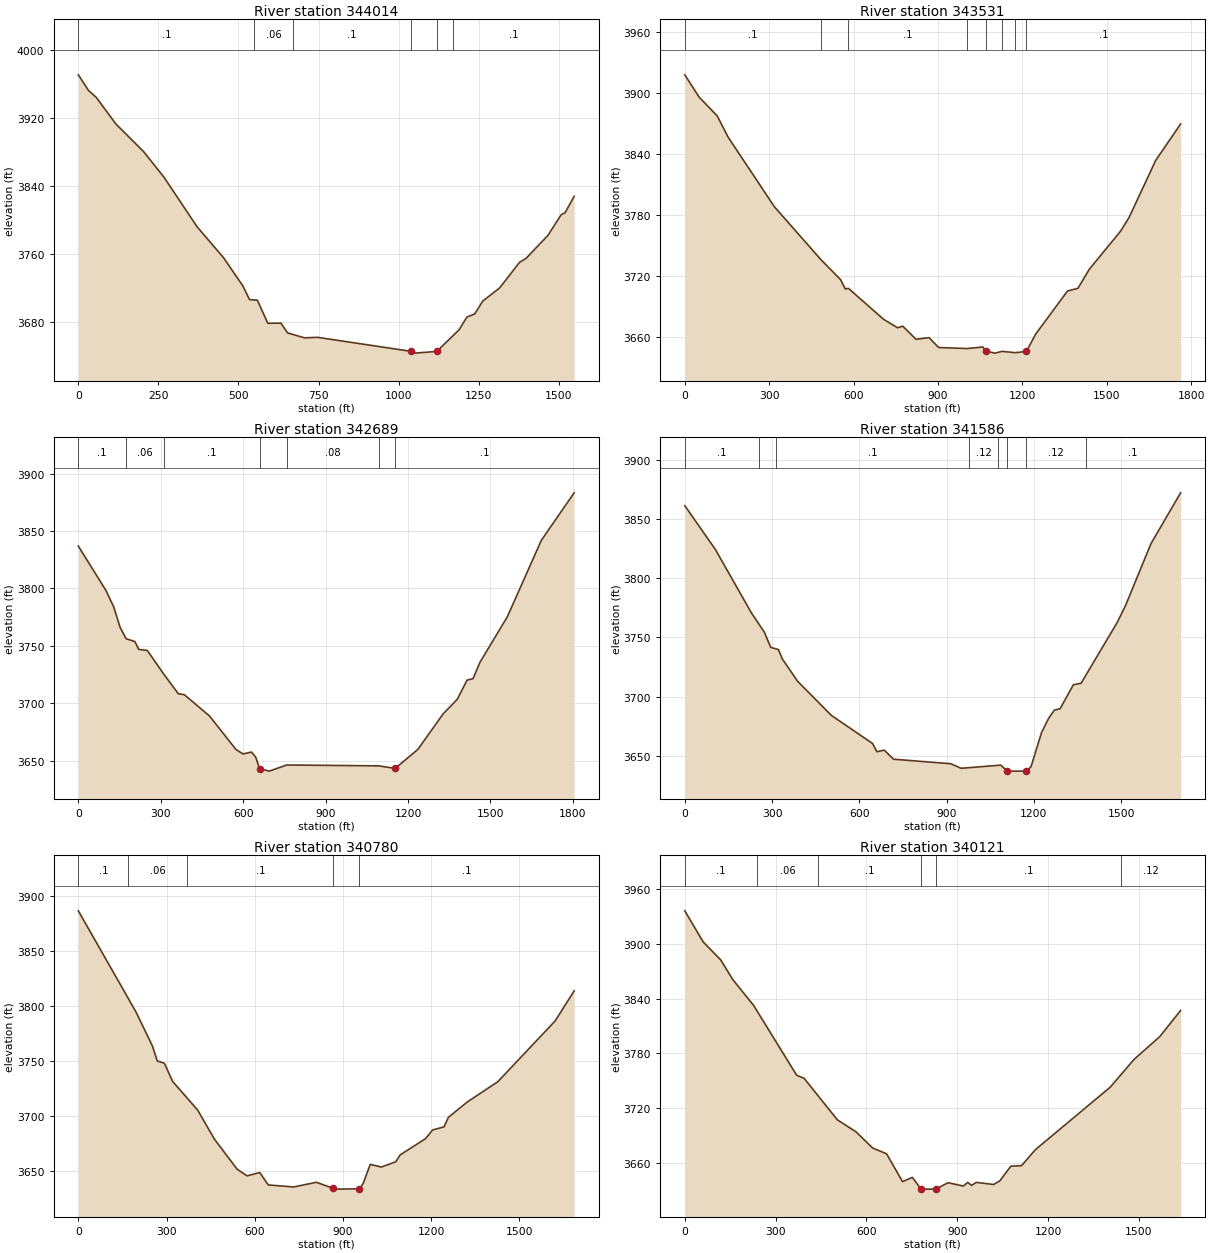
Type RM Length L Ch R = 1 ,344014  ,485.2,483.5,467.1
XS GIS Cut Line= 2
2273513.09084623567054.7894694462275027.98952596566734.977525946
#Sta/Elev= 30
       0 3970.59    31.8 3952.29    56.3 3943.95   117.6 3912.78   203.5 3880.65
   267.3 3850.57   371.1  3792.2   452.9 3756.29   513.7 3723.02   534.6 3706.89
   559.1 3706.15   591.8 3679.07   632.7 3679.25   653.2 3667.85   706.3 3661.98
   747.2  3662.6  1040.3 3646.09  1049.7 3644.06  1119.2 3646.02  1188.8 3671.37
  1213.2 3686.33  1237.8 3690.01    1263 3705.21  1315.5 3720.49  1377.8 3750.61
  1398.1 3755.23  1466.7 3782.35  1507.6 3806.41  1519.9 3808.79  1548.3 3828.02
#Mann= 6 ,-1,0
       0      .1       0     550     .06       0     670      .1       0
  1040.3    .045       0  1119.2     .12       0    1170      .1       0
Bank Sta=1040.3,1119.2
XS Rating Curve= 0 ,0
Exp/Cntr(USF)=0,0
Exp/Cntr=0.3,0.1

Type RM Length L Ch R = 1 ,343531  ,866.3,842.1,532.2
XS GIS Cut Line= 3
2273619.69482739567677.5811488932274797.94935608567251.165224227
2275207.53307319 566948.18548828
#Sta/Elev= 30
       0 3917.95    50.7 3896.08   115.4 3877.39   153.7 3856.67   318.5 3787.89
   484.8 3735.52   553.5 3716.14   570.5 3706.87   581.7 3707.45   706.7 3676.94
   756.6 3668.61   774.7  3670.2   822.2 3657.24   868.3  3658.9   902.3 3649.15
  1003.3 3648.13  1059.7 3649.68 1071.523645.422  1102.3 3643.62  1128.3 3645.36
  1175.1 3644.06  1214.43645.267  1246.9 3662.23  1360.3 3704.84  1397.6 3707.53
    1438 3726.33  1549.4 3763.95  1579.2 3777.28  1673.7  3833.5  1762.5 3869.53
#Mann= 8 ,-1,0
       0      .1       0   484.8     .06       0   581.7      .1       0
  1003.3     .12       0 1071.52    .045       0  1128.3     .08       0
  1175.1    .045       0  1214.4      .1       0
Bank Sta=1071.52,1214.4
XS Rating Curve= 0 ,0
Exp/Cntr(USF)=0,0
Exp/Cntr=0.3,0.1

Type RM Length L Ch R = 1 ,342689  ,1104.5,1103,703.4
XS GIS Cut Line= 3
2274537.26871187568561.053472538 2274955.0499599568137.661488665
2275392.68735627567009.903582639
#Sta/Elev= 30
       0 3836.88     101 3798.04   129.1 3783.69   152.2 3765.98     174 3756.16
   205.6 3753.75   219.8 3746.91   250.9 3745.98   311.7  3725.1     364 3708.23
   385.7 3707.44   477.2 3688.94   573.6 3659.72   599.6  3655.8   630.1 3657.45
   645.5 3653.08   659.7 3643.01     695 3640.84   758.4 3646.19    1093 3645.42
  1153.1 3643.21  1235.9 3659.82  1327.7 3690.72    1379 3703.35  1414.8 3720.13
  1436.3 3721.34    1462 3735.75  1561.3 3775.28  1685.1  3841.9  1804.5 3883.26
#Mann= 7 ,-1,0
       0      .1       0     174     .06       0   311.7      .1       0
   659.7    .045       0   758.4     .08       0    1093    .045       0
  1153.1      .1       0
Bank Sta=659.7,1153.1
XS Rating Curve= 0 ,0
Exp/Cntr(USF)=0,0
Exp/Cntr=0.3,0.1

Type RM Length L Ch R = 1 ,341586  ,781,805.4,822.3
XS GIS Cut Line= 4
2276064.07506739568744.9993819452275996.45368885568594.932364152
2275807.88180923568204.9903188762275863.98916774567099.675356253
#Sta/Elev= 30
       0 3861.36   105.1 3824.35   228.8 3770.84   273.2 3754.54   295.4 3741.61
   322.1 3739.68   335.4 3731.77   387.7 3712.97   504.2 3684.02   645.6 3660.33
   660.5 3653.39   685.5 3654.73   717.7 3647.05     914 3643.24     950 3639.38
  1086.2 3642.04  1108.6  3637.1  1126.2 3636.98  1174.3 3637.02  1190.3 3640.77
  1226.4 3669.59  1250.4 3681.46  1270.4 3688.52  1290.4 3689.79  1335.6 3709.95
  1362.5 3711.32  1486.7 3762.72  1514.7 3776.71  1602.8 3829.38  1704.5 3872.21
#Mann= 8 ,-1,0
       0      .1       0   254.6     .06       0   314.6      .1       0
  977.74     .12       0 1077.74    .025       0  1108.6    .045       0
  1174.3     .12       0 1377.74      .1       0
Bank Sta=1108.6,1174.3
XS Rating Curve= 0 ,0
Exp/Cntr(USF)=0,0
Exp/Cntr=0.3,0.1

Type RM Length L Ch R = 1 ,340780  ,670.7,659.5,647
XS GIS Cut Line= 3
2276402.61980943568782.8961115162276329.68024337568277.929884937
2276986.13633792567301.661846885
#Sta/Elev= 30
       0 3886.66   195.7 3794.92   252.3 3763.58   268.5 3750.17   292.7 3748.05
     321 3731.44   405.9 3705.49   462.8 3679.16     540 3651.74   573.8 3645.69
   617.2 3648.64   646.1  3637.4   732.8 3635.56     810 3639.81   867.8 3634.23
   887.2 3633.59   956.4 3633.92     969 3638.74   993.1 3656.11  1030.8 3653.69
  1079.9 3658.45  1094.7 3664.69  1181.1 3679.48  1205.2 3687.41  1243.8 3690.19
    1259 3698.91  1322.4 3712.69  1426.9 3731.24  1622.1 3786.57  1686.7 3813.86
#Mann= 5 ,-1,0
       0      .1       0     170     .06       0     370      .1       0
   867.8    .045       0   956.4      .1       0
Bank Sta=867.8,956.4
XS Rating Curve= 0 ,0
Exp/Cntr(USF)=0,0
Exp/Cntr=0.3,0.1

Type RM Length L Ch R = 1 ,340121  ,926.6,937.7,949.4
XS GIS Cut Line= 3
2276986.13633792569040.9899606562277199.34430025567868.346167823
2277311.55901727567436.319507306
#Sta/Elev= 30
       0 3936.48    60.8 3902.32   118.6 3882.65   158.4 3861.08   227.5 3832.59
   369.8 3755.89   394.2 3752.62   503.9 3707.06   565.8  3693.8   620.8 3676.01
   666.6 3669.73   719.4 3639.17   751.9 3643.81   780.4 3630.96   796.7 3630.91
   829.2 3630.95   869.8 3637.94   920.1 3634.31   934.9  3638.3   947.1 3634.99
   963.3 3638.33  1020.3    3636  1040.5 3639.89  1077.2 3656.08  1112.7 3656.68
  1158.5 3674.27  1405.9 3742.95  1483.8 3773.17  1569.1 3798.32  1638.2 3827.06
#Mann= 6 ,-1,0
       0      .1       0     240     .06       0     440      .1       0
   780.4    .045       0   829.2      .1       0 1441.87     .12       0
Bank Sta=780.4,829.2
XS Rating Curve= 0 ,0
Exp/Cntr(USF)=0,0
Exp/Cntr=0.3,0.1

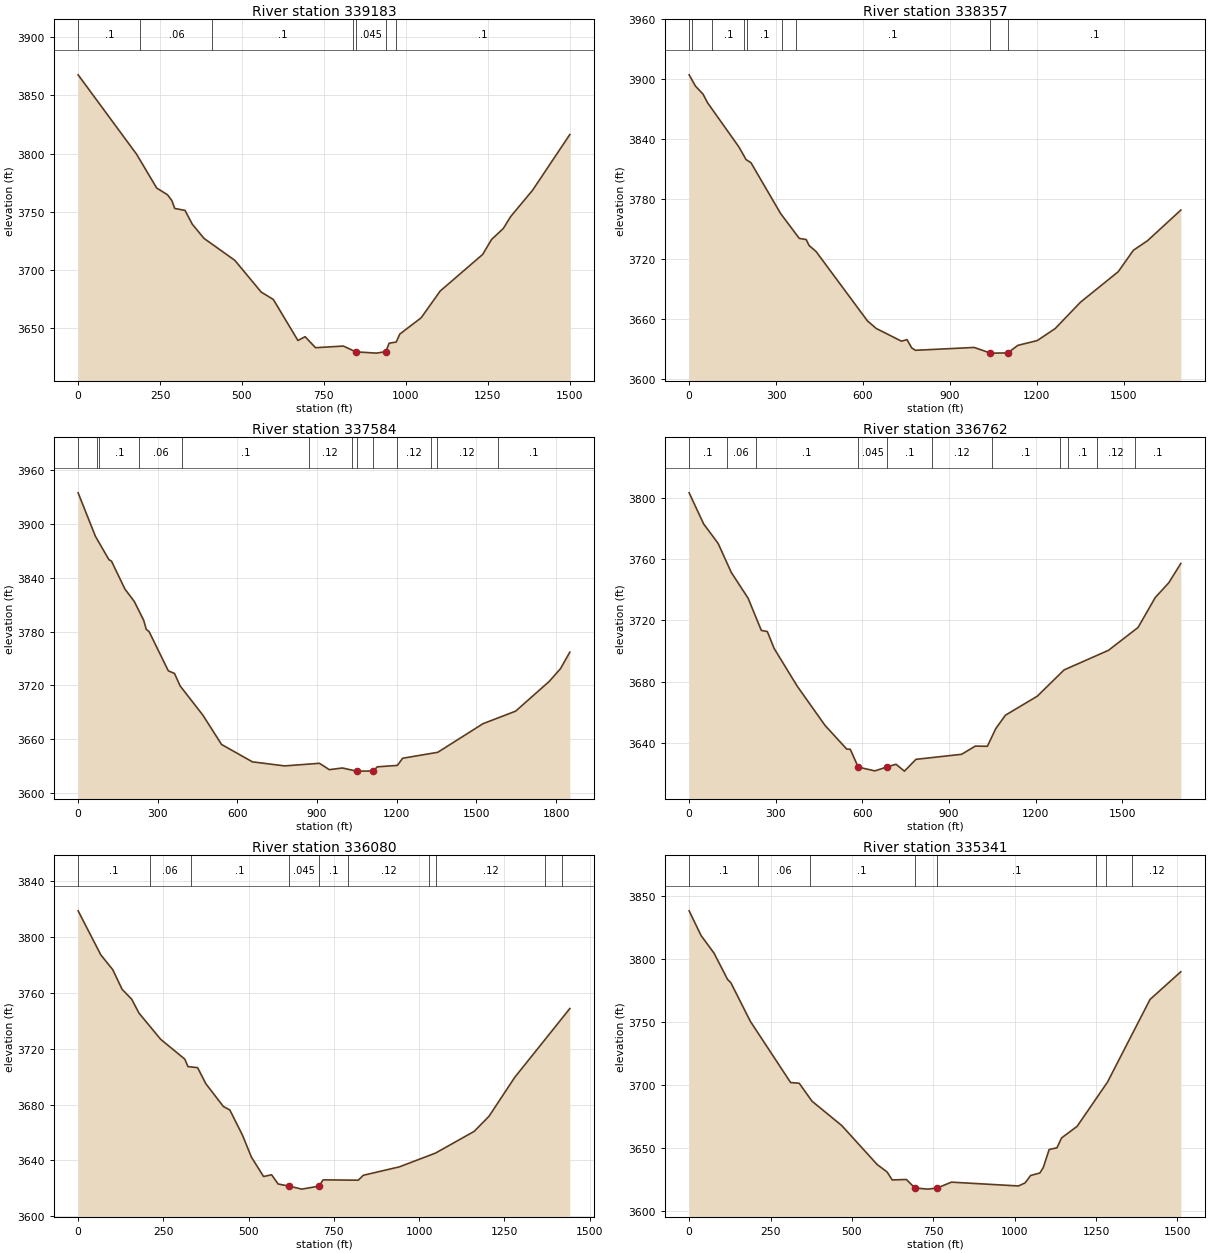
Type RM Length L Ch R = 1 ,339183  ,822.6,826.3,827.7
XS GIS Cut Line= 2
2277625.76022492569276.6408663932278299.04852702567935.674998033
#Sta/Elev= 30
       0 3867.68   178.4 3799.52   239.8 3770.47   272.6 3764.74   285.9 3759.81
   294.8 3752.98   326.3 3751.26   348.5  3739.4   384.3 3727.23   478.2 3708.42
   558.6 3681.19   595.7 3674.82   670.8  3639.6   692.7 3642.84   724.5  3633.4
   809.5 3634.81   847.4 3629.85   910.2 3628.74   939.3 3630.01     949 3637.21
   970.7 3638.27   981.7 3645.08  1046.8 3659.07  1104.9 3682.05  1234.7 3713.53
  1261.6 3726.31  1297.6 3735.78  1319.8 3745.92  1386.9 3768.62  1500.5 3816.41
#Mann= 7 ,-1,0
       0      .1       0     190     .06       0     410      .1       0
     840     .12       0   847.4    .045       0   939.3     .12       0
     970      .1       0
Bank Sta=847.4,939.3
XS Rating Curve= 0 ,0
Exp/Cntr(USF)=0,0
Exp/Cntr=0.3,0.1

Type RM Length L Ch R = 1 ,338357  ,762.6,772.9,782.4
XS GIS Cut Line= 3
2278192.44454586569663.7816401032278933.06167817568569.688149182
2278994.77977253568199.379583025
#Sta/Elev= 30
       0 3904.52    21.8 3893.24    47.8 3885.27    63.7 3876.49   172.2 3832.08
   196.4 3819.62   213.6 3816.36   315.6 3765.56   379.9 3740.67   404.1 3739.42
   413.7 3733.55   437.9  3727.5   615.2 3657.98   645.6 3650.37   732.5 3637.65
   751.8 3639.16   767.9 3630.91   780.8 3628.49   983.7 3631.34  1036.8 3625.97
  1051.3 3625.65  1099.6 3625.89  1134.1 3633.43  1201.1 3638.21  1263.3 3650.32
  1350.1 3676.61  1480.8  3707.3  1532.9 3728.74  1581.6 3738.28  1696.6 3769.01
#Mann= 9 ,-1,0
       0      .1       0      10     .12       0      80      .1       0
     190     .12       0     200      .1       0     320     .06       0
     370      .1       0  1036.8    .045       0  1099.6      .1       0
Bank Sta=1036.8,1099.6
XS Rating Curve= 0 ,0
Exp/Cntr(USF)=0,0
Exp/Cntr=0.3,0.1

Type RM Length L Ch R = 1 ,337584  ,834.5,821.5,761.8
XS GIS Cut Line= 2
2278529.08869691569933.0969609452279993.49075399568799.728319068
#Sta/Elev= 30
       0 3934.97    65.2  3886.4   116.2 3860.22   125.3 3858.89   176.3  3827.5
   211.3 3813.75   246.7 3792.76   256.8 3782.44   267.3 3779.98   339.7 3736.19
     363 3733.26   384.2 3719.33   469.8 3686.74   540.1 3653.97   656.4 3634.56
   777.6 3630.03   908.9 3632.93   945.9 3625.82   995.3  3627.7  1048.6 3624.19
  1111.3 3624.29  1126.8 3628.97  1202.5 3630.61    1222 3638.56  1354.4 3645.21
  1524.7 3677.14  1647.8 3691.17  1774.2 3724.37  1816.7 3738.64  1851.8 3757.05
#Mann= 13 ,-1,0
       0      .1       0      70     .12       0      80      .1       0
     230     .06       0     390      .1       0     870     .12       0
    1030      .1       0  1048.6    .045       0  1111.3      .1       0
    1200     .12       0    1330      .1       0    1350     .12       0
    1580      .1       0
Bank Sta=1048.6,1111.3
XS Rating Curve= 0 ,0
Exp/Cntr(USF)=0,0
Exp/Cntr=0.3,0.1

Type RM Length L Ch R = 1 ,336762  ,669.7,682.8,692.8
XS GIS Cut Line= 3
2279640.01439538570505.3920177342279954.21560303569416.909262665
2280318.91343334568979.271866296
#Sta/Elev= 30
       0 3803.55    50.2 3783.22   100.5  3770.4   145.9 3751.46   204.2 3734.56
     250 3713.47   270.8 3712.73   294.3 3701.68   374.9 3676.79   470.7 3651.25
   545.6 3635.78   558.1 3635.61   585.4 3623.98   643.2  3621.5  685.533624.082
   716.3 3625.84   745.5 3621.34   785.4 3629.05   943.7 3632.37   991.1 3637.74
  1032.7 3637.61  1061.9 3649.21  1095.2 3657.95  1205.5 3670.39  1298.4 3687.61
  1452.2 3700.45  1554.5 3715.41  1614.1 3735.02  1660.8 3744.64  1702.6 3757.31
#Mann= 11 ,-1,0
       0      .1       0     130     .06       0     230      .1       0
   585.4    .045       0  685.53      .1       0     840     .12       0
    1050      .1       0 1282.92     .12       0 1312.92      .1       0
 1412.92     .12       0 1542.92      .1       0
Bank Sta=585.4,685.53
XS Rating Curve= 0 ,0
Exp/Cntr(USF)=0,0
Exp/Cntr=0.3,0.1

Type RM Length L Ch R = 1 ,336080  ,736.3,738.7,738.9
XS GIS Cut Line= 2
  2280105.705471570662.4926215592280868.76554672569439.352206068
#Sta/Elev= 30
       0 3818.93    66.6 3787.33   101.5 3776.75   128.8 3762.71   157.1 3755.53
   178.5 3745.59     242 3726.82   312.7 3712.62   322.1 3707.24   350.4 3706.48
   374.4 3694.99   425.9 3678.62   444.7 3676.17   481.8 3658.13   507.9 3642.42
   543.7 3628.44   567.3 3629.68   586.3 3623.09   619.2 3621.51     656 3619.39
  706.593621.562   718.2 3626.04   821.5  3625.8     836 3629.31   941.8 3635.35
  1047.9 3645.24  1161.2  3660.8  1204.7 3671.64  1280.2 3699.56  1441.6 3748.86
#Mann= 10 ,-1,0
       0      .1       0     210     .06       0     330      .1       0
   619.2    .045       0  706.59      .1       0     790     .12       0
    1030      .1       0    1050     .12       0    1370      .1       0
    1420     .12       0
Bank Sta=619.2,706.59
XS Rating Curve= 0 ,0
Exp/Cntr(USF)=0,0
Exp/Cntr=0.3,0.1

Type RM Length L Ch R = 1 ,335341  ,948.8,951,944.5
XS GIS Cut Line= 3
2280509.67845227570999.1367726122280958.53732034570662.492621559
2281474.72501862569865.768130735
#Sta/Elev= 30
       0 3838.43    36.6 3818.82    76.6 3804.72   118.1 3783.86   128.1 3781.28
   188.1 3750.52   311.8 3701.86   338.1 3701.32   377.5 3687.03   468.9 3667.65
   577.7 3636.65   608.2 3630.71   623.9 3624.41   667.3 3624.78   693.4 3618.04
   733.3  3617.1  762.163618.017   805.7 3622.65  1011.5 3619.62  1031.8 3622.01
  1049.1 3627.97  1077.4 3629.93  1087.9 3634.31    1106 3648.62  1129.8 3649.97
  1144.1 3657.82  1191.8 3667.04    1285 3702.15  1415.8 3767.95  1510.4 3789.99
#Mann= 8 ,-1,0
       0      .1       0     210     .06       0     370      .1       0
   693.4    .045       0  762.16      .1       0 1251.07     .12       0
 1281.07      .1       0 1361.07     .12       0
Bank Sta=693.4,762.16
XS Rating Curve= 0 ,0
Exp/Cntr(USF)=0,0
Exp/Cntr=0.3,0.1

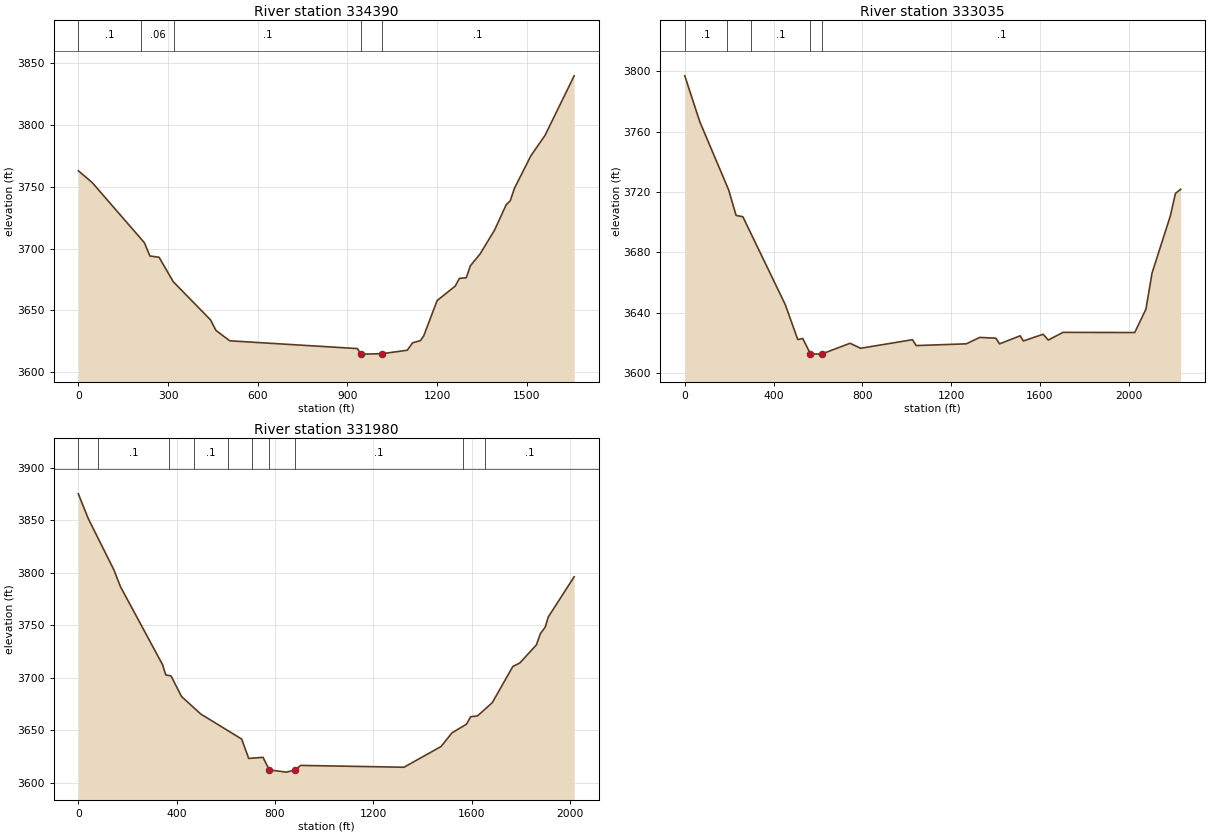
Type RM Length L Ch R = 1 ,334390  ,1340.3,1354.9,1358.8
XS GIS Cut Line= 2
2281396.17471671571745.3646407782282215.34215093570303.405527103
#Sta/Elev= 30
       0 3762.98    46.2 3753.48     221 3704.78   239.4 3694.03     270 3693.02
   317.6  3673.2   441.9 3642.43   460.3 3633.86   506.3 3625.44   933.1 3619.15
   944.8 3615.03   950.7 3614.66 1015.813615.005  1100.3 3617.83  1118.1 3623.83
  1144.3 3625.59  1154.9 3629.21    1200 3657.96  1260.7 3669.71  1274.5 3675.92
  1297.5 3676.42  1311.3 3686.15  1343.5  3695.6  1392.9 3715.29  1430.9 3735.42
  1444.7 3738.73  1458.5  3748.7  1513.7 3775.11  1560.9 3791.58  1658.4 3839.76
#Mann= 5 ,-1,0
       0      .1       0     210     .06       0     320      .1       0
   944.8    .045       0 1015.81      .1       0
Bank Sta=944.8,1015.81
XS Rating Curve= 0 ,0
Exp/Cntr(USF)=0,0
Exp/Cntr=0.3,0.1

Type RM Length L Ch R = 1 ,333035  ,1051.4,1054.8,1054.9
XS GIS Cut Line= 4
2282416.62375924572327.6146254782282608.55218152571864.313416585
2283320.84629366571010.8798253742283017.30489624570468.735994021
#Sta/Elev= 30
       0 3796.95    67.6 3766.54   197.5 3721.44   231.1 3704.49   261.7  3703.6
   452.9 3645.35   509.1 3622.26   531.6 3622.97   565.9 3612.82   605.7  3612.6
   619.5 3612.82   744.8  3619.8   792.1 3616.47    1026 3622.16    1043 3618.27
  1268.7 3619.42  1328.8 3623.66  1401.7 3623.17  1418.5  3619.4  1511.1 3624.74
  1525.8 3621.33  1614.9 3625.77    1638 3621.93  1704.5 3627.02  2027.6 3626.91
  2078.1  3642.4  2105.6 3666.31  2188.1 3704.16    2211 3719.03  2234.4  3721.8
#Mann= 5 ,-1,0
       0      .1       0     190     .06       0     300      .1       0
   565.9    .045       0   619.5      .1       0
Bank Sta=565.9,619.5
XS Rating Curve= 0 ,0
Exp/Cntr(USF)=0,0
Exp/Cntr=0.3,0.1

Type RM Length L Ch R = 1 ,331980  ,705.5,790.9,888
BEGIN DESCRIPTION:
Structure XS 4
END DESCRIPTION:
XS GIS Cut Line= 4
2282782.02647187572777.7400373392283371.15373621572542.089131602
2283853.67701939571941.7403955592284465.24722713571941.740395559
#Sta/Elev= 30
       0 3875.32    41.1 3851.38   144.5 3802.99   171.3 3786.95   342.7 3712.53
   355.6 3702.87   377.1 3701.92   419.3 3682.43   497.7 3665.69   664.3  3641.8
   692.8 3623.34   751.1 3624.41  776.56 3612.43   846.4 3610.32     882 3612.38
   904.3 3616.72  1324.4 3614.98  1475.2 3634.74  1519.2 3647.66  1578.7 3656.03
  1595.2 3663.03  1623.2 3663.87  1683.2 3676.43  1767.2    3711  1795.2 3714.22
  1862.7 3731.44  1879.2 3742.26  1898.7 3748.43  1911.2  3758.1  2016.3 3796.35
#Mann= 10 ,-1,0
       0     .12       0      80      .1       0     370     .06       0
     470      .1       0     610     .12       0  704.51      .1       0
  776.56    .045       0     882      .1       0 1564.73     .06       0
 1654.73      .1       0
Bank Sta=776.56,882
XS Rating Curve= 0 ,0
Exp/Cntr(USF)=0,0
Exp/Cntr=0.3,0.1