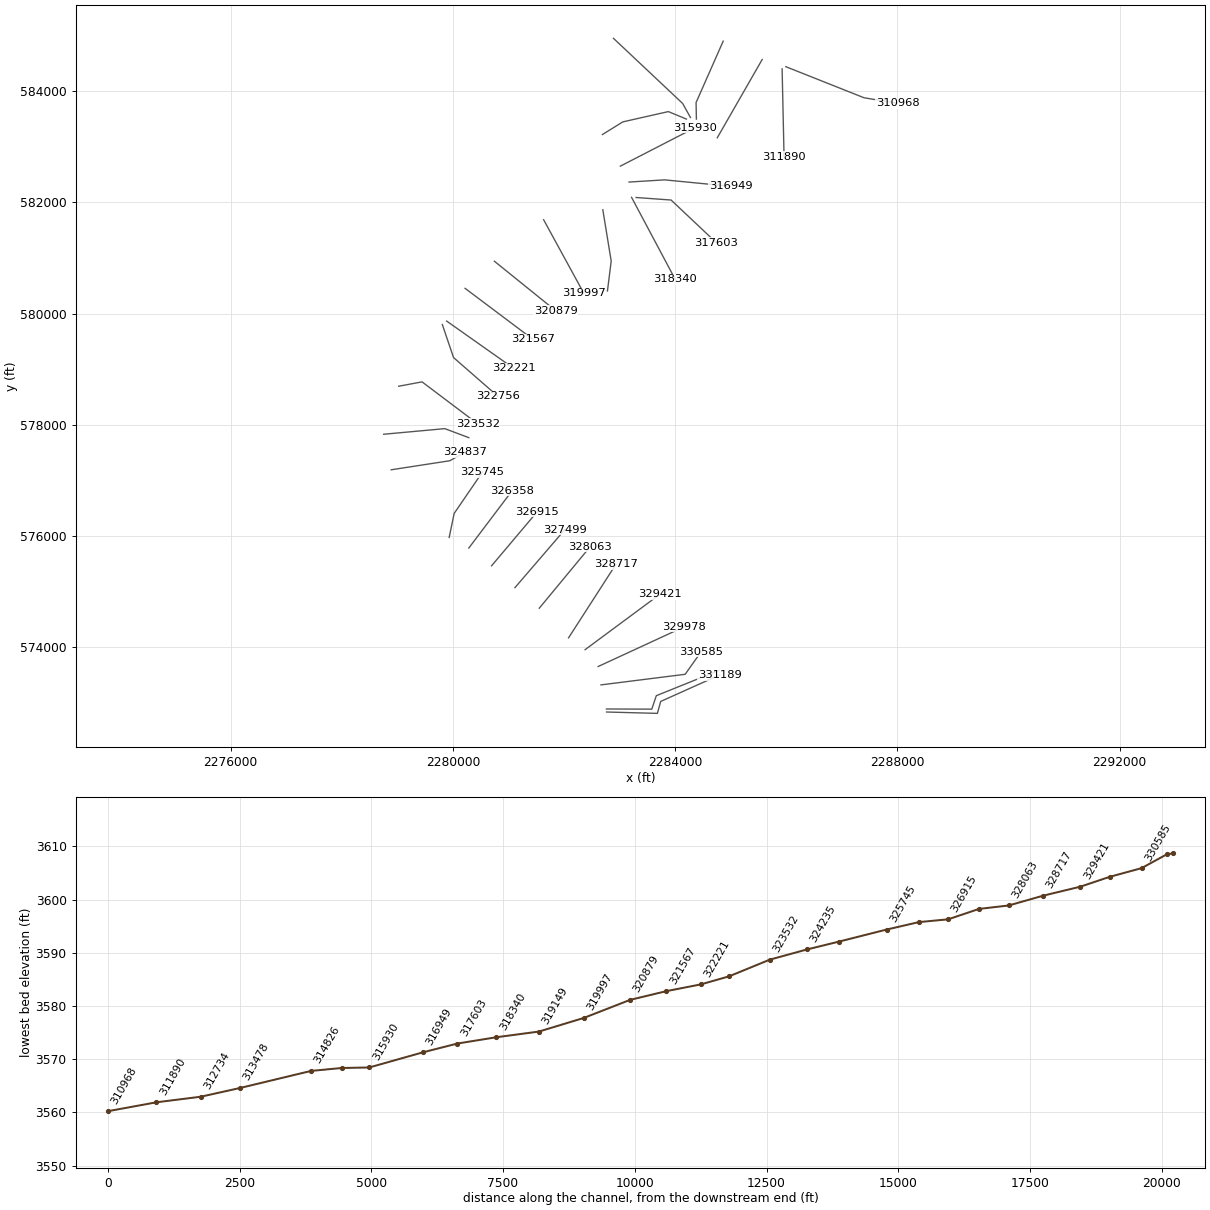
HEC-RAS study SHAVERSFK.prj: SHAVERSFK

--- SHAVERSFK.g01 (geometry) --- (continued)

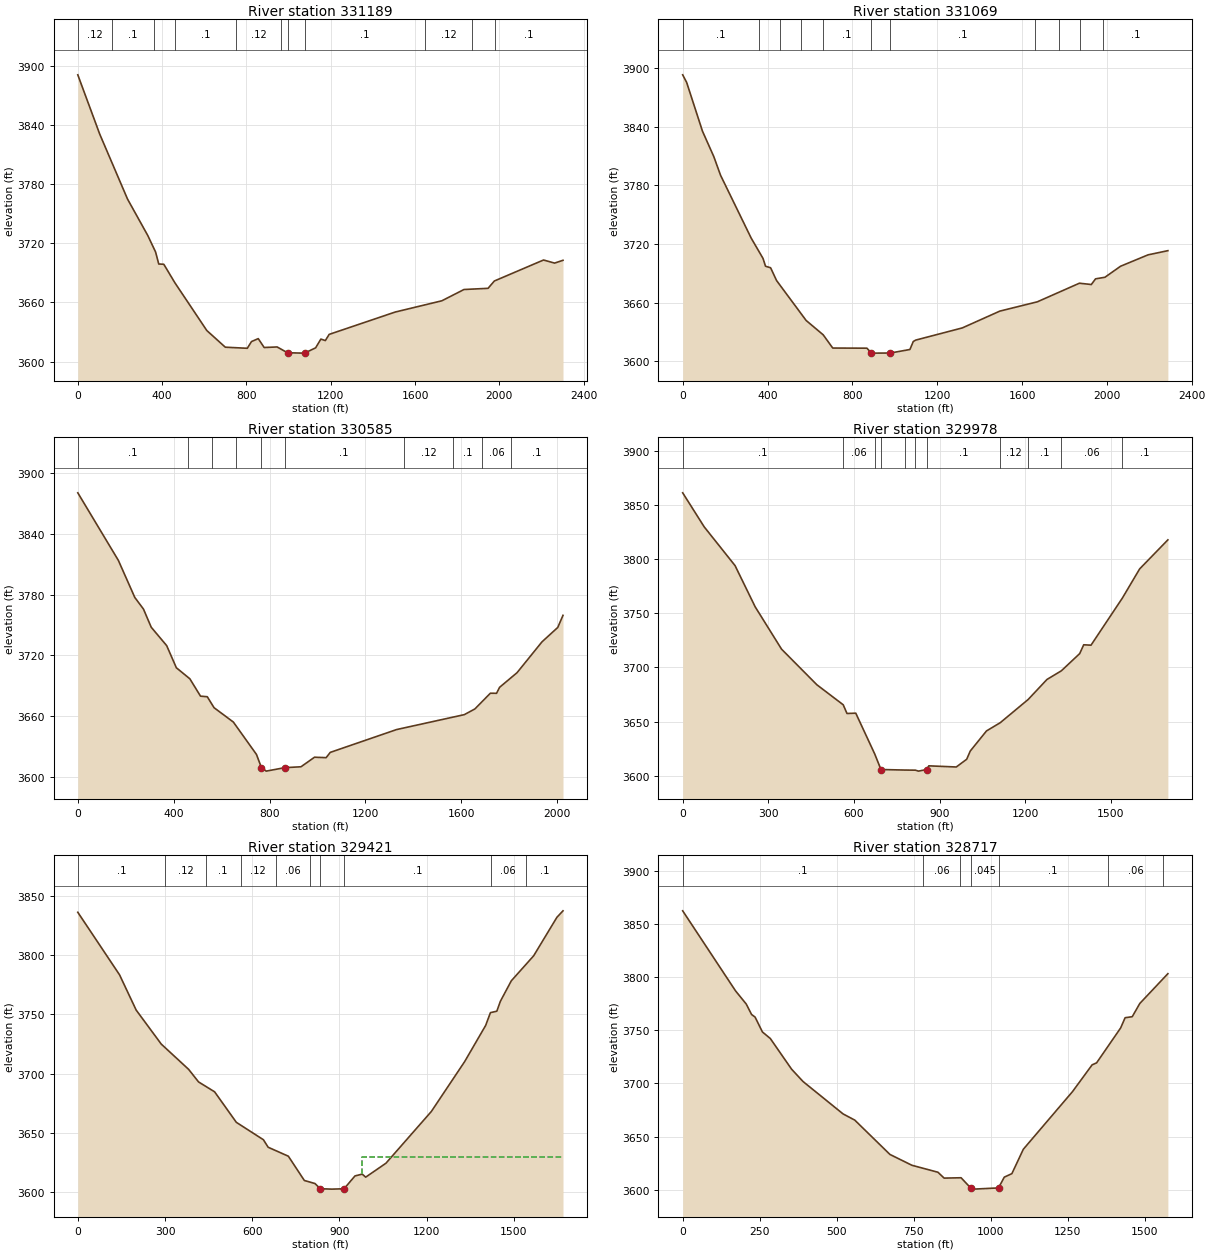
Type RM Length L Ch R = 1 ,331189  ,120.2,120.2,117.6
BEGIN DESCRIPTION:
Structure XS 3
END DESCRIPTION:
XS GIS Cut Line= 4
2282764.33971287572828.1572796852283679.02165547572803.656870508
2283738.91154457573018.7160177272284800.59594224573495.112862833
#Sta/Elev= 30
       0 3890.59   103.9  3830.6   235.9 3764.76     332 3727.84   369.1  3711.1
     384 3698.98     408 3698.71     460 3680.17   612.1 3631.59   699.8 3614.71
   804.1 3613.61   824.1 3620.42   856.1 3623.38   884.2 3614.39   945.7 3614.95
   995.1 3609.07  1069.8  3608.7  1078.5 3608.96  1128.4 3614.08  1153.2 3622.91
  1174.4 3621.42  1192.5 3627.67  1505.8 3650.31  1727.1 3661.71  1832.3 3673.15
  1946.3 3674.33  1976.3 3681.77  2209.5 3703.02    2262 3699.89  2301.9 3702.73
#Mann= 11 ,-1,0
       0     .12       0     160      .1       0     360     .06       0
     460      .1       0     750     .12       0  965.01      .1       0
   995.1    .045       0  1078.5      .1       0 1648.25     .12       0
 1868.25     .06       0 1978.25      .1       0
Bank Sta=995.1,1078.5
XS Rating Curve= 0 ,0
Exp/Cntr(USF)=0,0
Exp/Cntr=0.3,0.1

Type RM Length L Ch R = 1 ,331069  ,525.2,484.3,427.9
BEGIN DESCRIPTION:
Structure XS 2
END DESCRIPTION:
XS GIS Cut Line= 4
2282761.61744518572882.6026334112283578.29775108572879.880365725
2283659.96578167573122.1621898072284786.98460381573576.780893423
#Sta/Elev= 30
       0 3893.12    18.6 3885.42    93.4 3835.45   146.6 3809.57   178.6 3790.41
   322.9 3726.19   378.6 3705.46   390.6  3697.4   414.6 3695.84   442.6 3682.79
     582 3641.96   662.6 3627.24   707.5 3613.75   868.7 3613.62   889.8 3608.62
   898.5 3608.56   978.5 3608.66  1071.3 3612.27  1087.1  3620.4  1098.5 3621.87
  1318.4 3634.34  1495.3 3651.52  1672.1 3661.03  1870.5 3680.05  1926.6 3678.71
  1946.5  3684.5  1990.7 3686.12  2064.6 3697.41    2194 3709.04  2287.6 3713.32
#Mann= 11 ,-1,0
       0      .1       0     360     .06       0     460      .1       0
     560     .12       0     660      .1       0   889.8    .045       0
   978.5      .1       0 1662.36     .12       0 1772.36      .1       0
 1872.36     .06       0 1982.36      .1       0
Bank Sta=889.8,978.5
XS Rating Curve= 0 ,0
Exp/Cntr(USF)=0,0
Exp/Cntr=0.3,0.1

Type RM Length L Ch R = 1 ,330585  ,595.5,606.4,626.8
BEGIN DESCRIPTION:
Structure XS 1
END DESCRIPTION:
XS GIS Cut Line= 3
  2282664.201019573316.3706790232284179.09969874573507.135697953
2284466.54062466573913.264341763
#Sta/Elev= 30
       0 3880.24   169.3 3813.65   237.8 3777.13   274.1 3765.61   306.4 3747.74
   370.9 3729.61   411.2 3707.82   467.6 3696.92     512 3679.82   540.2 3679.28
   568.4 3668.48   649.1 3654.28   745.5 3622.36     766  3609.5   786.1 3605.93
   862.7 3609.32   931.3 3610.23   987.7 3619.64  1036.1  3619.2  1053.4  3624.4
  1330.4 3646.92  1612.7 3661.61  1656.8 3667.22  1721.4 3682.73  1747.2 3682.64
  1759.7 3688.51  1832.8 3702.99  1936.6 3733.32  2002.6 3747.56  2024.4 3759.49
#Mann= 10 ,-1,0
       0      .1       0     460     .06       0     560      .1       0
     660     .12       0     766    .045       0   862.7      .1       0
    1360     .12       0 1566.86      .1       0 1686.86     .06       0
 1806.86      .1       0
Bank Sta=766,862.7
XS Rating Curve= 0 ,0
Exp/Cntr(USF)=0,0
Exp/Cntr=0.3,0.1

Type RM Length L Ch R = 1 ,329978  ,546.6,557.2,563.3
XS GIS Cut Line= 2
2282613.70439635573647.4040942252284156.65675534574359.967547286
#Sta/Elev= 30
       0 3861.25    75.5 3829.78   183.4 3794.06   253.9    3756   346.4 3716.88
   469.8 3684.08   562.3 3665.54   575.5 3657.51   606.3 3657.79   672.3 3620.34
   694.5 3605.77     777 3605.29   815.2 3605.17     826 3604.29  854.59 3605.77
   862.2 3609.17   958.3 3608.11   994.8 3615.24  1007.3 3622.84  1064.1 3641.39
  1112.4 3649.02    1210 3670.42    1276 3688.93  1326.4 3696.93  1390.6  3712.8
  1404.7 3720.95  1430.2 3720.58  1540.2 3764.11  1600.6 3791.01  1699.5 3817.83
#Mann= 11 ,-1,0
       0      .1       0   562.3     .06       0   672.3      .1       0
   694.5    .045       0     777     .08       0   815.2    .045       0
  854.59      .1       0  1112.4     .12       0    1210      .1       0
  1326.4     .06       0  1540.2      .1       0
Bank Sta=694.5,854.59
XS Rating Curve= 0 ,0
Exp/Cntr(USF)=0,0
Exp/Cntr=0.3,0.1

Type RM Length L Ch R = 1 ,329421  ,685.9,704.3,717.5
XS GIS Cut Line= 2
2282378.05349061573950.3838301722283719.01935897574943.484075777
#Sta/Elev= 30
       0 3836.15   143.6 3783.35   200.8 3753.58     287 3724.89   381.1 3703.57
   415.3 3692.94   470.5 3684.59   545.2 3658.84   638.4 3644.12   654.7 3637.79
   724.2 3630.22   779.1 3609.74   815.7 3607.17   833.9 3602.78   872.9 3602.44
   915.7 3602.73   953.3 3613.58   978.2 3615.11   990.1 3612.54  1059.9 3624.33
    1216 3668.01  1330.4 3710.06  1402.7 3740.62  1419.1 3751.42  1441.1 3752.64
  1453.4 3761.04  1490.9 3778.29  1567.8 3799.42  1647.8 3831.92  1668.7 3837.38
#Mann= 10 ,-1,0
       0      .1       0     300     .12       0     440      .1       0
     560     .12       0     680     .06       0     800      .1       0
   833.9    .045       0   915.7      .1       0    1420     .06       0
    1540      .1       0
#XS Ineff= 2 , 0
                          977.33         3629.31
Permanent Ineff=
       F       F
Bank Sta=833.9,915.7
XS Rating Curve= 0 ,0
Exp/Cntr(USF)=0,0
Exp/Cntr=0.3,0.1

Type RM Length L Ch R = 1 ,328717  ,659.8,653.7,651.7
XS GIS Cut Line= 2
2282080.68449051574163.5917925062282933.51633985575487.725453312
#Sta/Elev= 30
       0 3862.13   171.5 3786.98   206.3 3774.58   223.6 3764.78     235 3762.33
   258.8 3748.37   284.4 3742.23   353.6 3713.37   390.6 3701.83   520.5 3671.41
   558.6 3665.57   672.7 3633.34   744.1 3623.15   828.5 3616.62   848.7  3611.1
   903.7 3611.43   935.5 3601.65   944.2 3600.75  1025.2 3601.88  1043.9    3612
  1068.6 3615.29  1105.7 3638.18  1265.4 3692.34  1329.1 3717.48  1343.6 3719.34
  1421.7 3752.14  1436.2 3761.75  1459.3 3762.68  1483.9 3775.14    1575  3803.1
#Mann= 7 ,-1,0
       0      .1       0     780     .06       0     900      .1       0
   935.5    .045       0  1025.2      .1       0    1380     .06       0
    1560      .1       0
Bank Sta=935.5,1025.2
XS Rating Curve= 0 ,0
Exp/Cntr(USF)=0,0
Exp/Cntr=0.3,0.1

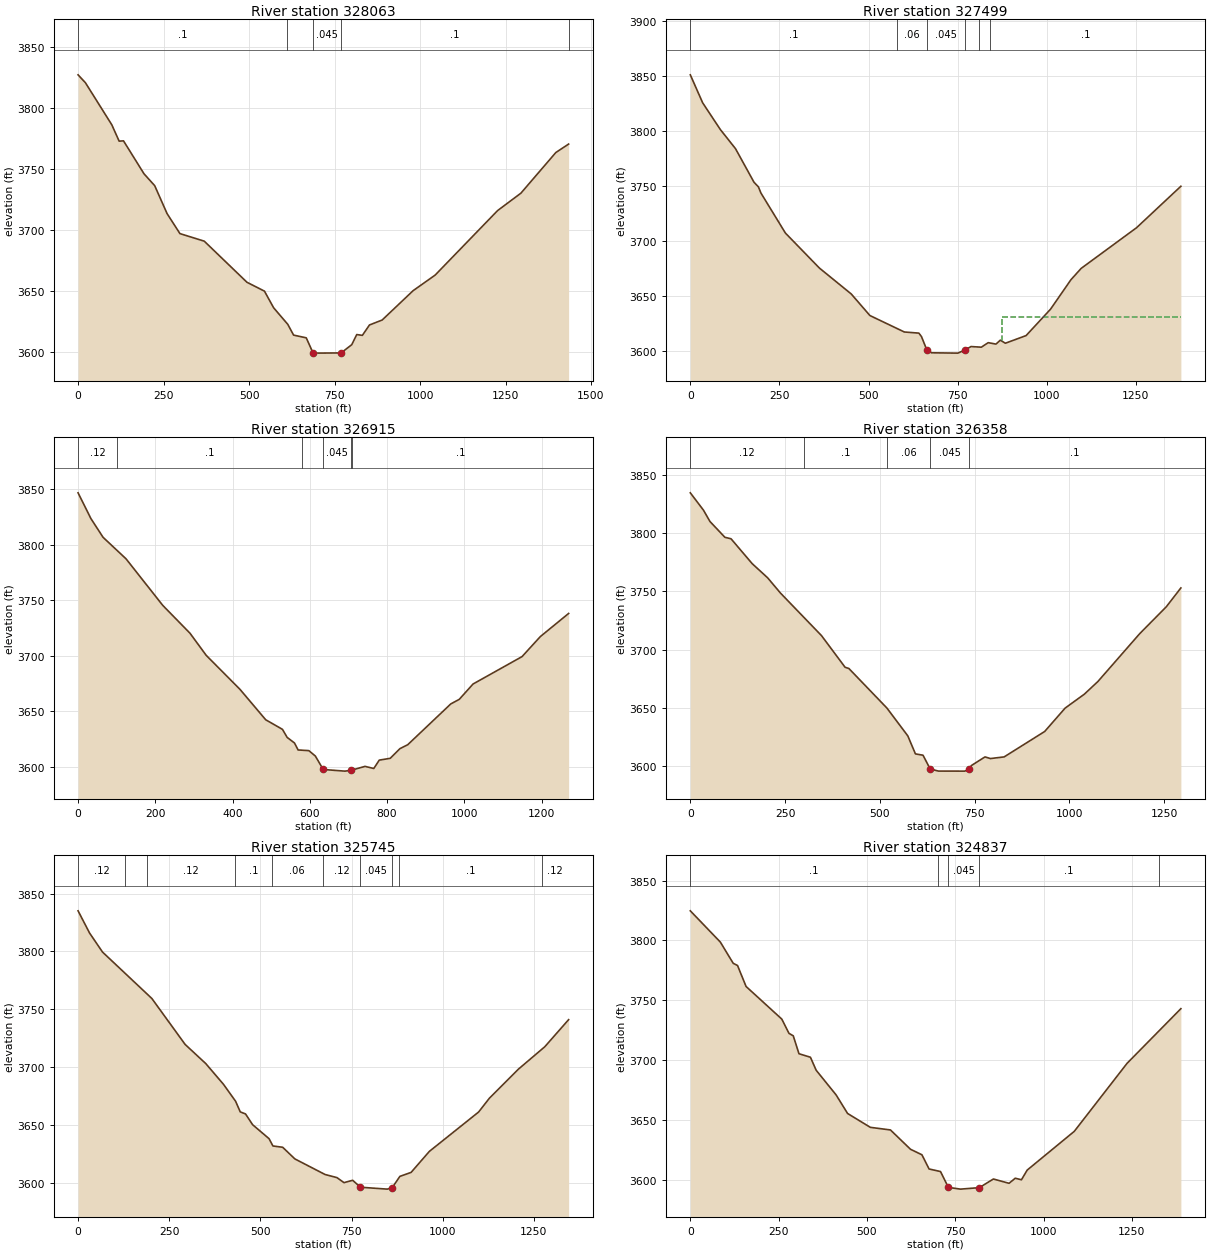
Type RM Length L Ch R = 1 ,328063  ,564.5,564.4,562.4
XS GIS Cut Line= 2
2281553.27532053574696.6116983392282467.82526422575801.926660961
#Sta/Elev= 30
       0 3826.81    21.5 3820.34    98.7 3785.87   120.1  3772.5   132.9 3772.74
   192.8 3745.78   224.1 3736.06   260.3 3713.17   297.9 3696.79     369  3690.6
   493.9 3656.94   545.1 3649.67   571.8 3636.09   613.4 3622.46   630.3 3613.66
   667.3 3611.44   687.1  3599.1   688.5 3598.91   769.1 3599.07   800.3  3605.8
     815 3614.11   831.4 3613.46   852.2 3621.96   889.3 3626.02   979.8 3650.04
  1044.3 3662.82  1226.9 3715.64  1295.1 3729.91  1397.3 3763.22  1434.6  3770.1
#Mann= 5 ,-1,0
       0      .1       0     610     .06       0   687.1    .045       0
   769.1      .1       0 1434.62     .06       0
Bank Sta=687.1,769.1
XS Rating Curve= 0 ,0
Exp/Cntr(USF)=0,0
Exp/Cntr=0.3,0.1

Type RM Length L Ch R = 1 ,327499  ,582.8,583.4,584.8
XS GIS Cut Line= 2
2281115.63792416575066.920264497 2282013.3556603576110.517132759
#Sta/Elev= 30
       0 3851.06    34.6 3825.65    84.2 3801.38   126.8 3783.99   178.7 3753.49
     191 3749.32   198.2 3743.66   266.8 3707.34   362.2 3675.54   451.5 3652.02
     504  3632.4   600.5 3617.47   641.4 3616.42   648.7 3613.27   663.3 3601.46
     677 3598.56   750.8 3598.26   770.6 3601.11   787.7 3604.23   816.6 3603.66
   835.9 3607.76   857.7 3606.46   869.9 3610.03   884.1 3607.25   942.2 3614.19
  1010.8 3638.16  1068.1 3664.96  1096.8 3675.24  1252.1 3712.15  1376.6 3749.85
#Mann= 6 ,-1,0
       0      .1       0     580     .06       0   663.3    .045       0
   770.6      .1       0     810     .12       0     840      .1       0
#XS Ineff= 2 , 0
                          874.37         3630.86
Permanent Ineff=
       F       F
Bank Sta=663.3,770.6
XS Rating Curve= 0 ,0
Exp/Cntr(USF)=0,0
Exp/Cntr=0.3,0.1

Type RM Length L Ch R = 1 ,326915  ,554.3,557,559.2
XS GIS Cut Line= 2
2280694.83273535575459.6717740582281514.00016957576430.329076259
#Sta/Elev= 30
       0 3846.83    33.2 3823.67    64.8 3806.76   124.1 3787.46   219.2 3745.54
   289.8 3720.44   331.7 3700.57   419.3  3669.9   485.8 3642.55   529.3 3633.89
   541.3 3626.68   560.3 3621.65   569.7 3615.36   597.5 3614.76   614.4 3609.86
   634.7  3597.8   690.5 3596.31   705.7 3596.93   742.9  3600.6   765.6 3598.66
   779.8 3606.21   808.2 3607.84   833.2 3616.51   853.6  3620.1     965 3656.81
     987 3660.93  1022.6 3674.72  1149.5  3699.4    1197 3717.48  1270.1 3738.24
#Mann= 6 ,-1,0
       0     .12       0     100      .1       0     580     .06       0
   634.7    .045       0   705.7     .06       0     710      .1       0
Bank Sta=634.7,705.7
XS Rating Curve= 0 ,0
Exp/Cntr(USF)=0,0
Exp/Cntr=0.3,0.1

Type RM Length L Ch R = 1 ,326358  ,610.7,613,613.9
XS GIS Cut Line= 2
2280285.24901823575779.483717558 2281065.1413015576811.859114119
#Sta/Elev= 30
       0 3834.63    34.7 3819.74    51.8 3810.03    91.1 3796.49   107.4 3795.18
   163.2 3773.84   203.9 3761.71   237.7 3748.62     346 3712.07   408.2 3684.92
   418.2 3683.86   518.5 3649.92   573.6 3626.03   593.7 3610.57   613.7 3609.43
  632.633597.609   654.4 3595.81     724 3595.78   734.4 3597.43   741.5 3600.63
   777.2 3607.98   791.5 3606.57   827.7 3607.99   934.6  3629.8   988.5 3649.87
  1039.1  3661.8  1074.9 3672.69  1185.2 3713.76  1255.4 3736.86  1293.8 3753.02
#Mann= 5 ,-1,0
       0     .12       0     300      .1       0     520     .06       0
  632.63    .045       0   734.4      .1       0
Bank Sta=632.63,734.4
XS Rating Curve= 0 ,0
Exp/Cntr(USF)=0,0
Exp/Cntr=0.3,0.1

Type RM Length L Ch R = 1 ,325745  ,946.1,908.5,875.1
XS GIS Cut Line= 3
2279931.77265963575970.2487364882280021.54443324576402.275397005
2280532.12139567577148.503265171
#Sta/Elev= 30
       0 3835.19    31.6 3815.95    67.1  3799.5   202.4 3759.32   293.7 3719.56
   350.3 3702.99   398.6 3685.16     432 3670.43   444.8 3661.23   459.3 3659.43
   478.7 3650.14   523.8 3638.03   534.4 3631.72   561.1 3630.62   594.7  3620.5
   677.4 3607.04     710 3604.34   729.3    3600   753.2 3602.03   774.3 3596.02
   848.1 3594.38   861.6 3595.67   882.6 3605.41   913.4 3608.87   963.4 3627.02
  1098.5  3661.1  1128.2 3673.09  1207.8 3698.23  1279.8 3717.51  1345.4 3741.03
#Mann= 10 ,-1,0
       0     .12       0     130      .1       0     190     .12       0
     430      .1       0  531.26     .06       0  671.26     .12       0
   774.3    .045       0   861.6     .12       0  881.26      .1       0
 1271.26     .12       0
Bank Sta=774.3,861.6
XS Rating Curve= 0 ,0
Exp/Cntr(USF)=0,0
Exp/Cntr=0.3,0.1

Type RM Length L Ch R = 1 ,324837  ,604.9,601.7,599.1
XS GIS Cut Line= 3
2278888.17579136577187.7784161282279942.99413133577350.489755803
2280223.53092387577507.590359628
#Sta/Elev= 30
       0 3824.73      85  3798.6   121.4 3780.87   133.6 3779.06   157.8 3761.51
     259 3734.21   279.3 3722.31   291.4 3720.26   307.6 3705.27     340 3702.36
   356.2 3691.51   412.8 3670.83   445.2 3655.33   509.7 3643.75   566.6 3641.57
   623.3 3625.43   655.7  3620.8   675.9 3608.94   708.3  3606.8   730.5 3593.57
   764.9  3592.1   818.2 3593.34     858 3600.56   902.4 3596.97   919.9 3601.22
   937.4 3599.91   953.7 3608.02    1087  3640.4  1236.5 3697.28  1388.8 3742.94
#Mann= 5 ,-1,0
       0      .1       0     700     .06       0   730.5    .045       0
   818.2      .1       0 1327.29     .12       0
Bank Sta=730.5,818.2
XS Rating Curve= 0 ,0
Exp/Cntr(USF)=0,0
Exp/Cntr=0.3,0.1

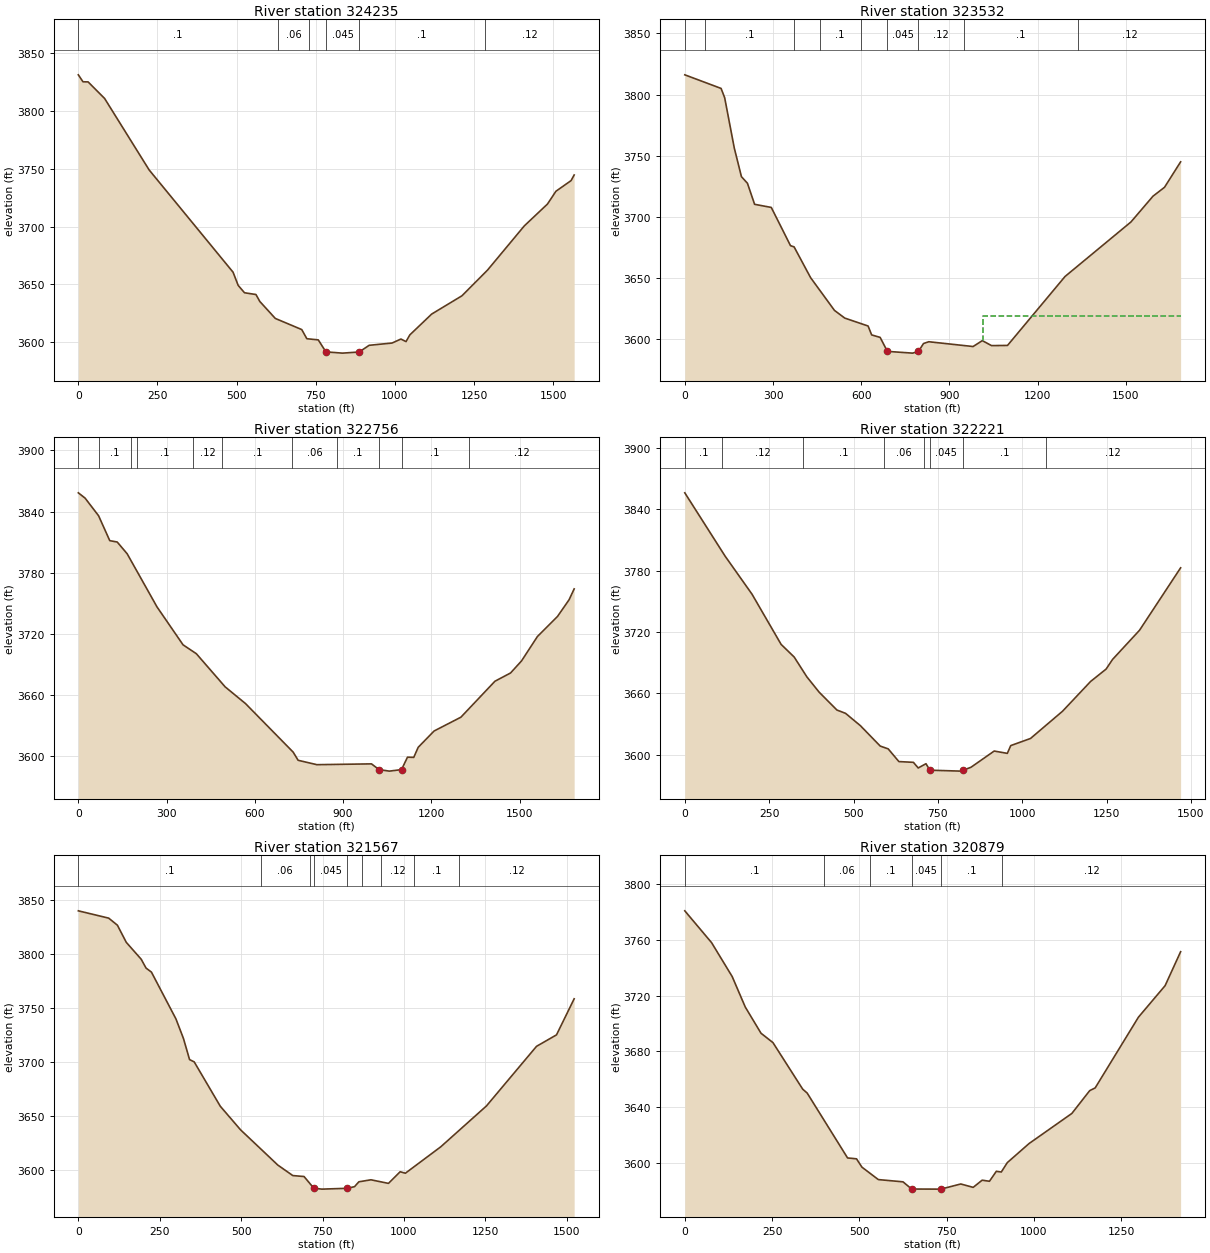
Type RM Length L Ch R = 1 ,324235  ,737.3,702.9,659.9
XS GIS Cut Line= 3
2278753.51813094577827.4023031272279853.22235771577928.395548443
2280285.24901823577765.684208768
#Sta/Elev= 30
       0 3831.12    14.7  3825.1    30.8 3825.02      83  3810.7   223.6 3748.96
   488.7 3660.57   504.8  3649.2   524.9 3642.79     561 3641.29   573.1 3635.32
   622.1 3620.62   705.6    3611   721.7 3603.09   757.8 3602.09   781.9 3591.73
   834.2 3590.64     887 3591.61   918.5  3597.4   990.8 3599.35  1018.9 3602.81
    1035 3600.61    1047 3606.39    1116 3624.39  1211.6 3640.18  1292.3 3662.36
  1408.5 3700.57  1481.7 3719.45  1508.4 3730.51  1556.3 3739.73    1566 3744.57
#Mann= 6 ,-1,0
       0      .1       0     630     .06       0     730      .1       0
   781.9    .045       0     887      .1       0 1284.33     .12       0
Bank Sta=781.9,887
XS Rating Curve= 0 ,0
Exp/Cntr(USF)=0,0
Exp/Cntr=0.3,0.1

Type RM Length L Ch R = 1 ,323532  ,774.1,776.1,752.3
XS GIS Cut Line= 3
2279022.83345178578691.455624162 2279443.6386406578770.005926074
2280447.96035791578012.556586206
#Sta/Elev= 30
       0 3816.08   123.4 3804.97   135.6 3797.37   168.2 3756.37   192.6 3732.89
     213  3727.5   237.4  3710.3   294.1 3707.75   359.4 3676.54   371.7 3675.51
   427.8 3650.38     509 3623.62     544 3617.35   623.3 3610.88   635.4 3603.61
   664.2  3601.6   688.9 3590.15   774.9 3588.73   794.5 3590.14   811.8 3596.59
   829.6 3598.03   980.3 3594.12  1011.7 3598.94  1043.1 3594.87  1097.4 3595.02
    1293 3651.35  1517.2  3695.9    1592 3716.93  1631.2 3724.19    1686 3744.99
#Mann= 9 ,-1,0
       0     .12       0      70      .1       0     370     .12       0
  458.07      .1       0  598.07     .06       0   688.9    .045       0
   794.5     .12       0  948.07      .1       0 1338.07     .12       0
#XS Ineff= 2 , 0
                         1013.72         3618.79
Permanent Ineff=
       F       F
Bank Sta=688.9,794.5
XS Rating Curve= 0 ,0
Exp/Cntr(USF)=0,0
Exp/Cntr=0.3,0.1

Type RM Length L Ch R = 1 ,322756  ,531.4,535.3,533.2
XS GIS Cut Line= 3
2279808.33647091579802.3813226362280010.32296154579207.643322443
2280807.04745236578511.912076934
#Sta/Elev= 30
       0  3858.4    22.9 3853.24    68.9 3835.92   106.9 3811.51   132.2 3810.18
     166 3798.68   267.4 3746.61   356.1 3709.39   401.3 3700.67   499.1 3668.22
   568.4  3651.8   730.4 3604.21   747.4 3596.19   811.1  3591.9   996.7 3592.69
  1022.4 3587.09  1057.5 3585.58  1098.9 3587.06  1119.1 3599.24  1140.4 3599.05
  1155.6 3608.95  1209.5  3624.9  1300.8 3638.46  1416.5 3673.71  1469.6  3681.8
  1506.8  3693.6    1561 3717.57  1629.2 3737.22  1668.7 3753.65  1685.8 3764.22
#Mann= 11 ,-1,0
       0     .12       0      70      .1       0     180     .12       0
     200      .1       0     390     .12       0     490      .1       0
   728.1     .06       0   878.1      .1       0  1022.4    .045       0
  1098.9      .1       0  1328.1     .12       0
Bank Sta=1022.4,1098.9
XS Rating Curve= 0 ,0
Exp/Cntr(USF)=0,0
Exp/Cntr=0.3,0.1

Type RM Length L Ch R = 1 ,322221  ,654.9,653.7,651.3
XS GIS Cut Line= 2
2279886.88677282579864.0994169952281087.58424491579016.878303513
#Sta/Elev= 30
       0 3856.12   119.1 3794.41   199.3    3757   285.5 3707.95   324.2  3695.6
   361.8 3676.22   398.1 3661.29   450.8 3643.81   476.4 3640.57   520.5 3628.49
   579.2 3608.56   602.9  3605.8   634.5  3593.4   677.5 3592.67   691.8 3587.16
   714.8 3591.31   726.3 3584.98   818.2 3584.07   823.8 3584.75   848.5 3587.91
     917  3603.7   955.9 3601.43     966 3609.02  1024.7 3616.01  1119.5 3642.61
  1202.8 3671.75  1248.7 3683.84  1267.8 3693.27  1347.8 3721.81  1469.5 3782.82
#Mann= 8 ,-1,0
       0      .1       0     110     .12       0     350      .1       0
     590     .06       0     710      .1       0   726.3    .045       0
   823.8      .1       0    1070     .12       0
Bank Sta=726.3,823.8
XS Rating Curve= 0 ,0
Exp/Cntr(USF)=0,0
Exp/Cntr=0.3,0.1

Type RM Length L Ch R = 1 ,321567  ,689.6,687.8,685.3
XS GIS Cut Line= 2
2280217.92018802580453.2266813372281435.44986766579538.676737644
#Sta/Elev= 30
       0 3839.67    93.3 3832.92     120  3826.4   147.3 3810.57   193.1 3794.99
   207.9 3786.85   224.5 3783.11   299.8 3739.91     323 3721.73   341.6 3702.38
   355.9 3700.23   435.9 3659.34   498.1 3637.58   612.8 3604.98   658.7 3595.31
   693.2 3594.44   723.2 3583.67   748.2  3582.8   825.9 3583.56   848.3 3585.08
   861.6 3589.56   898.7 3591.41   952.5  3588.1   988.4 3598.84  1004.4 3597.47
    1113 3621.83  1253.5  3659.6  1407.2 3714.59  1468.6 3725.19  1522.8 3758.47
#Mann= 9 ,-1,0
       0      .1       0     560     .06       0     710      .1       0
   723.2    .045       0   825.9     .12       0     870    .025       0
     930     .12       0    1030      .1       0    1170     .12       0
Bank Sta=723.2,825.9
XS Rating Curve= 0 ,0
Exp/Cntr(USF)=0,0
Exp/Cntr=0.3,0.1

Type RM Length L Ch R = 1 ,320879  ,899.3,882.1,866.7
XS GIS Cut Line= 2
  2280745.329358580941.3607003632281850.64432063580049.253700074
#Sta/Elev= 30
       0 3780.91    76.7 3758.08   135.8 3733.72   173.3 3711.82   218.3 3693.06
   252.5 3686.34   337.8  3652.9   350.6 3650.11   466.3 3603.54     492  3602.9
   507.4 3596.95   554.4 3588.01   625.1 3586.39   649.9 3581.23   726.3 3581.16
   733.6 3581.17   790.6 3584.85   826.1 3582.43   851.8 3587.57   872.8 3586.81
   892.5 3593.96   906.7 3593.45   923.8 3600.16   986.3 3613.89  1108.8 3635.48
  1159.9 3651.84  1175.6  3653.8  1299.5 3704.55    1376 3727.22  1420.4 3751.56
#Mann= 6 ,-1,0
       0      .1       0     400     .06       0     530      .1       0
   649.9    .045       0   733.6      .1       0     910     .12       0
Bank Sta=649.9,733.6
XS Rating Curve= 0 ,0
Exp/Cntr(USF)=0,0
Exp/Cntr=0.3,0.1

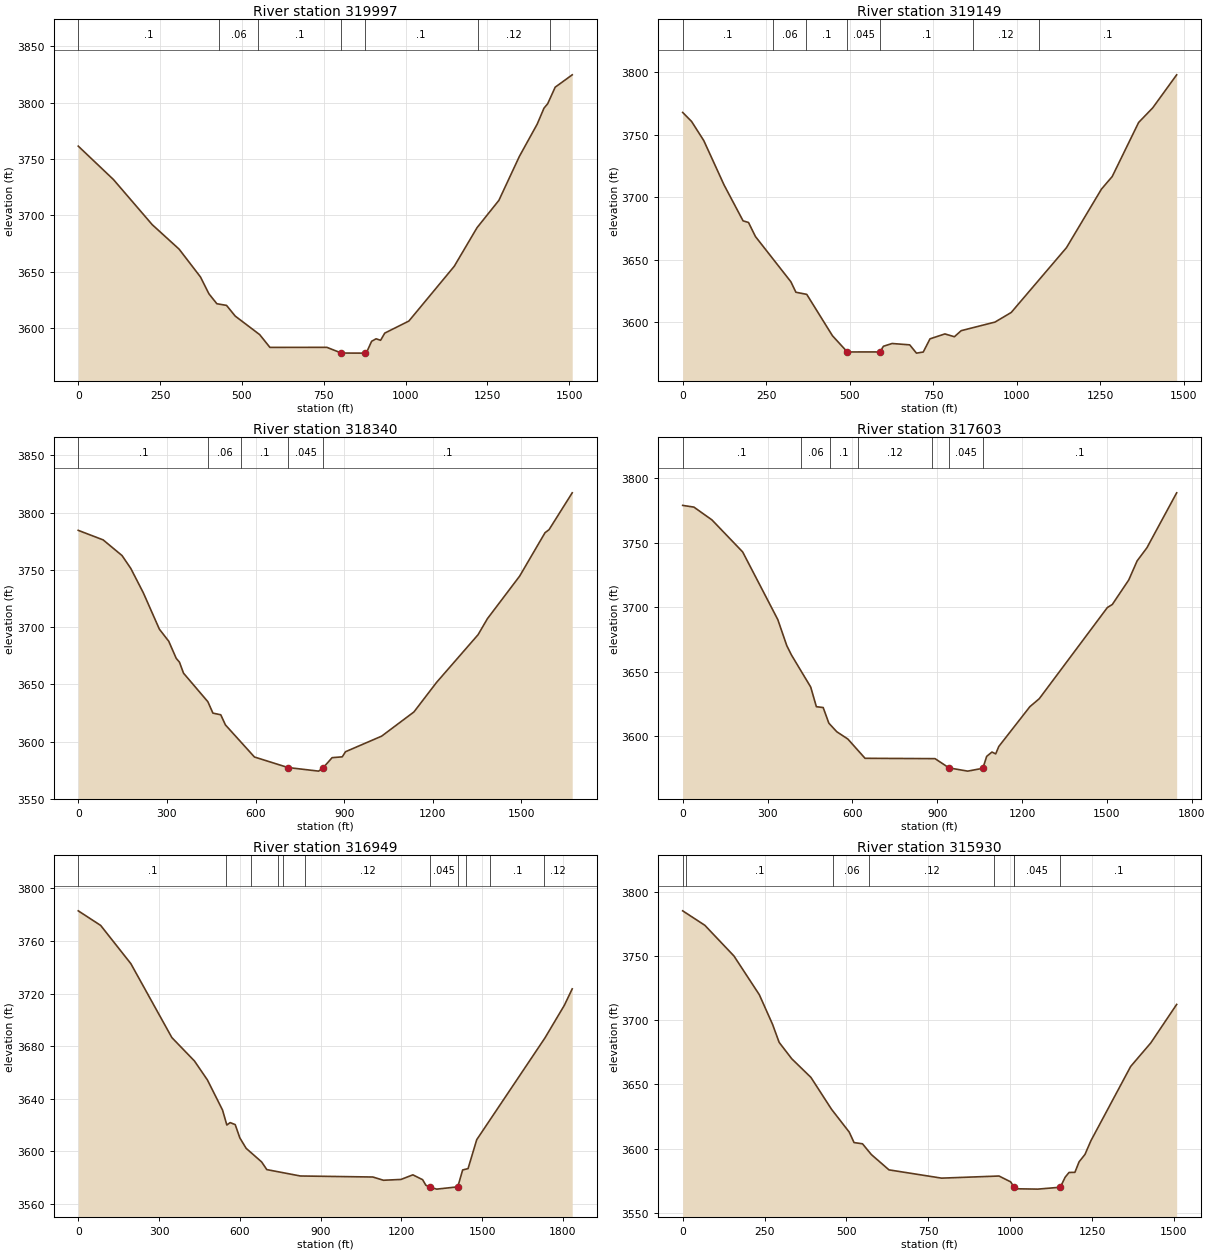
Type RM Length L Ch R = 1 ,319997  ,860.1,848.1,827.6
XS GIS Cut Line= 2
2281631.82562244 581687.58856853 2282355.6105472580363.454907723
#Sta/Elev= 30
       0 3761.39   107.6 3731.73     226 3691.71   308.2 3669.98   373.4 3645.31
   399.3 3630.34   423.5 3621.56     453  3620.1   479.5 3610.62   554.3 3594.17
   585.6 3582.83   759.6 3582.88   803.7 3577.82   868.1 3577.75   874.5 3577.89
   883.3 3579.98   896.2 3588.25   909.9 3590.47   923.6 3589.13   936.4 3595.51
  1010.1 3606.23  1148.6 3654.78  1218.3 3689.06    1285 3713.27  1347.5 3752.23
  1402.1 3780.95  1422.7 3795.04  1434.1 3799.02  1456.9 3813.64    1509 3824.63
#Mann= 7 ,-1,0
       0      .1       0     430     .06       0     550      .1       0
   803.7    .045       0   874.5      .1       0    1220     .12       0
    1440      .1       0
Bank Sta=803.7,874.5
XS Rating Curve= 0 ,0
Exp/Cntr(USF)=0,0
Exp/Cntr=0.3,0.1

Type RM Length L Ch R = 1 ,319149  ,785,809.2,825.5
XS GIS Cut Line= 3
2282697.08819294581867.563248267 2282847.7157959580944.554688871
2282780.38696569580405.924047186
#Sta/Elev= 30
       0  3767.7    26.7 3760.46    63.2 3745.16     124 3709.61   180.7    3681
     197 3679.69   217.8 3668.41   323.7  3632.3   338.8 3623.89   371.2  3622.2
   448.2 3589.08   492.6 3576.14   590.4 3576.15   600.6 3580.68   626.6  3582.9
   679.3 3581.81   699.5  3575.2   719.8 3576.07     740 3586.62   784.6 3590.56
     813 3588.31   833.3 3593.16   934.6 3600.04     983 3607.71  1148.2  3659.5
    1253 3706.39  1285.2 3716.45  1364.2 3759.67  1406.2 3771.31    1478 3797.78
#Mann= 7 ,-1,0
       0      .1       0     270     .06       0     370      .1       0
   492.6    .045       0   590.4      .1       0     870     .12       0
 1065.22      .1       0
Bank Sta=492.6,590.4
XS Rating Curve= 0 ,0
Exp/Cntr(USF)=0,0
Exp/Cntr=0.3,0.1

Type RM Length L Ch R = 1 ,318340  ,707.6,736.9,747.4
XS GIS Cut Line= 2
2283214.05313239582091.5615497932283999.55615151580615.938021013
#Sta/Elev= 30
       0 3784.46    84.3 3776.13   148.2 3762.45   177.8 3751.22   220.2 3729.94
   274.6 3698.13   306.3 3687.58   331.6 3672.64   342.6  3669.3   356.2 3659.74
   438.7 3634.75   455.8  3624.8   482.4 3623.34   498.2 3614.47   596.3 3586.47
   709.6 3577.28   813.6 3574.13   828.7 3577.03   859.1 3585.88   893.5 3586.62
   904.5 3591.08  1026.8  3604.7    1136 3625.82  1212.6 3651.63  1353.1 3693.31
  1384.8 3707.32  1493.8 3744.49  1579.6 3782.38  1593.2 3785.03  1671.7 3817.24
#Mann= 5 ,-1,0
       0      .1       0     440     .06       0     550      .1       0
   709.6    .045       0   828.7      .1       0
Bank Sta=709.6,828.7
XS Rating Curve= 0 ,0
Exp/Cntr(USF)=0,0
Exp/Cntr=0.3,0.1

Type RM Length L Ch R = 1 ,317603  ,606.8,653.8,677.7
XS GIS Cut Line= 3
2283296.56195021582088.2571099022283926.05901639582042.699661316
2284737.68283075581276.982461159
#Sta/Elev= 30
       0 3778.76    39.7 3777.44   103.5 3767.52   212.2  3742.7   336.5 3690.28
   368.1 3670.18   384.6 3662.93   452.8 3638.07   472.8 3622.86   496.9 3622.19
     517 3610.08     545 3603.45   584.2  3597.8     645 3582.88   892.5 3582.62
   942.1 3575.44    1008 3572.95 1061.653575.149  1075.1 3584.37  1093.8 3587.72
    1107 3586.31    1118 3592.05  1227.9 3622.87    1261 3629.01  1501.9 3699.64
  1519.4 3702.02  1577.6 3721.02  1607.1 3735.75  1641.8 3745.93    1747 3788.49
#Mann= 7 ,-1,0
       0      .1       0     420     .06       0     520      .1       0
     620     .12       0  881.14      .1       0   942.1    .045       0
 1061.65      .1       0
Bank Sta=942.1,1061.65
XS Rating Curve= 0 ,0
Exp/Cntr(USF)=0,0
Exp/Cntr=0.3,0.1

Type RM Length L Ch R = 1 ,316949  ,975,1018.8,1025.8
XS GIS Cut Line= 3
2283169.16724558582366.4876064862283808.79113258582405.762757442
2284997.22880701582290.007943264
#Sta/Elev= 30
       0 3782.87    83.2  3771.8   195.4 3742.72   347.7 3686.53   431.8 3668.69
   479.9 3654.28     536 3631.42     552 3620.03   564.2 3621.88   583.1 3620.35
   600.1 3610.33   623.7 3602.32   681.1    3592   700.5 3586.14   825.1 3581.29
  1094.3 3580.51  1133.7 3578.04  1198.8 3578.66    1243 3582.16  1279.2 3578.47
  1291.3 3574.26  1307.3 3572.75  1331.5  3571.3  1409.8 3573.04  1427.9 3585.87
    1448  3586.9  1480.2 3608.89  1733.4 3686.18  1805.7 3711.07  1834.9 3723.54
#Mann= 11 ,-1,0
       0      .1       0     550     .06       0  640.83      .1       0
  740.83     .12       0  760.83      .1       0  840.83     .12       0
  1307.3    .045       0  1409.8      .1       0 1440.83    .025       0
 1530.83      .1       0 1730.83     .12       0
Bank Sta=1307.3,1409.8
XS Rating Curve= 0 ,0
Exp/Cntr(USF)=0,0
Exp/Cntr=0.3,0.1

Type RM Length L Ch R = 1 ,315930  ,546.2,522.7,505.4
XS GIS Cut Line= 2
2283012.06664176 582652.635134882284353.03251012583342.755644538
#Sta/Elev= 30
       0 3785.29    67.6 3774.04   156.6 3750.09   234.1 3719.89   274.5 3696.79
   294.5  3682.8     333 3670.02   391.5 3655.51   454.5 3630.65   508.5 3612.88
   523.2 3604.72     549 3603.77   575.9 3595.42   629.9 3583.45   790.5 3577.01
   965.8 3578.66  1001.4  3574.1  1010.3 3570.46  1021.3 3568.71  1084.3 3568.45
  1152.9 3569.93  1167.7 3577.75  1179.6 3581.44  1197.4 3581.52  1210.3 3589.76
  1228.2 3595.48  1246.2  3606.1  1367.7 3664.04  1429.1 3682.37  1508.1 3712.36
#Mann= 8 ,-1,0
       0     .12       0      10      .1       0     460     .06       0
     570     .12       0     950      .1       0    1010     .12       0
  1010.3    .045       0  1152.9      .1       0
Bank Sta=1010.3,1152.9
XS Rating Curve= 0 ,0
Exp/Cntr(USF)=0,0
Exp/Cntr=0.3,0.1

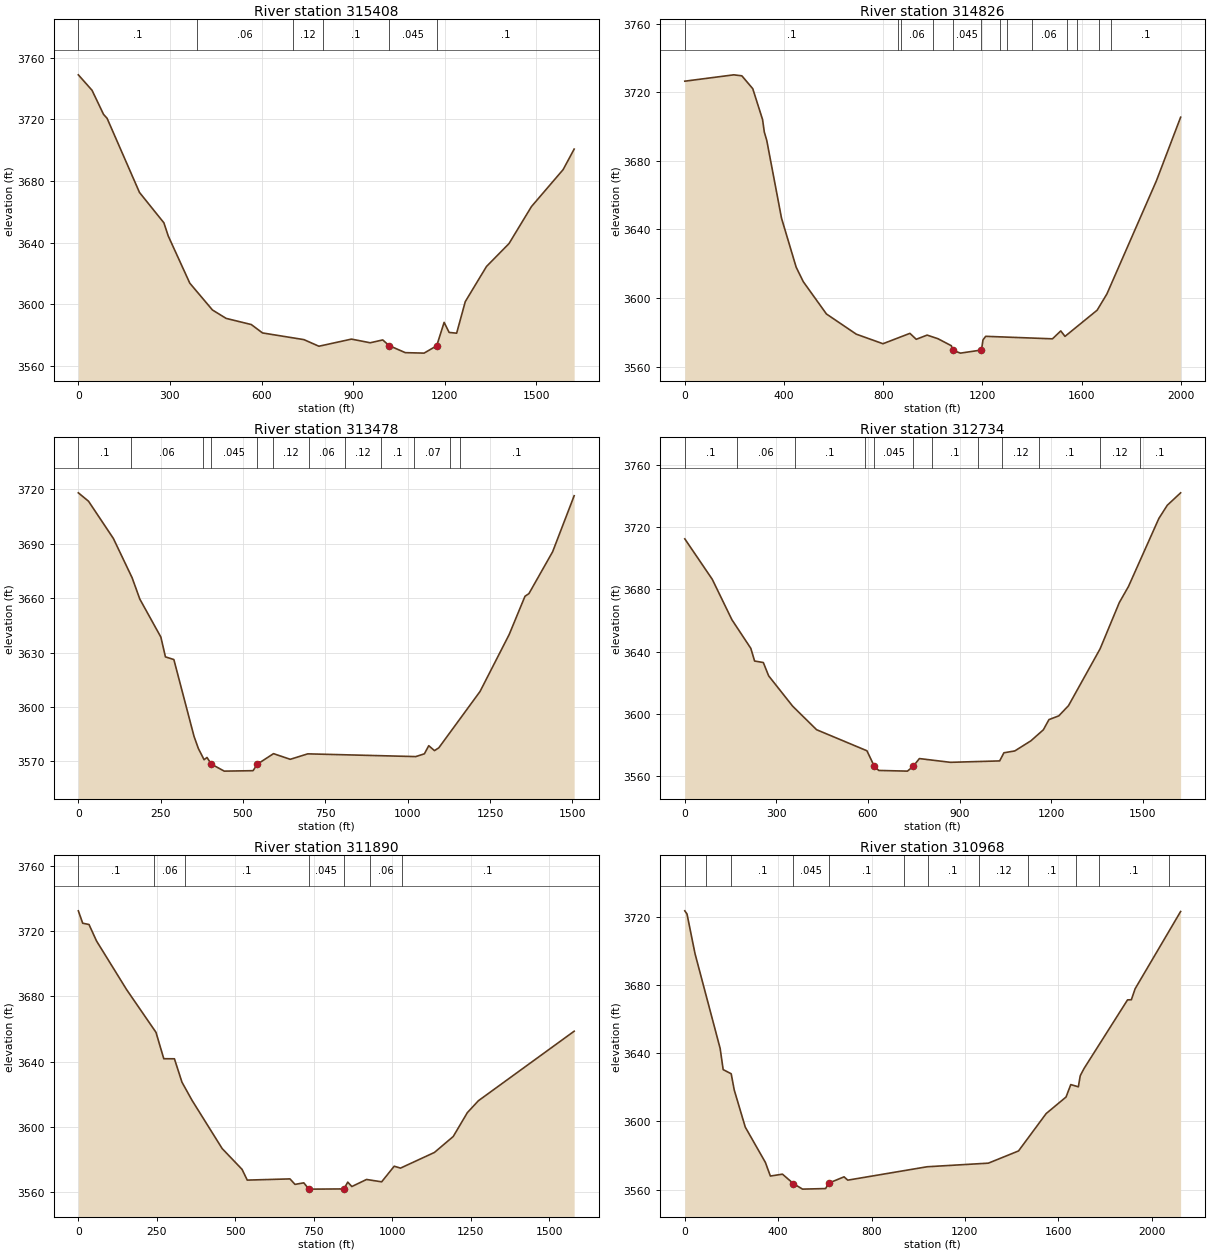
Type RM Length L Ch R = 1 ,315408  ,644.1,581.4,526.5
XS GIS Cut Line= 4
2282690.01401185583221.5661554492283056.95252856583449.359625705
2283876.11996279583634.5139087842284201.54264214583499.856248363
#Sta/Elev= 30
       0 3748.85    44.9 3738.82    82.6  3723.2    94.2 3720.65   200.3 3672.56
   280.3 3652.86   294.4 3644.37   365.1 3613.72   439.3 3596.33   484.1 3590.88
   566.4 3586.89   603.3 3581.44   738.8 3577.11   787.9 3572.82   894.5 3577.44
     956 3575.06     997 3576.91  1017.5 3573.26  1070.8 3568.66  1132.4 3568.35
  1173.7 3573.11    1198  3588.3  1214.4 3581.78    1239 3581.28  1267.3 3601.75
  1336.7 3624.53  1410.6 3639.42  1483.9 3663.37  1587.8 3687.38  1623.9 3700.68
#Mann= 6 ,-1,0
       0      .1       0     390     .06       0   701.9     .12       0
   801.9      .1       0  1017.5    .045       0  1173.7      .1       0
Bank Sta=1017.5,1173.7
XS Rating Curve= 0 ,0
Exp/Cntr(USF)=0,0
Exp/Cntr=0.3,0.1

Type RM Length L Ch R = 1 ,314826  ,1414.1,1348.8,1268.3
XS GIS Cut Line= 3
2282888.63045304584953.0368337392284134.21381193583780.393040906
 2284274.4822082583527.909927617
#Sta/Elev= 30
       0 3726.37   197.7 3730.08   230.1  3729.5   274.1    3722   313.7 3703.97
   320.7 3696.69   330.7 3691.74   390.1 3646.47   449.1 3617.92   477.8 3609.47
   571.2 3590.63   691.6 3578.85   799.2 3573.28   907.9 3579.33   933.3 3575.87
   977.3 3578.31  1021.2 3576.19  1074.9 3572.12 1080.69 3569.49  1111.7  3567.8
  1196.5 3569.62  1202.5 3575.48  1213.5  3577.6  1482.7 3576.14  1516.3 3580.75
  1533.3 3577.57  1662.9 3592.83  1702.4 3602.33    1902  3668.3  1999.6 3705.36
#Mann= 13 ,-1,0
       0      .1       0     860     .07       0     870     .06       0
    1000      .1       0 1080.69    .045       0  1196.5     .06       0
    1270     .12       0    1300     .07       0    1400     .06       0
    1540     .12       0    1580      .1       0    1670     .12       0
 1720.72      .1       0
Bank Sta=1080.69,1196.5
XS Rating Curve= 0 ,0
Exp/Cntr(USF)=0,0
Exp/Cntr=0.3,0.1

Type RM Length L Ch R = 1 ,313478  ,753.7,743.9,735.9
XS GIS Cut Line= 3
2284863.60947255584902.5402110822284375.47545352583797.225248459
2284381.08618937583499.856248363
#Sta/Elev= 30
       0 3718.12    30.9  3713.5   106.4 3692.95   163.3 3671.28   186.7 3659.52
   250.7 3638.51   264.5 3627.62   290.1 3626.15   351.3  3583.8   364.4 3577.12
   381.9 3570.89   390.7 3572.12     404 3568.45   443.1 3564.59   530.6 3564.83
   543.5 3568.42   592.7 3574.23   643.6 3571.11   696.7 3574.12  1024.7 3572.61
  1050.9 3574.14  1064.1 3578.62  1081.5 3575.91  1094.7 3577.45  1219.9 3608.54
  1308.4 3639.96  1356.4 3661.06  1368.4 3662.53  1440.4 3685.64  1505.7 3716.51
#Mann= 12 ,-1,0
       0      .1       0     160     .06       0     380      .1       0
     404    .045       0   543.5      .1       0     590     .12       0
     700     .06       0     810     .12       0     920      .1       0
    1020     .07       0    1130     .12       0    1160      .1       0
Bank Sta=404,543.5
XS Rating Curve= 0 ,0
Exp/Cntr(USF)=0,0
Exp/Cntr=0.3,0.1

Type RM Length L Ch R = 1 ,312734  ,822.1,843.5,881
XS GIS Cut Line= 2
2285564.95145391 584571.506795882284757.00549138 583163.21209731
#Sta/Elev= 30
       0  3712.6      90 3686.52   154.3 3660.49   216.2 3642.05   228.6 3633.89
   257.2 3632.91   274.6 3624.34   353.2 3604.79   431.6 3589.63   596.4 3576.07
   620.8 3565.94   635.2 3563.39     729 3562.95  747.483565.936   768.2 3571.04
   869.7 3568.62  1031.1 3569.53  1044.9 3574.77  1080.6 3575.96  1133.4 3582.49
    1174 3589.55  1192.5 3596.16  1224.7 3598.56  1256.5 3605.14    1360 3641.78
    1423 3671.63  1452.8  3681.9  1552.4 3725.77  1579.8 3734.22  1623.6 3742.26
#Mann= 12 ,-1,0
       0      .1       0     170     .06       0     360      .1       0
     590     .12       0   620.8    .045       0  747.48     .12       0
     810      .1       0     960     .07       0    1040     .12       0
    1160      .1       0    1360     .12       0    1490      .1       0
Bank Sta=620.8,747.48
XS Rating Curve= 0 ,0
Exp/Cntr(USF)=0,0
Exp/Cntr=0.3,0.1

Type RM Length L Ch R = 1 ,311890  ,853.5,921.9,994.5
XS GIS Cut Line= 2
2285924.03854836584403.1847203542285958.82030005 582824.15721214
#Sta/Elev= 30
       0 3732.27      14 3724.67      34  3723.9      58  3713.8     154 3683.98
   247.4 3657.88   272.2 3641.73   306.1 3641.69   330.1 3627.38   362.1  3616.3
   458.1 3586.75   521.5 3574.01   538.1 3567.42   674.2 3568.16   690.2  3564.8
   718.2 3565.75   734.2 3561.97   746.2  3561.9   846.2 3562.03   858.2  3566.2
   871.2 3563.49   918.1 3567.81   966.2 3566.37  1006.2 3575.92  1026.3 3574.77
  1134.3 3584.35  1194.3 3594.14  1239.2 3608.73  1274.3    3616  1579.4 3658.57
#Mann= 7 ,-1,0
       0      .1       0     240     .06       0     340      .1       0
   734.2    .045       0   846.2      .1       0     930     .06       0
    1030      .1       0
Bank Sta=734.2,846.2
XS Rating Curve= 0 ,0
Exp/Cntr(USF)=0,0
Exp/Cntr=0.3,0.1

Type RM Length L Ch R = 1 ,310968  ,798.2,771.3,752.9
XS GIS Cut Line= 3
2285991.36737857 584442.459871312287398.70877504583883.371901056
2288000.52696955 583783.67205327
#Sta/Elev= 30
       0 3723.71     9.5 3721.83    43.9  3698.5   151.5 3642.85   164.4 3630.43
   198.8 3627.99   211.8 3618.46   259.1 3596.65   345.2 3575.93   366.7  3567.9
   418.4 3569.01   465.7 3563.43   504.4 3560.22   603.4 3560.55   616.4 3563.73
   682.4 3567.44   698.1 3565.49  1038.2 3573.36  1300.7 3575.48  1429.8 3582.65
  1548.3 3604.62  1633.4 3614.33  1653.7 3621.63  1686.1 3620.33  1694.2 3626.82
  1710.4 3631.06  1896.9  3671.4  1913.2 3671.48  1929.4 3677.94  2124.3 3723.32
#Mann= 12 ,-1,0
       0      .1       0      90     .06       0     200      .1       0
   465.7    .045       0   616.4      .1       0     940     .06       0
    1040      .1       0    1260     .12       0    1470      .1       0
 1674.33     .06       0 1774.33      .1       0 2074.33     .06       0
Bank Sta=465.7,616.4
XS Rating Curve= 0 ,0
Exp/Cntr(USF)=0,0
Exp/Cntr=0.3,0.1