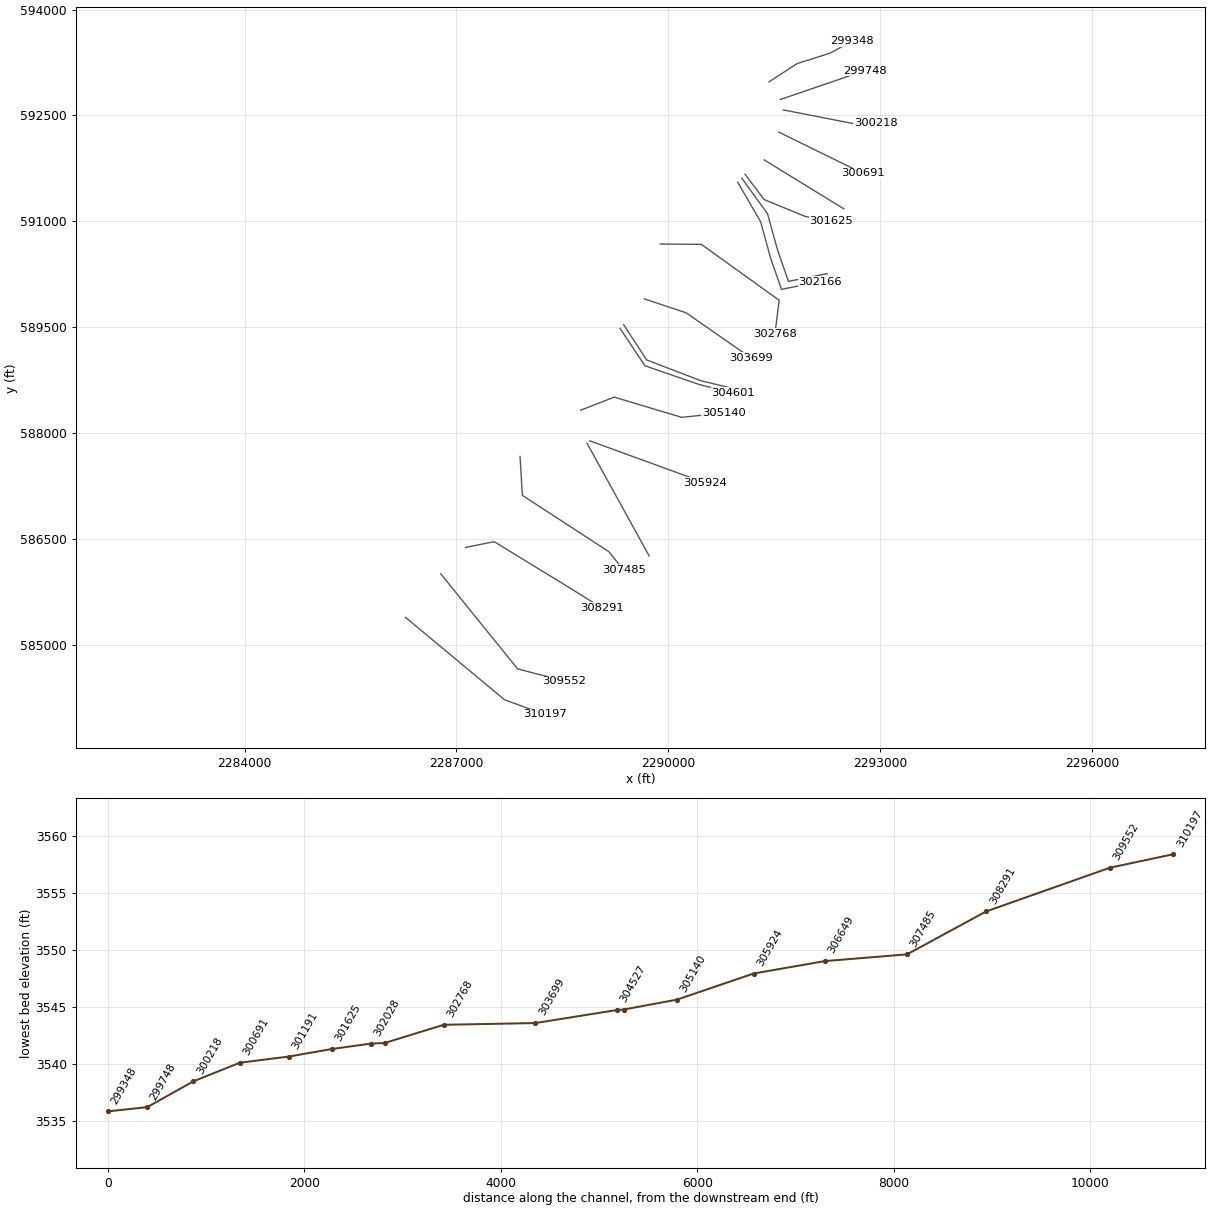
HEC-RAS study SHAVERSFK.prj: SHAVERSFK

--- SHAVERSFK.g01 (geometry) --- (continued)

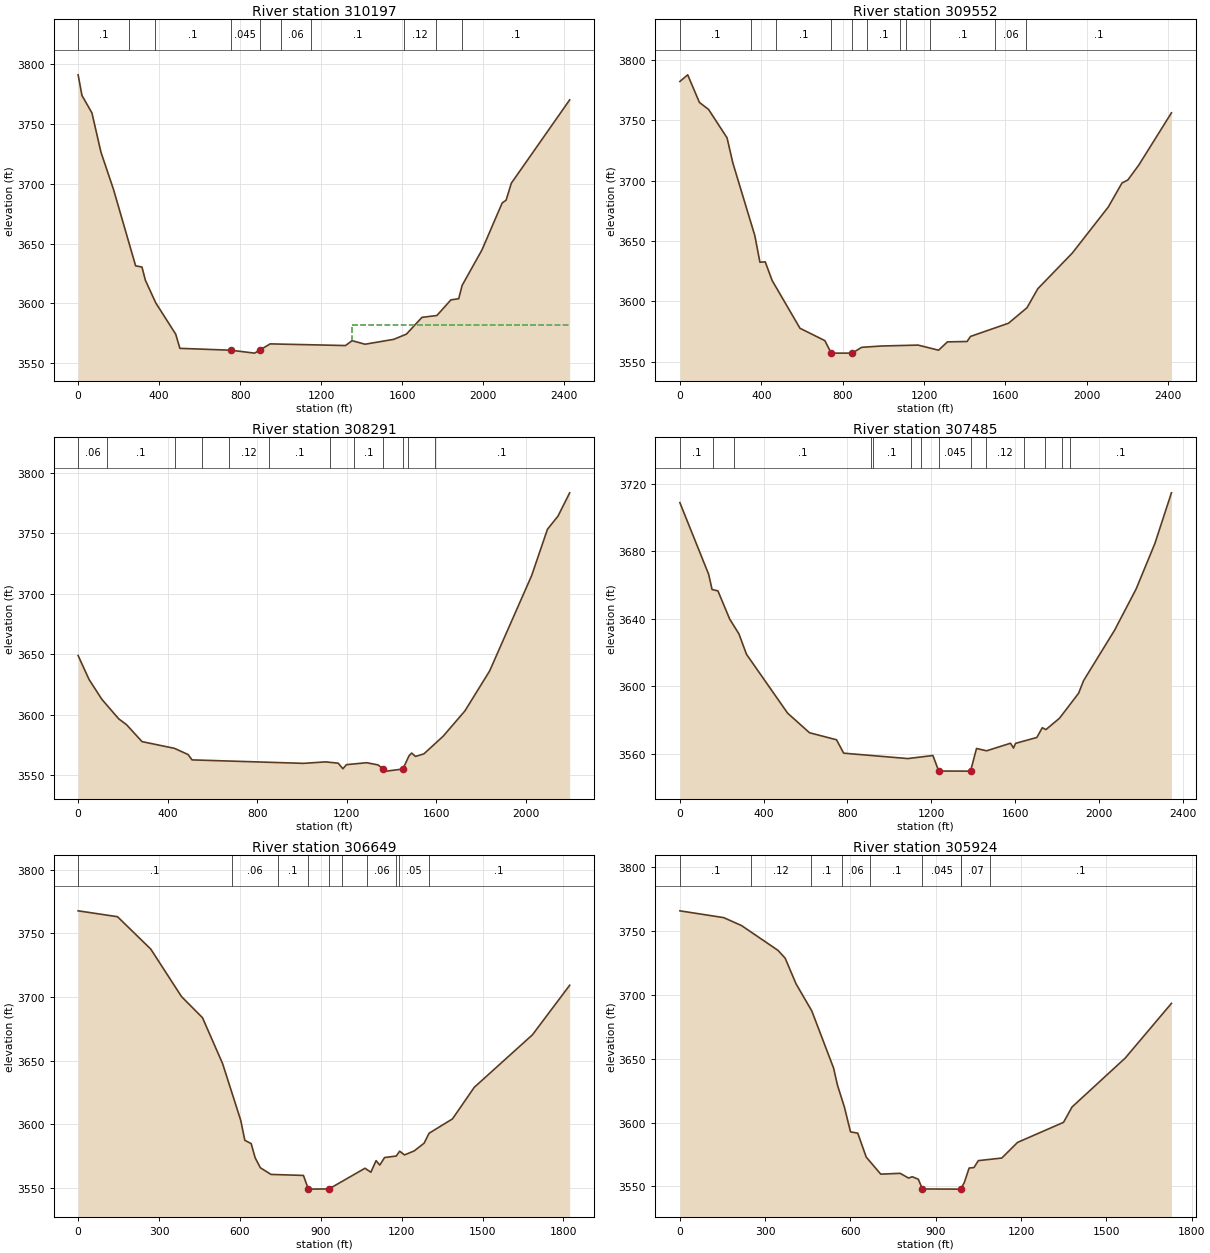
Type RM Length L Ch R = 1 ,310197  ,650,644.9,634.5
XS GIS Cut Line= 3
2286277.51490697585390.6742301082287680.19886969584223.641173125
2288246.88319062584016.043946643
#Sta/Elev= 30
       0 3791.12    19.1 3773.84    68.3 3759.25   112.7  3726.5   175.2 3695.08
   284.1 3631.39   315.4 3630.39   332.4 3619.27   383.8 3600.34   482.2  3574.2
   502.7 3562.38   752.8 3560.83   872.1 3558.38   897.6 3560.98   948.8 3566.11
  1320.8 3564.72  1353.2 3568.79  1417.4 3565.83  1559.4 3569.91  1621.7 3574.28
  1698.6 3588.29  1772.3 3589.85  1841.7 3602.94    1880 3603.86  1897.1 3615.08
  1995.1 3644.75  2094.7 3683.93  2114.3 3686.32  2139.9 3700.48  2428.2 3770.19
#Mann= 10 ,-1,0
       0      .1       0     250     .06       0     380      .1       0
   752.8    .045       0   897.6      .1       0    1000     .06       0
    1150      .1       0    1610     .12       0    1770     .06       0
 1894.69      .1       0
#XS Ineff= 2 , 0
                         1353.79          3581.9
Permanent Ineff=
       F       F
Bank Sta=752.8,897.6
XS Rating Curve= 0 ,0
Exp/Cntr(USF)=0,0
Exp/Cntr=0.3,0.1

Type RM Length L Ch R = 1 ,309552  ,1243.3,1261.3,1268.9
XS GIS Cut Line= 3
2286776.87039769586007.8551737042287865.35315276584661.278569494
2288527.41998317584487.345758117
#Sta/Elev= 30
       0 3782.05    38.4 3787.54      96 3764.69   140.8 3758.93   231.8 3735.42
   260.2 3714.66   368.3 3654.49   393.4 3632.44   419.5 3632.74   453.6 3617.26
   590.2 3577.79   712.5 3567.55   743.8 3557.22     847  3557.2   893.2    3562
     991 3563.09  1170.4 3563.86  1271.5 3559.62    1315 3566.52  1411.5 3566.82
  1428.2 3571.01  1615.1 3581.94  1705.9 3594.75  1759.2  3610.5  1928.8 3640.04
  2105.5 3678.12  2172.8 3697.98  2201.7 3700.52  2255.5 3712.85    2416 3756.07
#Mann= 11 ,-1,0
       0      .1       0     350     .06       0     470      .1       0
   743.8    .045       0     847    .025       0     920      .1       0
    1080     .06       0    1110     .07       0    1230      .1       0
    1550     .06       0    1700      .1       0
Bank Sta=743.8,847
XS Rating Curve= 0 ,0
Exp/Cntr(USF)=0,0
Exp/Cntr=0.3,0.1

Type RM Length L Ch R = 1 ,308291  ,815.4,806.4,788.8
XS GIS Cut Line= 4
2287128.14029127586381.5222577112287534.17716444586462.766160137
2288514.48268487 585862.677217032289052.55263996585528.787958274
#Sta/Elev= 30
       0    3649      49 3629.16   106.1 3612.78   181.7 3596.58   216.2 3591.82
   285.6 3577.77   430.5 3572.22   491.5 3567.08   509.1 3562.66  1007.4 3559.79
  1105.8 3561.01  1162.1 3559.96  1183.3 3555.34  1199.2 3558.72  1289.4 3560.31
  1340.3  3558.5  1363.8 3555.01  1377.9 3553.361451.3913555.107  1478.5 3565.94
  1490.4 3568.33  1507.6 3565.52  1545.4 3567.67  1631.4 3582.26  1728.5 3603.17
  1838.9 3636.19  2026.8 3715.16  2097.4 3753.48  2144.5 3764.36  2196.7 3783.62
#Mann= 12 ,-1,0
       0     .06       0     130      .1       0  434.09     .12       0
  554.09      .1       0  674.09     .12       0  854.09      .1       0
 1124.09     .12       0 1234.09      .1       0  1363.8    .045       0
1451.391      .1       0 1474.09     .07       0 1593.48      .1       0
Bank Sta=1363.8,1451.391
XS Rating Curve= 0 ,0
Exp/Cntr(USF)=0,0
Exp/Cntr=0.3,0.1

Type RM Length L Ch R = 1 ,307485  ,870.2,836,788.1
XS GIS Cut Line= 4
2287899.87390736587670.4792520692287932.68198297587118.780872177
2289155.82239847586322.0563813532289366.03317258586062.205324059
#Sta/Elev= 30
       0  3708.7   137.4  3666.2   153.6 3657.23   181.6 3656.42   237.7 3639.72
   281.8 3630.94   317.9 3618.85   514.2 3583.96   618.9 3572.33   747.8 3568.17
   781.8 3560.23  1088.3 3557.03  1207.9 3558.85  1235.7 3549.64  1387.5 3549.59
  1416.1 3563.02  1464.1 3561.63  1578.4 3566.12  1592.7 3563.29  1602.3 3566.04
    1704 3569.54    1730 3575.31  1747.4  3574.2  1812.3 3580.96  1903.5 3595.77
  1926.9 3603.16  2075.3 3633.14  2178.2 3657.58  2267.4 3684.45  2346.6 3714.52
#Mann= 14 ,-1,0
       0      .1       0     160     .06       0     260      .1       0
  912.67     .12       0  922.67      .1       0 1102.67     .12       0
 1152.67      .1       0  1235.7    .045       0  1387.5    .025       0
 1462.67     .12       0 1642.67     .06       0 1742.67      .1       0
 1822.67     .05       0 1862.67      .1       0
Bank Sta=1235.7,1387.5
XS Rating Curve= 0 ,0
Exp/Cntr(USF)=0,0
Exp/Cntr=0.3,0.1

Type RM Length L Ch R = 1 ,306649  ,681.7,725,758
XS GIS Cut Line= 2
2288848.13279533587857.1680974192289728.11745525586260.338286993
#Sta/Elev= 30
       0 3767.68   146.1 3763.06   269.5 3737.62   383.6 3700.27   461.3 3683.71
   535.9 3647.64   602.9 3603.25   618.4 3587.36   641.9 3584.78   656.6 3573.65
   675.9  3565.8   715.5 3560.56   835.8 3559.76   853.9    3549   930.5 3549.16
  1064.1 3565.41  1085.8 3562.28  1105.2 3571.39  1118.9 3567.91  1136.6 3573.81
    1180 3575.01  1192.5 3578.82  1210.5 3575.87  1246.8 3579.06  1283.4 3585.11
  1301.6 3592.89  1388.4 3604.17  1469.3 3628.99  1685.3 3670.31  1823.2  3709.2
#Mann= 10 ,-1,0
       0      .1       0     570     .06       0     740      .1       0
   853.9    .045       0   930.5      .1       0     980     .07       0
    1070     .06       0    1180      .1       0    1190     .05       0
    1300      .1       0
Bank Sta=853.9,930.5
XS Rating Curve= 0 ,0
Exp/Cntr(USF)=0,0
Exp/Cntr=0.3,0.1

Type RM Length L Ch R = 1 ,305924  ,774,783.4,801.6
XS GIS Cut Line= 2
2288888.30881495  587890.87704172290512.76413489587299.180758893
#Sta/Elev= 30
       0 3765.66   154.1 3760.34     217 3754.11   344.5 3734.81   370.2 3728.66
   408.5 3708.57   463.9 3687.37   540.5  3642.7   554.3 3629.25   578.8 3611.96
   600.1 3592.74   625.6 3591.69   655.4 3572.97   706.5 3559.63   774.6 3560.28
   804.4 3556.55   817.2 3557.61   838.5 3555.67   853.1 3548.04   987.5 3547.91
  1000.3 3553.02  1017.3 3564.39  1034.3 3564.79  1049.7  3570.2  1132.2 3572.24
  1187.6 3584.47  1349.3 3600.16  1379.2 3612.16  1566.5  3650.5  1728.9 3693.26
#Mann= 9 ,-1,0
       0      .1       0     250     .12       0     460      .1       0
     570     .06       0     670      .1       0   853.1    .045       0
   987.5      .1       0     990     .07       0    1090      .1       0
Bank Sta=853.1,987.5
XS Rating Curve= 0 ,0
Exp/Cntr(USF)=0,0
Exp/Cntr=0.3,0.1

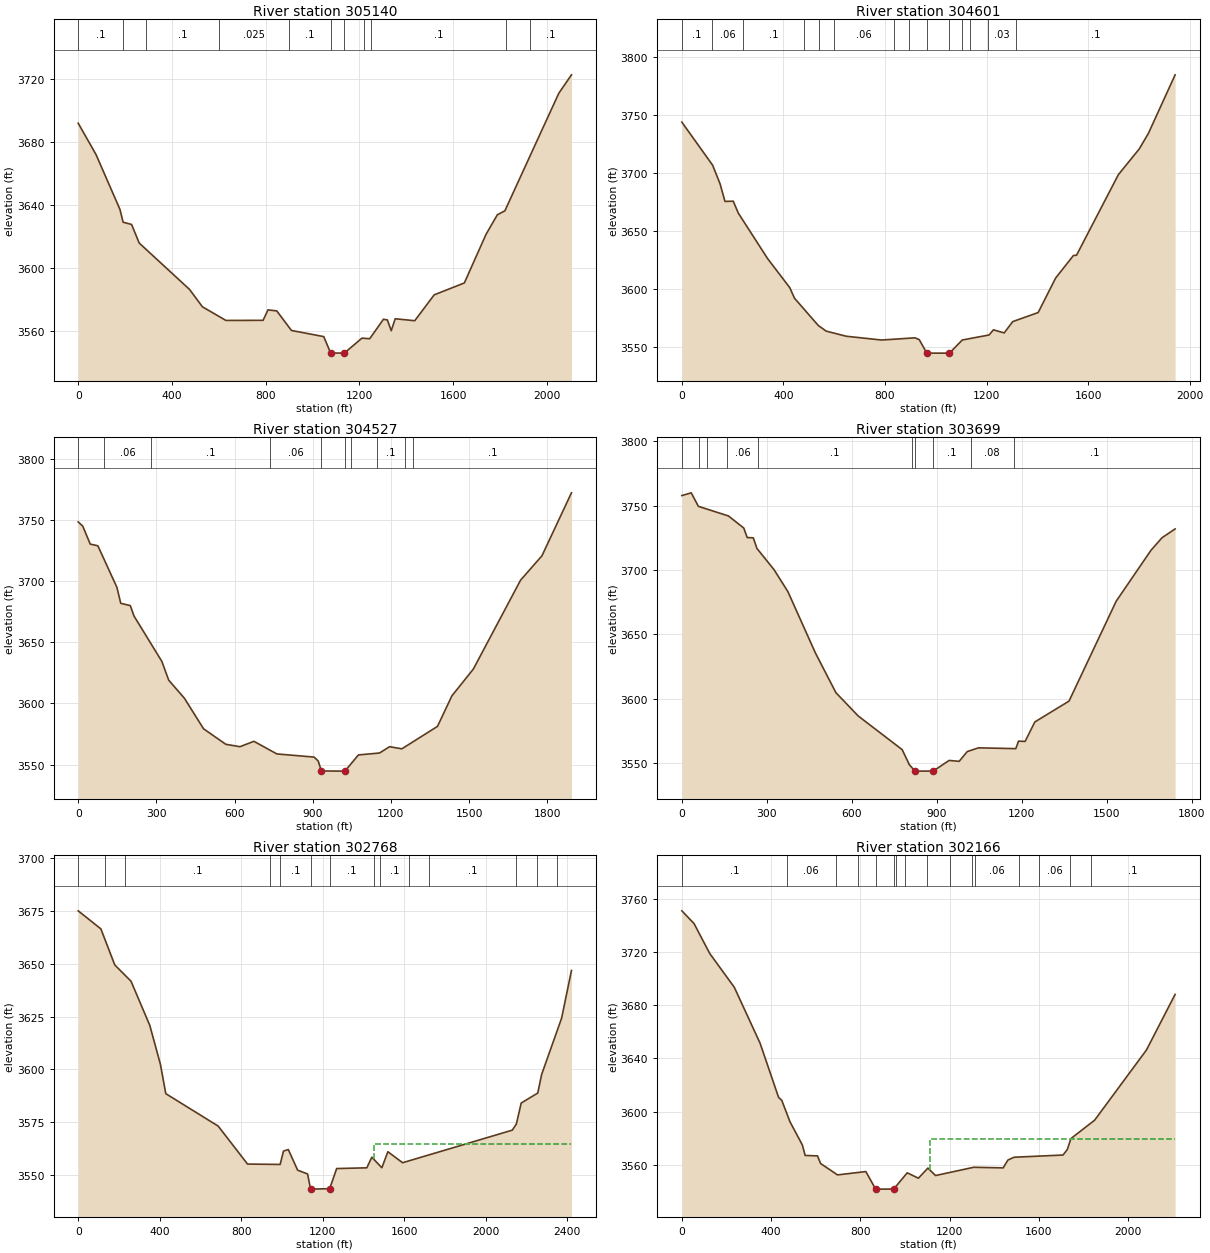
Type RM Length L Ch R = 1 ,305140  ,539.2,539.4,539.6
XS GIS Cut Line= 4
2288757.46015305588325.0890801152289234.37270038588510.243363194
2290188.19779503  588224.09583482290782.93579522588285.813929159
#Sta/Elev= 30
       0 3692.08    75.9 3672.17   178.3 3637.13   191.7 3629.02   227.8 3627.59
   260.4 3615.74   474.9 3586.24   530.2 3575.13   630.4 3566.44   789.1  3566.5
     810 3573.17   847.6  3572.5   910.2 3560.04    1048 3556.14  1077.3  3545.7
  1135.7 3545.61    1211 3555.15  1244.3 3554.81  1302.8 3567.18  1319.5 3566.76
  1336.2  3559.9  1352.9  3567.5  1436.4 3566.26  1519.5 3582.75  1648.1 3590.31
  1740.6 3621.26  1788.9 3633.73  1821.1 3636.26  2051.2 3711.14  2105.3  3722.9
#Mann= 11 ,-1,0
       0      .1       0     190     .06       0     290      .1       0
  601.59    .025       0  901.59      .1       0  1077.3    .045       0
  1135.7      .1       0 1221.59     .06       0 1251.59      .1       0
 1827.42     .12       0 1927.42      .1       0
Bank Sta=1077.3,1135.7
XS Rating Curve= 0 ,0
Exp/Cntr(USF)=0,0
Exp/Cntr=0.3,0.1

Type RM Length L Ch R = 1 ,304601  ,75,73.7,72
XS GIS Cut Line= 4
2289316.96167438 589482.57992645 2289667.9252781588954.460212769
2290442.97257228588687.0767050042290917.12864781588571.042023674
#Sta/Elev= 30
       0 3743.78   121.4 3706.63   150.6 3690.57   169.8 3675.48   202.4 3675.67
   222.6 3665.28     338  3626.1     425 3601.15   443.5 3592.06   537.1 3568.59
   568.4 3563.71   647.1 3559.31   786.3 3556.04   917.9 3557.93   934.8 3556.37
   964.4 3544.75  1053.7 3544.75  1104.1 3556.06  1209.8 3560.39  1226.8 3564.84
  1269.1 3562.16  1302.9 3571.93  1402.9 3579.71  1471.7 3609.46  1541.7 3628.85
    1554 3629.13  1718.8 3698.56  1801.1 3720.76    1837 3734.11  1942.1 3784.56
#Mann= 14 ,-1,0
       0      .1       0     120     .06       0     240      .1       0
     480     .06       0     540      .1       0     600     .06       0
   834.1      .1       0   894.1     .06       0   964.4    .045       0
  1053.7     .08       0  1104.1     .07       0  1134.1     .06       0
  1204.1     .03       0  1314.1      .1       0
Bank Sta=964.4,1053.7
XS Rating Curve= 0 ,0
Exp/Cntr(USF)=0,0
Exp/Cntr=0.3,0.1

Type RM Length L Ch R = 1 ,304527  ,833.3,827.6,816
XS GIS Cut Line= 5
2289366.90485178589536.0984178172289692.43600139  589037.3238435
2290461.61426769588742.5515389962290802.68593007588659.743973539
2290922.07594485588630.429542915
#Sta/Elev= 30
       0 3748.38    17.5  3744.9    46.2 3730.24    75.5 3728.86   148.7 3694.84
   163.3 3681.84   199.9 3680.01     214 3671.54     321  3634.4   347.4 3619.04
   407.7 3604.25   481.1 3579.31   566.6 3566.62     621 3564.67   674.3 3569.07
   762.4 3558.76   905.2 3556.18   920.9 3553.07   933.7 3544.82  1023.7  3544.7
  1075.5 3557.93  1156.5  3559.5    1195 3564.67  1242.2 3562.93    1379 3581.27
  1434.3 3606.21  1516.6 3628.12  1697.8 3700.76  1779.8 3720.65  1893.2 3772.15
#Mann= 10 ,-1,0
       0      .1       0     100     .06       0     280      .1       0
  735.61     .06       0   933.7    .045       0  1023.7     .08       0
 1045.61     .07       0 1145.61      .1       0 1255.61     .03       0
 1285.61      .1       0
Bank Sta=933.7,1023.7
XS Rating Curve= 0 ,0
Exp/Cntr(USF)=0,0
Exp/Cntr=0.3,0.1

Type RM Length L Ch R = 1 ,303699  ,932.5,931.2,929.3
XS GIS Cut Line= 3
2289660.78862504589901.7058542112290249.91588939589705.330099431
2291170.07656893589065.706212431
#Sta/Elev= 30
       0 3757.76    33.1 3759.91    58.4 3749.41   164.4 3741.94   218.6 3732.55
   230.8 3725.15   252.3 3724.92     265 3716.72   325.6 3700.14   374.6 3683.05
   471.1 3635.64   543.8  3604.6   622.7 3586.43   777.9 3560.28   803.5 3548.46
   823.5 3543.56   887.6 3543.61   943.6 3551.86   979.1 3551.17  1007.8 3558.78
  1047.6 3561.67  1179.1 3561.04  1188.8 3566.86  1211.9 3566.65  1246.3 3581.79
    1367 3597.99  1533.7 3675.71  1656.5 3715.26  1695.5 3725.02  1741.6 3731.84
#Mann= 10 ,-1,0
       0      .1       0      60     .06       0      90      .1       0
     160     .06       0     270      .1       0  810.99    .025       0
   823.5    .045       0   887.6      .1       0 1020.99     .08       0
 1170.99      .1       0
Bank Sta=823.5,887.6
XS Rating Curve= 0 ,0
Exp/Cntr(USF)=0,0
Exp/Cntr=0.3,0.1

Type RM Length L Ch R = 1 ,302768  ,630.7,602.3,575.6
BEGIN DESCRIPTION:
Structure XS 4
END DESCRIPTION:
XS GIS Cut Line= 4
2289885.02202184590678.782571454 2290466.1771913590674.802056595
2291568.77980732589882.6795995982291509.07208443589405.017816484
#Sta/Elev= 30
       0 3674.97   111.2 3666.44   179.5 3649.39   259.2 3641.69   351.2 3620.84
   403.2  3602.5   429.8 3588.54   686.8 3573.21   830.8 3555.26   990.8 3555.08
  1007.2 3561.38  1030.9 3562.13  1076.7 3552.36  1125.5 3550.58  1139.8 3543.54
  1140.2 3543.41  1233.8 3543.62  1268.2 3553.14    1416 3553.48  1440.6  3558.5
  1489.9 3553.52  1519.4 3561.09  1591.7 3555.89  2129.8 3571.29  2149.9 3574.21
  2173.6 3584.11  2254.8 3588.83  2273.9 3597.62  2371.7 3624.18  2420.2 3646.76
#Mann= 14 ,-1,0
       0      .1       0     130     .06       0     230      .1       0
  941.17    .025       0  991.17      .1       0  1139.8    .045       0
  1233.8      .1       0 1451.17     .08       0 1481.17      .1       0
 1621.17     .07       0 1721.17      .1       0 2148.81     .07       0
 2248.81     .06       0 2348.81      .1       0
#XS Ineff= 2 , 0
          998.19 3557.14 1449.46         3564.62
Permanent Ineff=
       T       F
Bank Sta=1139.8,1233.8
XS Rating Curve= 0 ,0
Exp/Cntr(USF)=0,0
Exp/Cntr=0.3,0.1

Type RM Length L Ch R = 1 ,302166  ,144.1,138.2,138.4
BEGIN DESCRIPTION:
Structure XS 3
END DESCRIPTION:
XS GIS Cut Line= 5
2290980.77659686591556.7544328532291306.12104232 590994.26460568
2291447.31382766590480.6429258372291601.77265884590037.040326679
 2292149.9362069590146.325211148
#Sta/Elev= 30
       0 3750.96    54.7 3741.39   125.1 3718.89   235.2 3693.49   350.7 3651.47
   433.9 3610.66   447.7 3608.64   484.7 3592.45   540.2 3575.01   552.6 3567.13
   608.2 3566.78   621.9 3561.07   697.9  3552.5   824.8 3555.01   868.8 3541.81
   949.6 3541.86  1010.3 3554.07  1060.3 3550.02  1103.1 3557.63  1137.2 3552.02
  1308.4 3558.23  1440.3 3557.77  1461.5 3563.65  1489.2 3565.77  1708.8 3567.44
  1728.1 3571.65  1744.4 3579.84  1850.4 3593.61  2082.9 3646.42  2211.2 3688.17
#Mann= 16 ,-1,0
       0      .1       0     470     .06       0   689.8      .1       0
   789.8     .12       0   868.8    .045       0   949.6      .1       0
   959.8     .08       0   999.8      .1       0  1099.8     .06       0
 1202.48      .1       0 1302.48     .07       0 1312.48     .06       0
 1512.48      .1       0 1602.48     .06       0  1742.2     .08       0
  1832.2      .1       0
#XS Ineff= 2 , 0
                         1111.91         3579.14
Permanent Ineff=
       F       F
Bank Sta=868.8,949.6
XS Rating Curve= 0 ,0
Exp/Cntr(USF)=0,0
Exp/Cntr=0.3,0.1

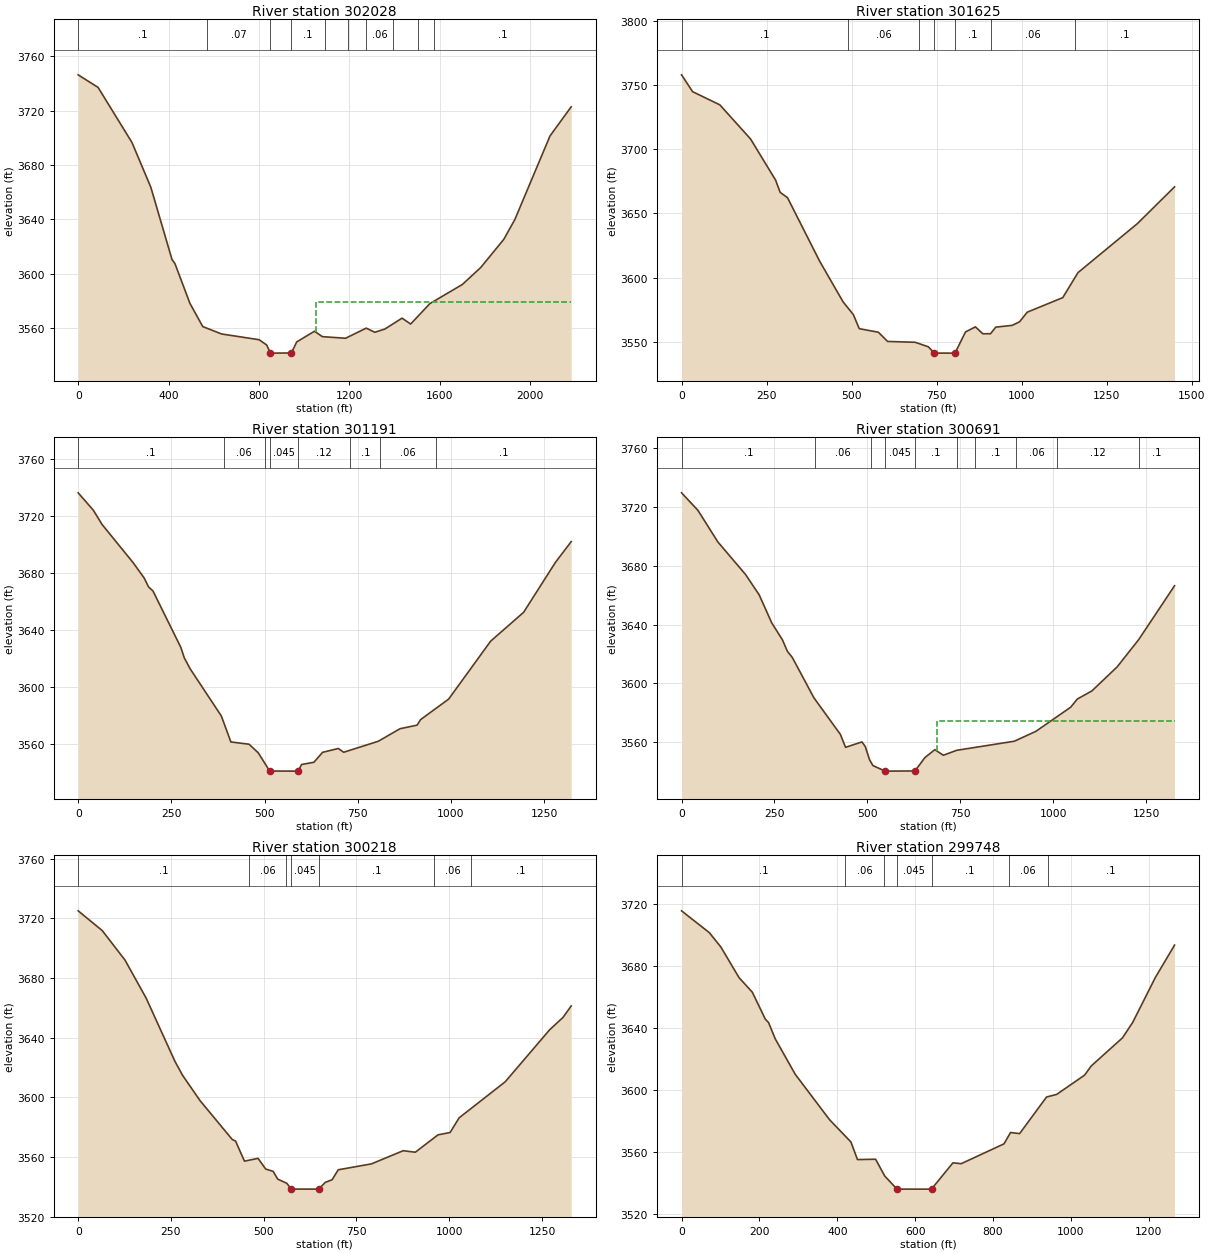
Type RM Length L Ch R = 1 ,302028  ,356.7,402.3,432.5
BEGIN DESCRIPTION:
Structure XS 2
END DESCRIPTION:
XS GIS Cut Line= 5
2291040.48308961591609.4162223782291404.71825606591107.423072281
2291545.91104139590593.8013924382291700.36987257 590150.19879328
2292248.53342063590259.483677749
#Sta/Elev= 30
       0 3746.33      88 3737.08   237.9 3696.63   321.5 3663.66   415.2 3610.56
   428.6  3607.4   494.5 3578.33   551.2 3561.28   634.6 3555.84   800.9 3551.61
   834.1 3547.72   850.7 3541.79   852.6 3541.76   943.7 3541.88   966.9 3549.97
  1045.7 3557.86  1080.4 3553.88  1183.2 3552.69  1274.5 3560.12  1312.7  3557.1
  1356.9 3559.45  1433.1 3567.47  1471.2 3563.15  1555.9 3578.11  1699.9 3592.21
  1781.5 3604.73  1883.4 3625.41  1932.4 3640.01  2087.9  3701.4  2181.6 3722.82
#Mann= 10 ,-1,0
       0      .1       0     570     .07       0   850.7    .045       0
   943.7      .1       0 1090.21     .07       0 1192.89      .1       0
 1272.89     .06       0 1392.89      .1       0 1502.89     .06       0
 1572.89      .1       0
#XS Ineff= 2 , 0
                         1052.35         3579.31
Permanent Ineff=
       F       F
Bank Sta=850.7,943.7
XS Rating Curve= 0 ,0
Exp/Cntr(USF)=0,0
Exp/Cntr=0.3,0.1

Type RM Length L Ch R = 1 ,301625  ,440.9,434.7,429.2
BEGIN DESCRIPTION:
Structure XS 1
END DESCRIPTION:
XS GIS Cut Line= 4
2291085.43412754591667.0977590662291356.10913797 591308.85142173
2291937.26430743591070.0205301732292303.47167448591002.351777565
#Sta/Elev= 30
       0 3757.92    32.5 3744.82   112.7 3734.53   202.9 3707.99   276.6 3675.96
   289.9 3666.45   311.7 3662.24     406  3612.9     475 3581.21   505.3 3571.22
   522.6 3560.33   578.8 3557.53     606 3550.37   686.9 3549.74   725.9 3546.19
   743.1 3541.31   803.7 3541.28   804.3 3541.39     835 3557.78   864.2 3561.72
   885.9 3556.36   908.6 3556.37   923.9  3561.5   972.4  3562.9     994 3565.68
  1016.4 3573.14    1121 3584.49  1165.7 3603.93  1340.6 3642.14  1449.7 3670.71
#Mann= 7 ,-1,0
       0      .1       0     489     .06       0     699      .1       0
   743.1    .045       0   804.3      .1       0     909     .06       0
 1157.32      .1       0
Bank Sta=743.1,804.3
XS Rating Curve= 0 ,0
Exp/Cntr(USF)=0,0
Exp/Cntr=0.3,0.1

Type RM Length L Ch R = 1 ,301191  ,497.3,499.5,504.8
XS GIS Cut Line= 2
2291357.70491831591870.2294903172292484.19062349591177.619904802
#Sta/Elev= 30
       0 3735.95    40.5 3723.79    63.9  3713.8   147.1 3687.03   176.6 3676.33
   188.7 3669.94   200.6 3667.06   275.2 3627.55   284.6 3620.16   299.9 3612.61
   383.9 3579.36   409.6 3561.09   458.4  3559.5   483.1 3553.45   513.7 3540.67
   589.8 3540.62   599.2 3545.28   632.1 3546.81   655.6 3553.82   697.8 3556.51
   712.1 3553.86   805.1 3561.59   863.3 3570.39   909.1 3572.89   918.5  3576.8
   993.7 3591.17  1106.4 3631.86  1194.7 3652.06  1280.1 3687.12  1322.4 3701.71
#Mann= 8 ,-1,0
       0      .1       0     390     .06       0     500     .12       0
   513.7    .045       0   589.8     .12       0     730      .1       0
     810     .06       0     960      .1       0
Bank Sta=513.7,589.8
XS Rating Curve= 0 ,0
Exp/Cntr(USF)=0,0
Exp/Cntr=0.3,0.1

Type RM Length L Ch R = 1 ,300691  ,466.8,473.4,487.1
XS GIS Cut Line= 2
2291564.69169099592264.3004613862292754.86563392591679.164777072
#Sta/Elev= 30
       0 3729.75      44 3717.85    97.7 3696.27   172.3 3674.06   208.9 3660.19
   242.8 3641.03   271.3 3629.62   284.7 3621.76   298.1 3617.48     356 3590.09
   427.3 3565.11   441.2  3556.3   485.3 3559.99   494.2 3556.87   505.7 3547.89
   514.8 3543.87   547.7 3540.08   627.9  3540.2   654.6 3549.29   681.4 3554.72
   704.2 3550.89     740 3554.26   895.3 3560.47   953.3 3567.22  1046.9 3583.67
  1064.7 3589.23  1104.1 3594.79  1171.7  3611.1  1229.6 3629.66  1326.2 3666.42
#Mann= 10 ,-1,0
       0      .1       0     360     .06       0     510      .1       0
   547.7    .045       0   627.9      .1       0     740     .12       0
     790      .1       0     900     .06       0    1010     .12       0
    1230      .1       0
#XS Ineff= 2 , 0
                          686.35         3574.14
Permanent Ineff=
       F       F
Bank Sta=547.7,627.9
XS Rating Curve= 0 ,0
Exp/Cntr(USF)=0,0
Exp/Cntr=0.3,0.1

Type RM Length L Ch R = 1 ,300218  ,451.2,469.2,491.8
XS GIS Cut Line= 3
2291628.37992874 592578.761135272292627.48915842592383.715907165
2292937.96931744592395.657451743
#Sta/Elev= 30
       0  3725.1      65 3711.81   126.1 3692.09   183.2 3666.55   260.3 3624.38
     281 3614.91   328.5 3597.78   415.5 3571.65     424 3570.76   448.1 3557.21
   484.8 3559.08   505.2 3551.95   525.5 3550.34   537.8 3545.15   562.2 3542.36
   574.4 3538.47   647.8 3538.44   666.1 3542.98   684.5 3544.77   700.8 3551.41
   790.4 3555.38     876 3564.21   908.6  3563.2   969.8 3574.85  1002.4 3576.42
  1026.7 3586.27  1150.8 3610.42  1270.8 3645.36  1306.9 3653.69  1328.7  3661.3
#Mann= 7 ,-1,0
       0      .1       0     460     .06       0     560      .1       0
   574.4    .045       0   647.8      .1       0     960     .06       0
 1057.97      .1       0
Bank Sta=574.4,647.8
XS Rating Curve= 0 ,0
Exp/Cntr(USF)=0,0
Exp/Cntr=0.3,0.1

Type RM Length L Ch R = 1 ,299748  ,401.1,400,398.8
XS GIS Cut Line= 2
2291584.59426529592726.0401850632292782.72923793593136.033215569
#Sta/Elev= 30
       0 3715.75    71.4 3701.66     101 3692.41   147.5  3672.7   181.7 3663.26
   215.2 3645.85   223.6 3643.61   240.5 3633.23   291.9 3610.32   380.1 3580.99
     435 3566.63   451.9 3555.25   498.4 3555.47   521.9 3544.64   553.4 3536.19
   632.1 3536.18   642.2 3536.27   697.1 3553.15   718.3  3552.6   828.2 3565.39
   845.1  3572.7   868.4 3572.02   937.6 3595.63   963.5 3597.29  1035.3 3609.75
  1052.3 3615.65  1132.6 3633.79  1158.7  3643.7  1217.1 3672.79  1266.3 3693.62
#Mann= 7 ,-1,0
       0      .1       0     420     .06       0     520     .03       0
   553.4    .045       0   642.2      .1       0     840     .06       0
     940      .1       0
Bank Sta=553.4,642.2
XS Rating Curve= 0 ,0
Exp/Cntr(USF)=0,0
Exp/Cntr=0.3,0.1

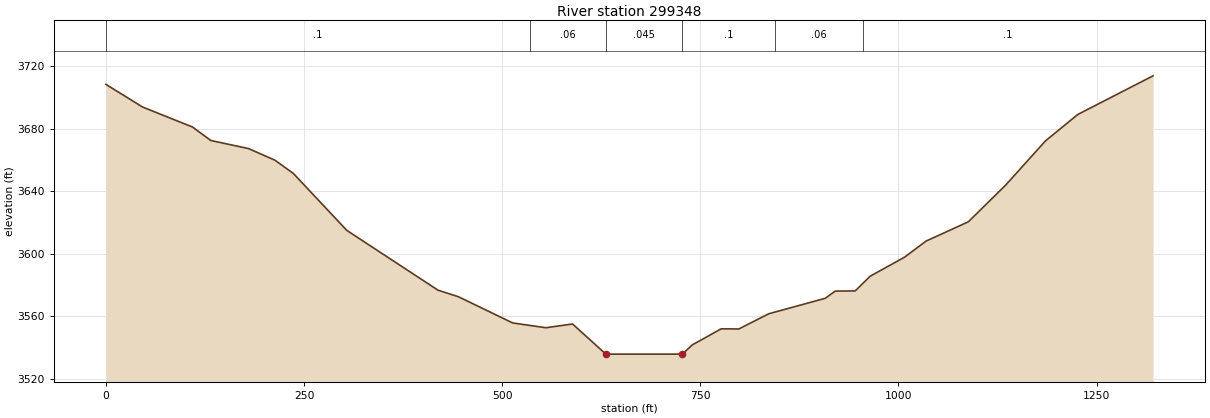
Type RM Length L Ch R = 1 ,299348  ,617.8,631.1,643.3
XS GIS Cut Line= 4
2291425.37367092592976.8126211982291823.42515684593235.546087051
2292289.14539538593382.8251368452292603.60606926593553.987275794
#Sta/Elev= 30
       0 3708.26    46.3 3693.76   109.3 3680.98   132.4 3672.37   179.9 3667.22
   213.3 3659.78   236.5 3651.31   303.9 3614.94     419 3576.69   444.7 3572.51
   513.3 3555.73   555.2 3552.68   588.8 3555.08   630.8 3535.81   727.3 3535.81
   739.8 3541.69   776.3 3551.97   798.6  3551.9   836.3  3561.6   907.6  3571.5
   920.2  3576.1   945.4 3576.22   964.2 3585.59  1007.6 3597.75  1034.8 3608.07
  1088.1 3620.38  1135.2 3643.83  1185.4 3672.09  1226.2 3688.99  1321.2 3713.71
#Mann= 6 ,-1,0
       0      .1       0  534.75     .06       0   630.8    .045       0
   727.3      .1       0  844.75     .06       0  954.75      .1       0
Bank Sta=630.8,727.3
XS Rating Curve= 0 ,0
Exp/Cntr(USF)=0,0
Exp/Cntr=0.3,0.1