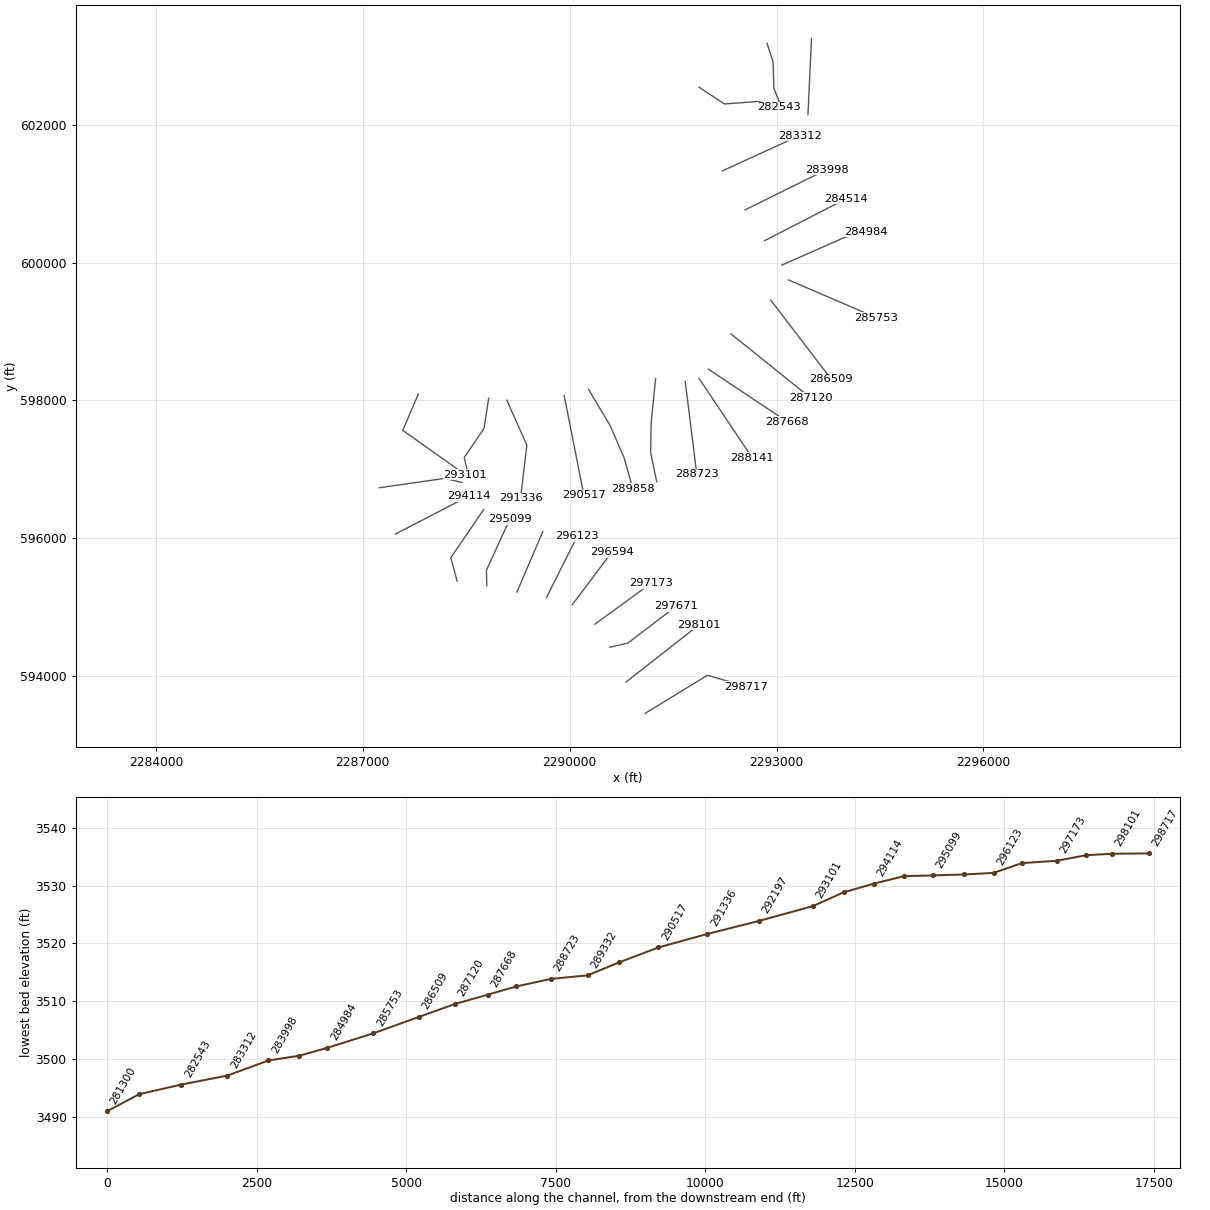
HEC-RAS study SHAVERSFK.prj: SHAVERSFK

--- SHAVERSFK.g01 (geometry) --- (continued)

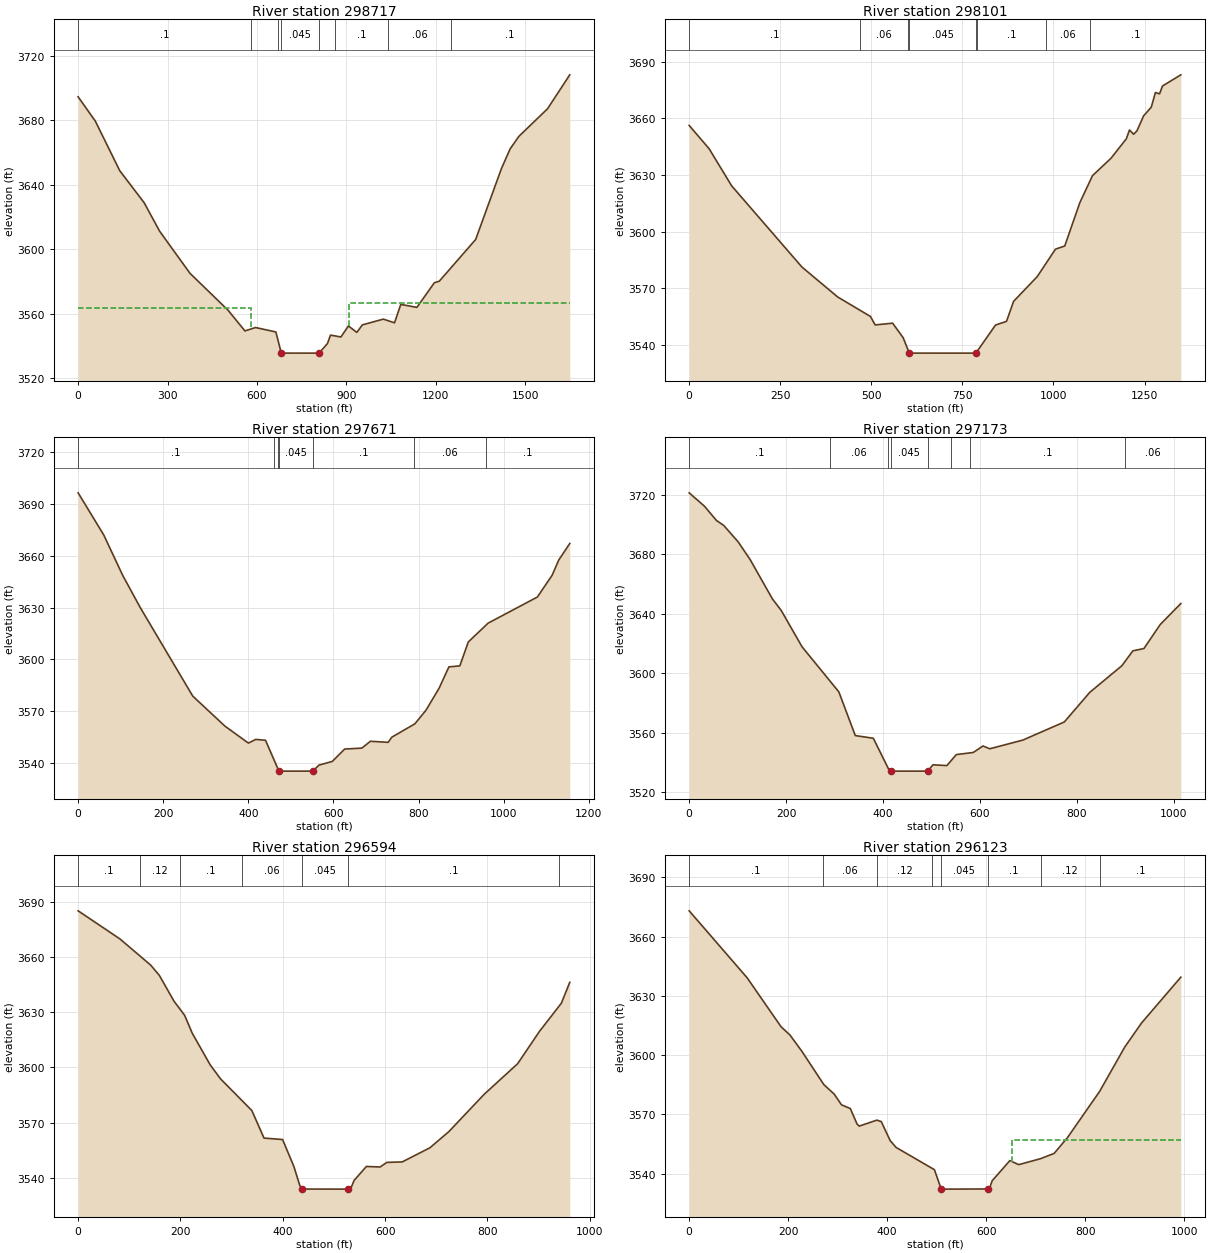
Type RM Length L Ch R = 1 ,298717  ,608.1,615.9,624.3
XS GIS Cut Line= 3
 2291094.9909376 593462.435434032291998.56781065594015.726999471
2292563.80092067593848.545375381
#Sta/Elev= 30
       0 3694.61    57.7 3679.53   139.6 3648.76   221.8  3628.8   273.3 3611.23
   375.2 3585.09   503.2 3562.12   559.5 3549.34   595.1 3551.44   663.2  3548.7
   681.5 3535.58   808.1 3535.56   836.3 3541.52   846.5 3546.74   881.4 3545.58
   906.6 3552.41   934.8 3548.43   953.5  3553.1  1023.9 3556.66  1061.2 3554.35
  1082.2 3565.79  1136.3 3563.95  1194.8 3579.22  1211.4  3580.2  1333.3 3606.05
  1419.9 3650.13  1449.1 3662.34  1478.3 3670.06  1574.3 3687.17    1649 3708.24
#Mann= 8 ,-1,0
       0      .1       0     580     .06       0     670    .025       0
   681.5    .045       0   808.1    .025       0     860      .1       0
    1040     .06       0 1249.52      .1       0
#XS Ineff= 2 , 0
          579.64 3563.79  907.15          3566.9
Permanent Ineff=
       F       F
Bank Sta=681.5,808.1
XS Rating Curve= 0 ,0
Exp/Cntr(USF)=0,0
Exp/Cntr=0.3,0.1

Type RM Length L Ch R = 1 ,298101  ,426.6,430.3,446.2
XS GIS Cut Line= 2
2290816.35489745593916.2141279892291879.15236487594748.141733579
#Sta/Elev= 30
       0 3656.27    54.7 3643.95   116.6 3624.25   309.6 3581.16     408 3565.25
   497.6 3554.96   510.6 3550.46   558.5 3551.39   587.5 3543.66   604.3 3535.51
     787  3535.5   841.1 3550.42   871.1 3552.34   890.6 3562.96   955.5  3576.1
  1005.6 3590.66    1031 3592.32  1072.3 3615.25  1107.2 3629.64    1158 3638.87
  1200.1  3649.2  1208.7 3653.88  1220.1 3651.62  1229.1 3653.37  1247.5 3661.37
  1268.5 3665.95  1279.9 3673.74  1291.3 3673.05  1299.4 3677.21  1349.7 3683.13
#Mann= 8 ,-1,0
       0      .1       0     470     .06       0     600      .1       0
   604.3    .045       0     787    .025       0     790      .1       0
     980     .06       0    1100      .1       0
Bank Sta=604.3,787
XS Rating Curve= 0 ,0
Exp/Cntr(USF)=0,0
Exp/Cntr=0.3,0.1

Type RM Length L Ch R = 1 ,297671  ,499.1,498.4,497.4
XS GIS Cut Line= 3
2290581.50452075594421.7395151182290844.21850146594481.447238007
2291548.76963155 595018.81674401
#Sta/Elev= 30
       0 3696.51    60.2 3672.11   105.1 3648.53   146.3 3629.91   269.4 3578.73
   344.8 3561.38   400.2  3551.5   417.6 3553.64   440.5 3553.11   471.8 3535.31
   473.4 3535.25   551.7 3535.25     566 3538.72   597.4 3540.88   626.5 3548.05
   666.8 3548.58   686.9 3552.55   728.7 3551.93   737.2 3554.91   791.5 3562.66
   817.7 3570.61   848.5 3583.34   871.4 3595.65   897.1 3596.24     917  3610.1
   963.6    3621  1079.3 3636.12    1114 3648.73  1129.6 3657.57  1155.5 3667.18
#Mann= 7 ,-1,0
       0      .1       0  459.41     .07       0  469.41      .1       0
   471.8    .045       0   551.7      .1       0  789.41     .06       0
  959.41      .1       0
Bank Sta=471.8,551.7
XS Rating Curve= 0 ,0
Exp/Cntr(USF)=0,0
Exp/Cntr=0.3,0.1

Type RM Length L Ch R = 1 ,297173  ,565.1,579.2,589.3
XS GIS Cut Line= 2
2290366.55671835594756.1027632972291186.54277936 595353.17999219
#Sta/Elev= 30
       0 3721.16    31.7 3712.13    56.3  3702.6    71.3 3699.26     101 3688.26
   125.7 3676.39   171.7 3649.95     190 3642.14   232.9 3617.76   308.8 3587.51
   342.7 3558.16   379.9 3556.36   411.4 3535.68   416.3 3534.37   427.5 3534.29
   491.9 3534.29     503 3538.53   531.6 3538.01   551.2  3545.4   586.2 3546.83
   606.1 3551.17   620.2  3549.3   688.2 3555.12   773.9 3567.29   826.5  3587.2
   892.7 3605.08   915.3 3615.05   938.2 3616.62   971.8 3632.73  1014.3 3646.83
#Mann= 8 ,-1,0
       0      .1       0     290     .06       0     410     .08       0
   416.3    .045       0   491.9     .08       0     540    .025       0
     580      .1       0     900     .06       0
Bank Sta=416.3,491.9
XS Rating Curve= 0 ,0
Exp/Cntr(USF)=0,0
Exp/Cntr=0.3,0.1

Type RM Length L Ch R = 1 ,296594  ,459.9,470.5,476.1
XS GIS Cut Line= 2
2290036.17398503595034.7388034472290613.34863962595802.978171289
#Sta/Elev= 30
       0 3684.97    81.7 3669.72   141.7 3655.54   158.9 3649.86   187.4 3635.92
   208.2 3628.23   223.2 3618.45   258.2 3601.32   278.2  3593.8   339.6 3576.51
   363.3 3561.59   399.6 3560.81   421.7 3546.18   433.3 3535.82   438.3 3533.92
   527.4 3533.88   528.4 3533.88   533.1 3534.38   539.4 3538.61   563.4 3546.18
   590.2  3545.9   603.4 3548.39   633.4 3548.65   687.4  3556.3   724.5 3565.08
   793.5 3585.34   859.1    3602   901.6 3619.49   944.5 3634.84   960.9 3646.16
#Mann= 7 ,-1,0
       0      .1       0     120     .12       0     200      .1       0
     320     .06       0   438.3    .045       0   528.4      .1       0
     940     .06       0
Bank Sta=438.3,528.4
XS Rating Curve= 0 ,0
Exp/Cntr(USF)=0,0
Exp/Cntr=0.3,0.1

Type RM Length L Ch R = 1 ,296123  ,497.6,500.7,505.9
XS GIS Cut Line= 2
2289665.98610311595146.1932195072290111.80376735596033.848033127
#Sta/Elev= 30
       0 3673.09   117.1 3639.19   185.6 3614.42   203.5 3610.25   227.7 3601.97
   272.2 3585.07   292.9 3580.34   307.7 3574.89   325.6 3572.97   339.1 3565.17
   343.5 3564.09   379.2 3567.12   388.1 3566.38   406.1 3556.75     418 3553.31
   495.5 3542.03   509.1 3532.26   513.4 3532.19   603.1 3532.27   607.6 3533.18
   612.1  3536.4   647.9 3546.64   665.8 3544.59     710 3547.61   737.4 3550.29
   764.3 3558.28   829.2 3581.64   879.9 3604.08   913.9 3616.29   993.3  3639.5
#Mann= 8 ,-1,0
       0      .1       0     270     .06       0     380     .12       0
     490      .1       0   509.1    .045       0   603.1      .1       0
     710     .12       0     830      .1       0
#XS Ineff= 2 , 0
                          651.99         3557.24
Permanent Ineff=
       F       F
Bank Sta=509.1,603.1
XS Rating Curve= 0 ,0
Exp/Cntr(USF)=0,0
Exp/Cntr=0.3,0.1

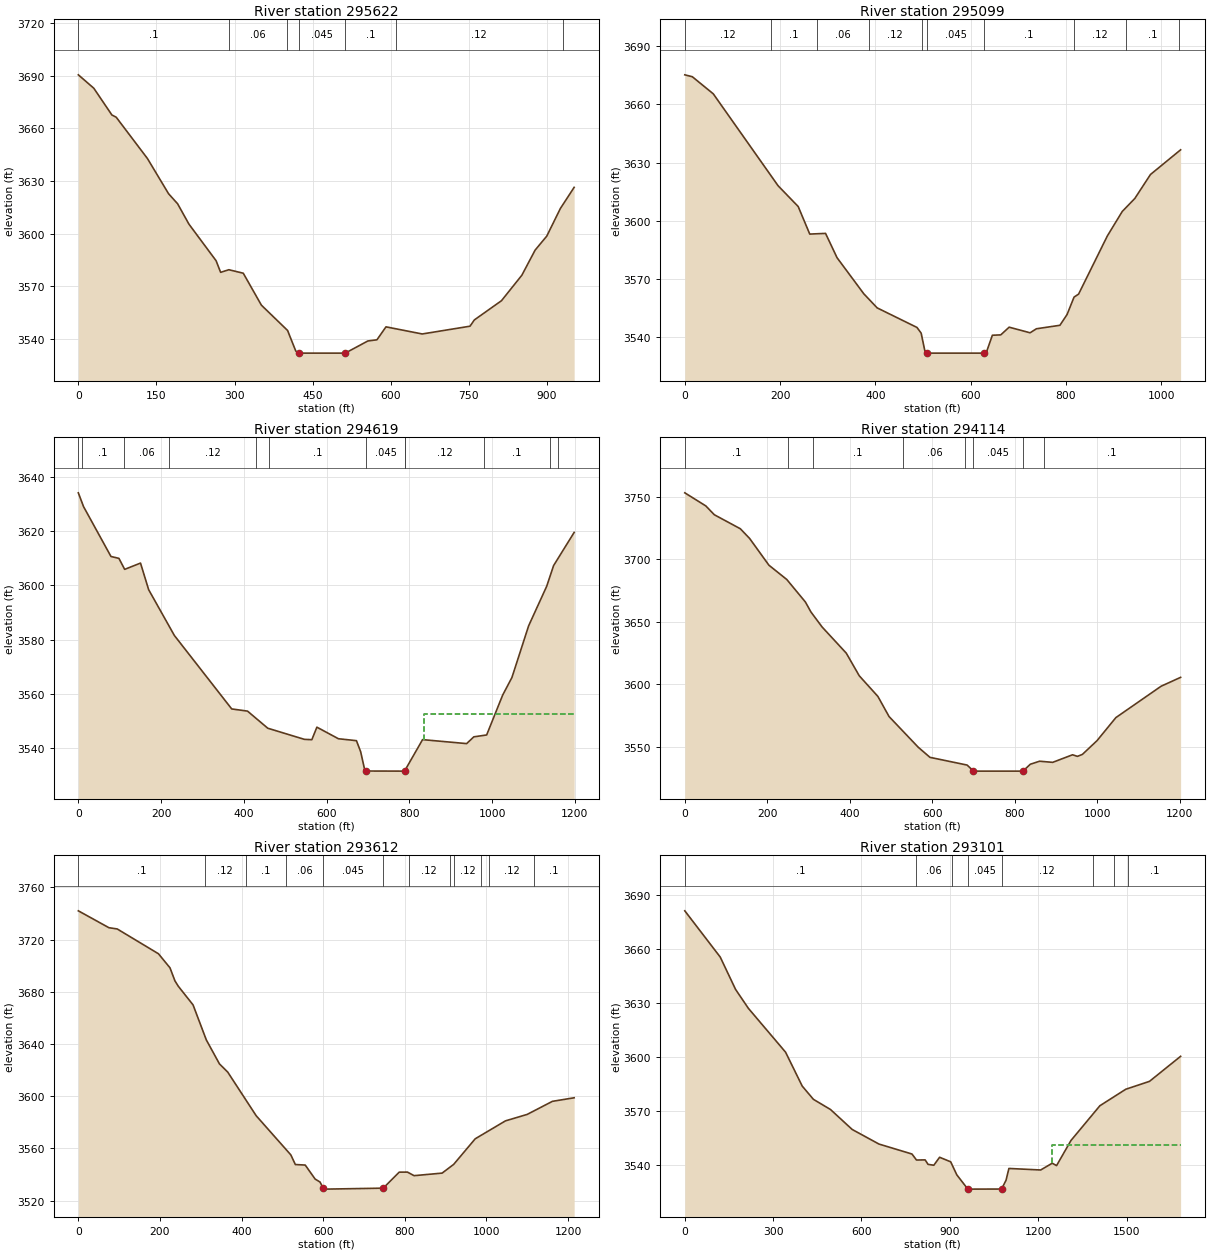
Type RM Length L Ch R = 1 ,295622  ,524.9,523.2,521.8
XS GIS Cut Line= 2
2289236.09049831595221.8230018342289610.25889508596097.536270876
#Sta/Elev= 30
       0 3690.55    29.7 3682.91    64.5 3667.65    72.7  3666.4   132.6  3642.9
   173.3 3622.78   190.7 3617.04   212.4 3605.46   264.6 3584.58   273.3 3577.96
   289.1 3579.45   316.8 3577.46   351.6 3559.25   401.9 3544.83   417.6 3533.12
   423.2 3531.93   425.6 3531.91   512.6 3531.91   556.1 3538.84   573.5  3539.5
   590.9 3546.89   660.5 3542.83   752.3 3547.26   760.5 3550.81   812.7 3561.79
   851.9 3576.34   877.3 3590.62   899.7 3598.61   925.8 3614.34   952.3 3626.42
#Mann= 7 ,-1,0
       0      .1       0     290     .06       0     400    .025       0
   423.2    .045       0   512.6      .1       0     610     .12       0
     930      .1       0
Bank Sta=423.2,512.6
XS Rating Curve= 0 ,0
Exp/Cntr(USF)=0,0
Exp/Cntr=0.3,0.1

Type RM Length L Ch R = 1 ,295099  ,487.1,479.8,472
XS GIS Cut Line= 3
2288798.23386379595313.3748435972288794.25334893595540.264190576
2289132.59711197596280.639954403
#Sta/Elev= 30
       0 3675.21    15.8 3674.23    59.8 3665.41   195.8 3618.05   238.1 3607.31
   262.3 3593.12   295.5 3593.47   319.6 3580.95   375.9 3562.31   403.8 3555.08
   487.4 3544.99   496.2 3542.06   503.7  3533.2   509.4 3531.75   627.5 3531.75
   633.5 3532.42   645.7 3540.97   663.3 3541.15   680.9 3545.13   724.9 3542.23
   738.1  3544.3   787.5  3546.1   802.6  3551.7   817.2 3560.64   826.7 3562.17
   887.1 3592.17   918.4 3604.78   944.8 3611.49   977.6 3623.83  1040.9 3636.56
#Mann= 10 ,-1,0
       0     .12       0     180      .1       0  276.92     .06       0
  386.92     .12       0  496.92    .025       0   509.4    .045       0
   627.5      .1       0  816.92     .12       0  926.92      .1       0
 1036.92     .12       0
Bank Sta=509.4,627.5
XS Rating Curve= 0 ,0
Exp/Cntr(USF)=0,0
Exp/Cntr=0.3,0.1

Type RM Length L Ch R = 1 ,294619  ,537.3,505.8,484.5
XS GIS Cut Line= 3
2288368.33825899595381.0435962052288276.78641722595719.387359244
2288754.44820034596419.957974478
#Sta/Elev= 30
       0 3634.05    12.6 3628.98    78.9 3610.62    98.1 3609.93     112 3605.88
   150.3 3608.19     170 3598.39   232.2 3581.53   370.7 3554.51   408.9 3553.71
   457.9 3547.41   546.3 3543.32   564.4 3543.19   576.6  3547.8   628.6 3543.54
   672.2 3542.83   682.4 3538.76   691.6 3532.46   696.4 3531.66   788.4 3531.62
     832 3543.21   938.5 3541.75   955.9 3544.24   986.9 3544.93  1025.6  3559.6
    1048 3566.08  1088.3 3585.07  1132.1 3599.68  1148.7 3607.27  1198.4 3619.48
#Mann= 12 ,-1,0
       0     .12       0      10      .1       0     110     .06       0
     220     .12       0  430.51     .06       0  460.51      .1       0
   696.4    .045       0   788.4      .1       0  790.51     .12       0
  980.51      .1       0 1140.51     .12       0 1160.51      .1       0
#XS Ineff= 2 , 0
                          835.23         3552.69
Permanent Ineff=
       F       F
Bank Sta=696.4,788.4
XS Rating Curve= 0 ,0
Exp/Cntr(USF)=0,0
Exp/Cntr=0.3,0.1

Type RM Length L Ch R = 1 ,294114  ,510.5,502,458.9
XS GIS Cut Line= 2
2287472.72241565596061.7116371422288539.50039794596615.003202582
#Sta/Elev= 30
       0 3753.27      51 3742.77    71.5 3735.72   134.6 3724.49   157.1 3716.72
   203.9 3695.28   247.2 3683.83   292.3  3665.8   305.8 3657.77   332.8 3645.78
   391.4 3624.82   422.9 3606.66     468 3590.16     495 3574.05   565.9 3549.41
   594.2 3541.35   684.3 3535.16   699.4 3530.46   702.3 3530.31   819.5 3530.31
   837.5 3535.85     860 3538.25   891.6 3537.34   939.8 3543.41   951.6 3542.14
   963.7 3543.72   999.1 3554.73  1044.8  3573.2  1154.3 3598.31  1201.7 3605.44
#Mann= 8 ,-1,0
       0      .1       0     250     .12       0     310      .1       0
     530     .06       0     680      .1       0   699.4    .045       0
   819.5    .025       0     870      .1       0
Bank Sta=699.4,819.5
XS Rating Curve= 0 ,0
Exp/Cntr(USF)=0,0
Exp/Cntr=0.3,0.1

Type RM Length L Ch R = 1 ,293612  ,546,511,451.5
XS GIS Cut Line= 3
2287241.85255381596734.4186483612288189.21509032596869.756153577
2288439.98752645596810.048430687
#Sta/Elev= 30
       0 3742.02    75.1 3729.07    95.3 3728.13   196.3 3709.13   224.6 3698.34
   236.7 3688.35   244.8  3684.3   281.1 3669.95   313.5 3643.19   345.8 3624.74
     366 3618.49   435.8 3585.03   520.7 3555.03   531.7 3547.65   555.9 3547.26
   580.2 3536.52   592.3 3534.23  599.773529.507   604.4 3528.82     747 3529.56
   786.2 3541.83   806.4 3541.86   822.6 3539.13   891.3 3541.09   919.6 3547.77
   972.4 3567.38  1046.4  3581.1  1099.8 3586.07  1161.5 3596.07  1214.8  3598.8
#Mann= 12 ,-1,0
       0      .1       0     310     .12       0     410      .1       0
     510     .06       0  599.77    .045       0     747      .1       0
     810     .12       0     910      .1       0     920     .12       0
  986.98      .1       0 1006.98     .12       0 1116.98      .1       0
Bank Sta=599.77,747
XS Rating Curve= 0 ,0
Exp/Cntr(USF)=0,0
Exp/Cntr=0.3,0.1

Type RM Length L Ch R = 1 ,293101  ,973,903.2,810.6
XS GIS Cut Line= 3
2287807.08566383598095.7547302362287580.19631685597566.346253951
2288483.77318991596925.483361606
#Sta/Elev= 30
       0 3681.01   120.3 3655.34   172.5 3637.35     216 3626.84   342.2 3602.51
   398.8 3583.66   436.8 3576.31   494.6 3570.69   568.5 3559.57   659.3 3551.48
   771.6 3545.93   786.8  3542.6   816.2 3542.68   826.1 3540.19   845.7 3539.71
   865.3 3544.14     903  3541.6   923.7 3534.38   961.3 3526.44  1075.8 3526.49
  1090.9 3531.38  1100.7 3537.92  1208.6 3537.07  1247.8 3540.84  1262.5  3539.5
  1311.5 3553.47  1409.6 3572.75  1497.6 3581.92  1578.1  3586.3  1683.8 3600.21
#Mann= 8 ,-1,0
       0      .1       0  785.98     .06       0  905.98     .12       0
   961.3    .045       0  1075.8     .12       0 1385.98      .1       0
 1455.98     .12       0 1505.98      .1       0
#XS Ineff= 2 , 0
                         1247.65         3551.03
Permanent Ineff=
       F       F
Bank Sta=961.3,1075.8
XS Rating Curve= 0 ,0
Exp/Cntr(USF)=0,0
Exp/Cntr=0.3,0.1

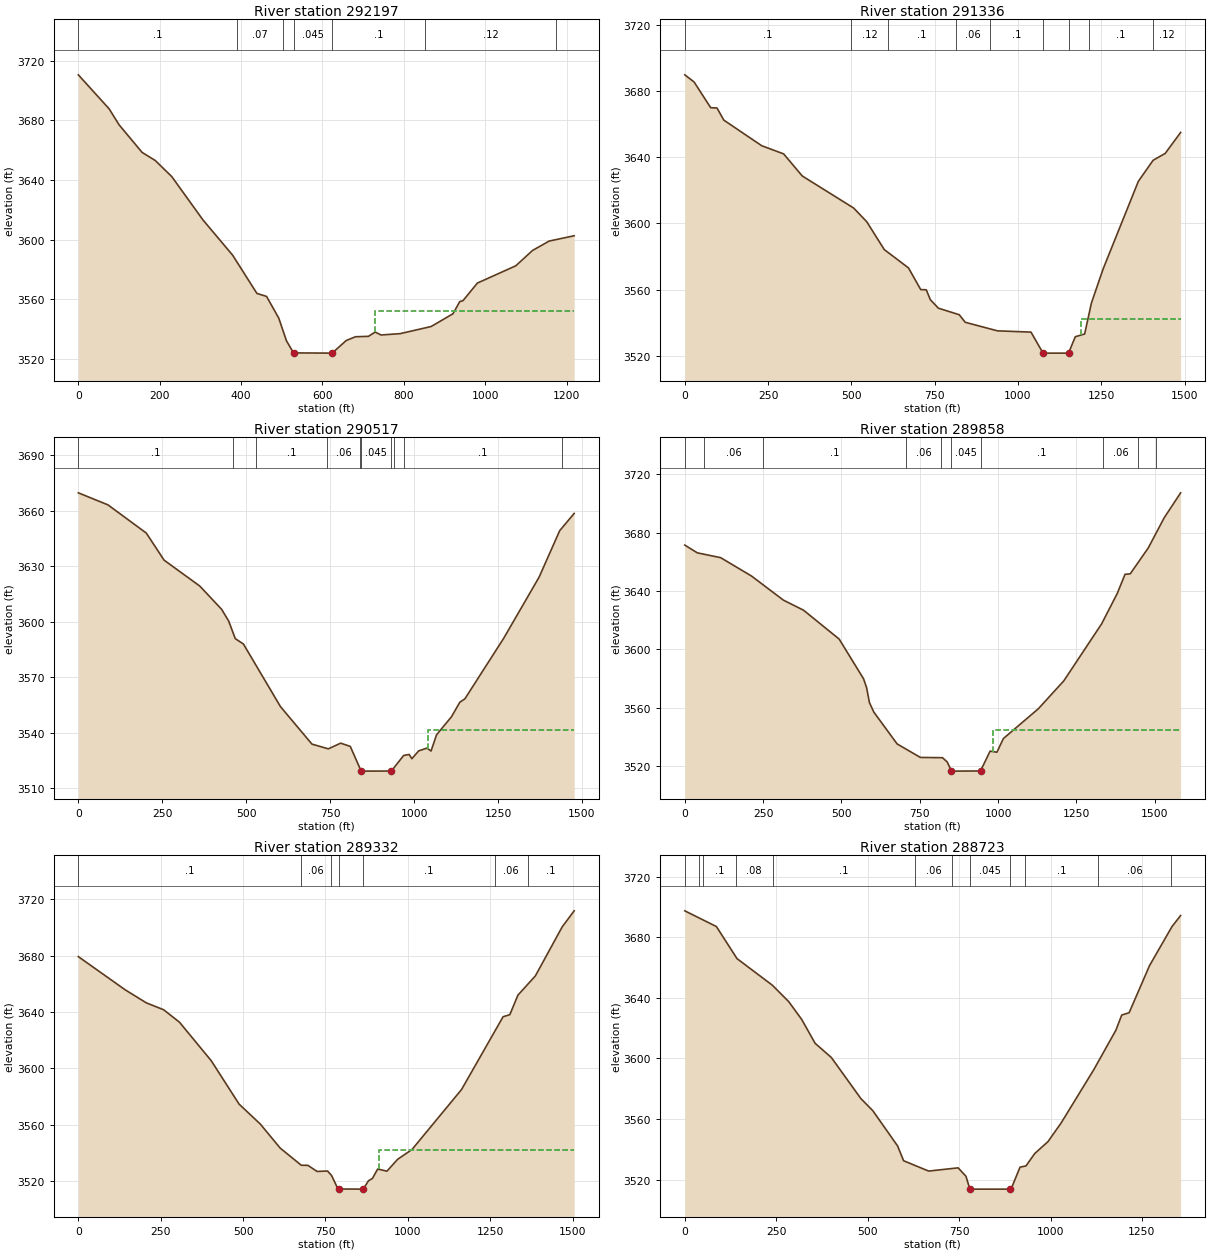
Type RM Length L Ch R = 1 ,292197  ,841.9,861.6,875.8
XS GIS Cut Line= 4
 2288826.0974678598032.066492487 2288758.4287152597594.209857966
2288471.83164533597172.2752828822288531.53936822596913.541817029
#Sta/Elev= 30
       0 3710.45    75.8 3687.63   100.1 3676.97   156.7 3658.45   189.1 3653.01
   229.6 3642.25   306.5 3613.11   379.4 3589.49   438.9 3563.92   462.7 3561.88
   492.7 3547.31   511.6 3532.14   528.9 3524.02   623.2 3523.87     624 3523.92
   658.5 3532.33   681.2 3534.85   713.2 3535.13   729.6    3538   744.1 3536.03
     791 3536.93   867.1 3541.71   920.9 3550.26   937.5 3558.41   945.4 3559.03
   980.9 3570.85  1075.3 3582.42  1116.4  3592.7  1157.4 3599.01  1218.7 3602.55
#Mann= 7 ,-1,0
       0      .1       0     390     .07       0  503.05      .1       0
   528.9    .045       0     624      .1       0  853.05     .12       0
 1173.12      .1       0
#XS Ineff= 2 , 0
                          728.81         3552.16
Permanent Ineff=
       F       F
Bank Sta=528.9,624
XS Rating Curve= 0 ,0
Exp/Cntr(USF)=0,0
Exp/Cntr=0.3,0.1

Type RM Length L Ch R = 1 ,291336  ,806.4,818.4,828.3
XS GIS Cut Line= 3
2289088.81144852598004.2028884722289379.38903324 597351.39845155
2289287.83719148596583.159083708
#Sta/Elev= 30
       0 3689.73    27.9 3685.41    77.7 3669.88    96.8 3669.67   117.1 3662.37
     231 3646.89   296.7 3641.97   352.5 3628.63   506.8 3609.27   546.2 3600.97
   598.7 3584.17   671.4  3573.1   708.2 3559.98   724.8 3559.88   736.9 3553.92
   761.1 3548.77   823.8 3544.82   841.7 3540.25   938.3 3535.09  1039.1 3534.31
  1075.3 3521.62  1151.8 3521.62    1172 3531.52  1200.2 3533.19  1220.3 3551.79
  1255.7 3572.53  1361.3 3625.39  1405.6 3638.11  1441.9 3642.25  1488.2 3654.93
#Mann= 9 ,-1,0
       0      .1       0     500     .12       0     610      .1       0
  814.56     .06       0  914.56      .1       0  1075.3    .045       0
  1151.8    .025       0 1214.56      .1       0 1404.56     .12       0
#XS Ineff= 2 , 0
                         1188.74         3542.34
Permanent Ineff=
       F       F
Bank Sta=1075.3,1151.8
XS Rating Curve= 0 ,0
Exp/Cntr(USF)=0,0
Exp/Cntr=0.3,0.1

Type RM Length L Ch R = 1 ,290517  ,647.5,658.9,665.8
XS GIS Cut Line= 2
2289920.73905411 598071.871641082290207.33612398596622.964232301
#Sta/Elev= 30
       0 3669.66    88.4 3663.14   202.4 3647.93   255.5 3633.28   361.6 3619.32
   426.8 3606.73   447.8 3600.39   467.6 3590.87   491.8 3587.96   602.1 3554.15
   695.9 3533.88   744.8 3531.32   781.5 3534.39   810.1 3532.64   842.6 3519.28
   932.4 3519.32   969.1 3527.74   985.4 3528.29   993.6    3526    1014 3530.23
  1038.4 3531.73  1050.7 3530.15    1067 3538.88  1111.6 3548.67  1136.3 3556.48
  1151.5 3558.34  1266.8 3590.98  1372.8 3624.17  1433.9  3649.2    1477 3658.53
#Mann= 10 ,-1,0
       0      .1       0     460     .06       0     530      .1       0
     740     .06       0     840      .1       0   842.6    .045       0
   932.4      .1       0     940    .025       0     970      .1       0
    1440     .06       0
#XS Ineff= 2 , 0
                         1040.87         3541.28
Permanent Ineff=
       F       F
Bank Sta=842.6,932.4
XS Rating Curve= 0 ,0
Exp/Cntr(USF)=0,0
Exp/Cntr=0.3,0.1

Type RM Length L Ch R = 1 ,289858  ,540.1,526.7,507.2
XS GIS Cut Line= 4
2290275.00487658598159.4429679842290585.48503561597637.995521418
2290788.49129343597172.2752828822290915.86776893596722.477103783
#Sta/Elev= 30
       0 3671.39    39.9 3666.09   114.4 3662.79   212.6 3650.26   314.7 3633.72
   378.9 3626.84   492.7 3607.06   570.6 3579.86   580.3 3573.75   589.2 3563.65
   603.2 3557.13   677.6 3535.31   751.8 3526.07   822.3 3525.88   837.5 3522.96
  851.133516.787   852.1 3516.69   943.8 3516.81   974.3 3530.37   996.1 3529.63
  1016.8    3539  1128.4 3559.39  1209.6 3578.48  1330.2 3617.46  1380.1 3638.27
    1405 3651.39  1421.6 3651.73  1479.5 3669.57  1529.7 3689.98  1582.4 3707.16
#Mann= 10 ,-1,0
       0      .1       0      60     .06       0     250      .1       0
  706.88     .06       0  816.88      .1       0  851.13    .045       0
   943.8      .1       0 1334.92     .06       0 1444.92      .1       0
 1504.92     .12       0
#XS Ineff= 2 , 0
                           983.1         3544.83
Permanent Ineff=
       F       F
Bank Sta=851.13,943.8
XS Rating Curve= 0 ,0
Exp/Cntr(USF)=0,0
Exp/Cntr=0.3,0.1

Type RM Length L Ch R = 1 ,289332  ,595.4,608.7,613.4
XS GIS Cut Line= 4
2291246.25050225598314.683047496 2291182.5622645 597681.78118487
2291174.60123478597243.9245503492291262.17256168596821.989975265
#Sta/Elev= 30
       0 3679.25   142.2 3655.72   206.5 3646.46   258.8 3641.61     307 3632.77
   403.5 3605.44     488  3574.7   552.3 3560.59   612.6 3543.56   676.7 3531.37
   696.7 3531.32   724.7 3526.98   756.5 3527.28   768.7 3524.12   784.4 3516.39
   792.7 3514.53   864.7 3514.45   880.7 3520.36   892.7 3522.04   908.7 3528.71
   936.8 3527.17   969.1 3535.57  1012.8 3542.53  1163.2 3585.05  1289.3 3636.64
  1309.7 3638.08  1334.2  3651.9  1387.3  3665.6    1469 3700.44    1505  3711.7
#Mann= 7 ,-1,0
       0      .1       0   676.1     .06       0   766.1      .1       0
   792.7    .045       0   864.7      .1       0 1264.03     .06       0
 1364.03      .1       0
#XS Ineff= 2 , 0
                          913.79         3542.24
Permanent Ineff=
       F       F
Bank Sta=792.7,864.7
XS Rating Curve= 0 ,0
Exp/Cntr(USF)=0,0
Exp/Cntr=0.3,0.1

Type RM Length L Ch R = 1 ,288723  ,551.2,581.7,600.7
XS GIS Cut Line= 2
2291676.14610705598274.8778989042291843.32773114596929.463876466
#Sta/Elev= 30
       0 3697.39    86.4 3687.02   142.8 3665.88   239.5 3648.31   283.9 3637.58
   319.5 3625.83   356.3 3610.04   400.8 3600.63   481.4 3573.58   514.2 3565.55
   581.9 3542.32   598.3 3532.57   666.8 3525.75   747.4 3527.88   768.8 3522.34
   779.6 3513.84   888.5 3513.84   892.5 3514.08   916.7 3528.33   932.8 3529.13
     957 3537.34   993.3 3545.22  1029.6 3557.68  1118.2 3592.56  1178.7 3618.61
  1194.8 3628.66    1215 3630.18  1270.7 3661.21  1332.1 3686.97  1355.8 3694.29
#Mann= 12 ,-1,0
       0      .1       0      40     .08       0      50      .1       0
     140     .08       0     240      .1       0     630     .06       0
     730      .1       0   779.6    .045       0   888.5    .025       0
     930      .1       0    1130     .06       0    1330      .1       0
Bank Sta=779.6,888.5
XS Rating Curve= 0 ,0
Exp/Cntr(USF)=0,0
Exp/Cntr=0.3,0.1

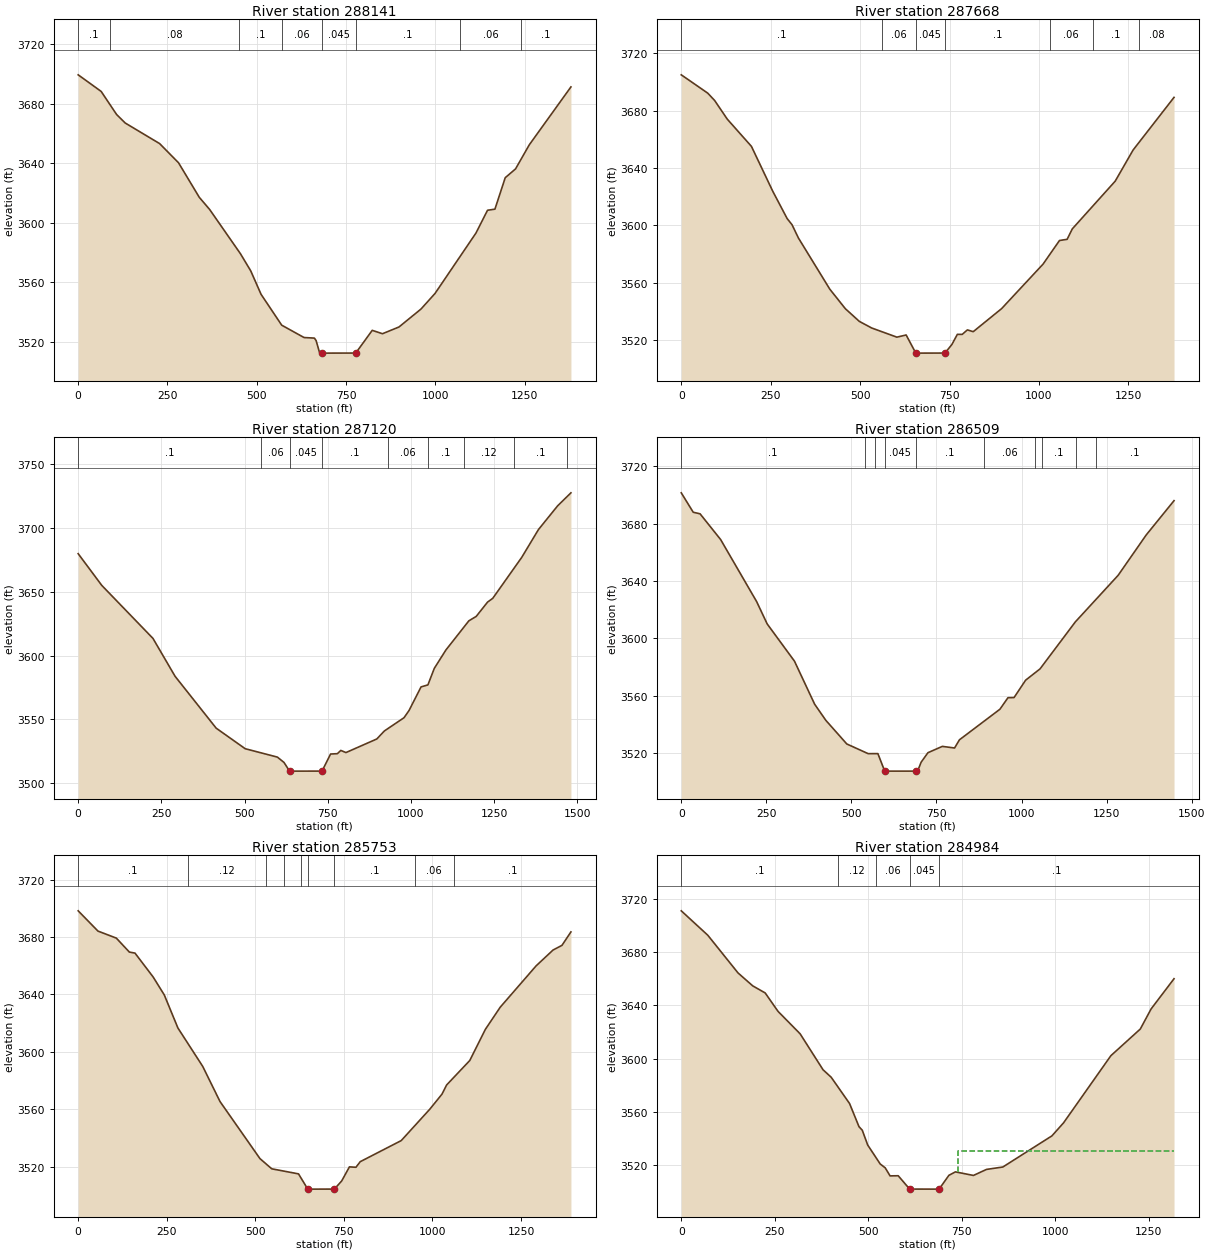
Type RM Length L Ch R = 1 ,288141  ,455.3,472.9,490.9
XS GIS Cut Line= 2
2291879.15236487598314.6830474962292647.39173272597168.294768023
#Sta/Elev= 30
       0 3699.47    64.4 3688.32   107.7 3672.79   131.8 3667.09   228.1 3653.28
   281.1 3640.38   339.1 3617.21   368.3 3608.99   454.5 3579.28   483.3 3567.78
   512.1 3552.07     570 3531.31   632.6    3523   661.5 3522.62   666.3 3520.99
   675.9 3512.95   682.2 3512.53   777.4 3512.58   823.5 3527.83   852.3 3525.57
   898.5  3530.1     960 3542.12   999.4 3552.62  1114.1 3593.22  1146.4  3608.5
  1167.1 3609.22    1196 3630.37  1224.9 3636.28  1263.4 3652.47    1380 3691.35
#Mann= 8 ,-1,0
       0      .1       0      90     .08       0     450      .1       0
     570     .06       0   682.2    .045       0   777.4      .1       0
    1070     .06       0    1240      .1       0
Bank Sta=682.2,777.4
XS Rating Curve= 0 ,0
Exp/Cntr(USF)=0,0
Exp/Cntr=0.3,0.1

Type RM Length L Ch R = 1 ,287668  ,552.8,548.3,543.2
XS GIS Cut Line= 2
2292010.50935523598454.001067571 2293156.8976347597689.742214589
#Sta/Elev= 30
       0 3704.87    73.9 3692.14    93.3 3687.01   128.7    3674   196.2 3655.06
   255.6 3623.93     296 3604.82   309.7 3600.51   327.7 3591.21   415.4 3555.62
   458.7 3542.07   497.9 3533.21   532.5 3528.61   602.9 3522.24   628.8 3523.76
   655.8 3511.12   737.3 3511.17   756.8 3517.17   771.9 3524.18   785.6 3524.18
     800  3527.3   816.3 3526.05   895.7  3542.1  1011.6 3573.09  1057.5 3589.52
  1078.9 3590.35  1093.3  3597.6  1213.3 3630.84  1263.4 3652.54  1377.8 3689.18
#Mann= 7 ,-1,0
       0      .1       0     560     .06       0   655.8    .045       0
   737.3      .1       0    1030     .06       0    1150      .1       0
    1280     .08       0
Bank Sta=655.8,737.3
XS Rating Curve= 0 ,0
Exp/Cntr(USF)=0,0
Exp/Cntr=0.3,0.1

Type RM Length L Ch R = 1 ,287120  ,620.2,611.2,596.9
XS GIS Cut Line= 2
2292340.89208855598963.5069695592293495.24139774598036.047007347
#Sta/Elev= 30
       0 3680.04    70.9 3655.18   224.8 3613.58   291.1 3583.92   414.7 3543.21
   501.9 3527.09   598.6 3520.51   618.5 3516.33   635.3 3509.51   732.8 3509.53
   758.5 3522.92     779  3523.2   789.2 3525.75   804.7 3524.07   897.4 3534.72
   920.1    3541   979.1 3551.38   994.1 3556.97  1030.4 3575.56    1051 3577.14
  1070.2  3590.1  1105.1 3604.52  1174.1  3627.4  1196.1 3630.84  1230.3 3642.07
  1245.9 3645.04  1333.2 3677.25  1383.2 3698.97  1440.9 3717.59  1480.8 3727.77
#Mann= 9 ,-1,0
       0      .1       0     550     .06       0   635.3    .045       0
   732.8      .1       0     930     .06       0    1050      .1       0
    1160     .12       0    1310      .1       0    1470     .12       0
Bank Sta=635.3,732.8
XS Rating Curve= 0 ,0
Exp/Cntr(USF)=0,0
Exp/Cntr=0.3,0.1

Type RM Length L Ch R = 1 ,286509  ,732.4,756.4,773.4
XS GIS Cut Line= 2
2292914.08622829599457.0908121112293793.78001219598306.722017778
#Sta/Elev= 30
       0 3701.47    35.1 3687.93    55.3 3686.81   115.6 3668.89   221.5 3625.57
   252.5 3609.97   332.7 3583.99   391.9 3553.98   424.9 3542.68   486.5 3526.19
   549.3 3519.43   577.8 3519.46   597.8 3507.33   599.1 3507.24   689.8 3507.25
   694.9 3507.43   704.9 3513.45     725 3520.11   767.3 3524.51   803.2 3523.38
   817.5 3529.09   936.5 3550.43   960.2  3558.5     978 3558.57    1012 3570.71
  1054.4 3578.59  1158.1 3611.38  1283.9 3643.89  1366.5 3672.08  1448.2    3696
#Mann= 10 ,-1,0
       0      .1       0     540     .06       0     570      .1       0
   597.8    .045       0   689.8      .1       0     890     .06       0
    1040     .12       0    1060      .1       0    1160     .12       0
    1220      .1       0
Bank Sta=597.8,689.8
XS Rating Curve= 0 ,0
Exp/Cntr(USF)=0,0
Exp/Cntr=0.3,0.1

Type RM Length L Ch R = 1 ,285753  ,735.9,768.6,797.8
XS GIS Cut Line= 2
2293172.81969414599747.6683968382294450.56496397599198.357346257
#Sta/Elev= 30
       0 3698.19    55.9 3684.07   107.6 3679.21   144.5 3669.47   160.4 3668.75
   211.5 3652.16   243.1 3639.61   281.5 3616.61   351.6 3589.85   400.3 3565.42
   513.1 3525.66   546.4 3518.56   621.9 3515.04     648 3504.42   723.1 3504.44
   743.8 3510.13   765.6 3519.93     784 3519.63   796.1 3523.53   911.8 3538.21
     992 3559.94  1026.8 3570.54  1039.9 3576.93  1105.2 3593.95  1149.3 3615.67
  1191.2 3631.08  1292.4 3659.84  1340.3 3670.89  1365.5 3674.15  1390.8 3683.51
#Mann= 9 ,-1,0
       0      .1       0     310     .12       0     530      .1       0
     580     .06       0     630      .1       0     648    .045       0
   723.1      .1       0     950     .06       0    1060      .1       0
Bank Sta=648,723.1
XS Rating Curve= 0 ,0
Exp/Cntr(USF)=0,0
Exp/Cntr=0.3,0.1

Type RM Length L Ch R = 1 ,284984  ,466.9,469.6,472.1
XS GIS Cut Line= 3
2293077.28733752599962.6161992392293988.82524029600364.648200027
2294299.30539932600448.239012072
#Sta/Elev= 30
       0 3710.97    70.9 3692.65   151.8 3664.31   191.1 3654.61   224.4 3649.28
   258.7 3635.47   317.9 3618.57   379.1  3591.6     401 3585.93   450.1 3566.21
   475.3 3548.83   484.1 3546.15   498.6 3535.03   532.1 3520.77   545.3 3517.94
   558.4 3511.86   580.2 3511.96   610.8 3501.94   689.5 3501.91   715.8  3512.3
   733.2 3514.87   781.3 3512.19   816.3 3516.72     860 3518.53   991.2 3541.91
  1022.3 3551.68  1148.9 3602.15  1227.6 3622.17  1256.6 3637.31  1317.8 3659.97
#Mann= 5 ,-1,0
       0      .1       0     420     .12       0     520     .06       0
   610.8    .045       0   689.5      .1       0
#XS Ineff= 2 , 0
                          739.93          3530.6
Permanent Ineff=
       F       F
Bank Sta=610.8,689.5
XS Rating Curve= 0 ,0
Exp/Cntr(USF)=0,0
Exp/Cntr=0.3,0.1

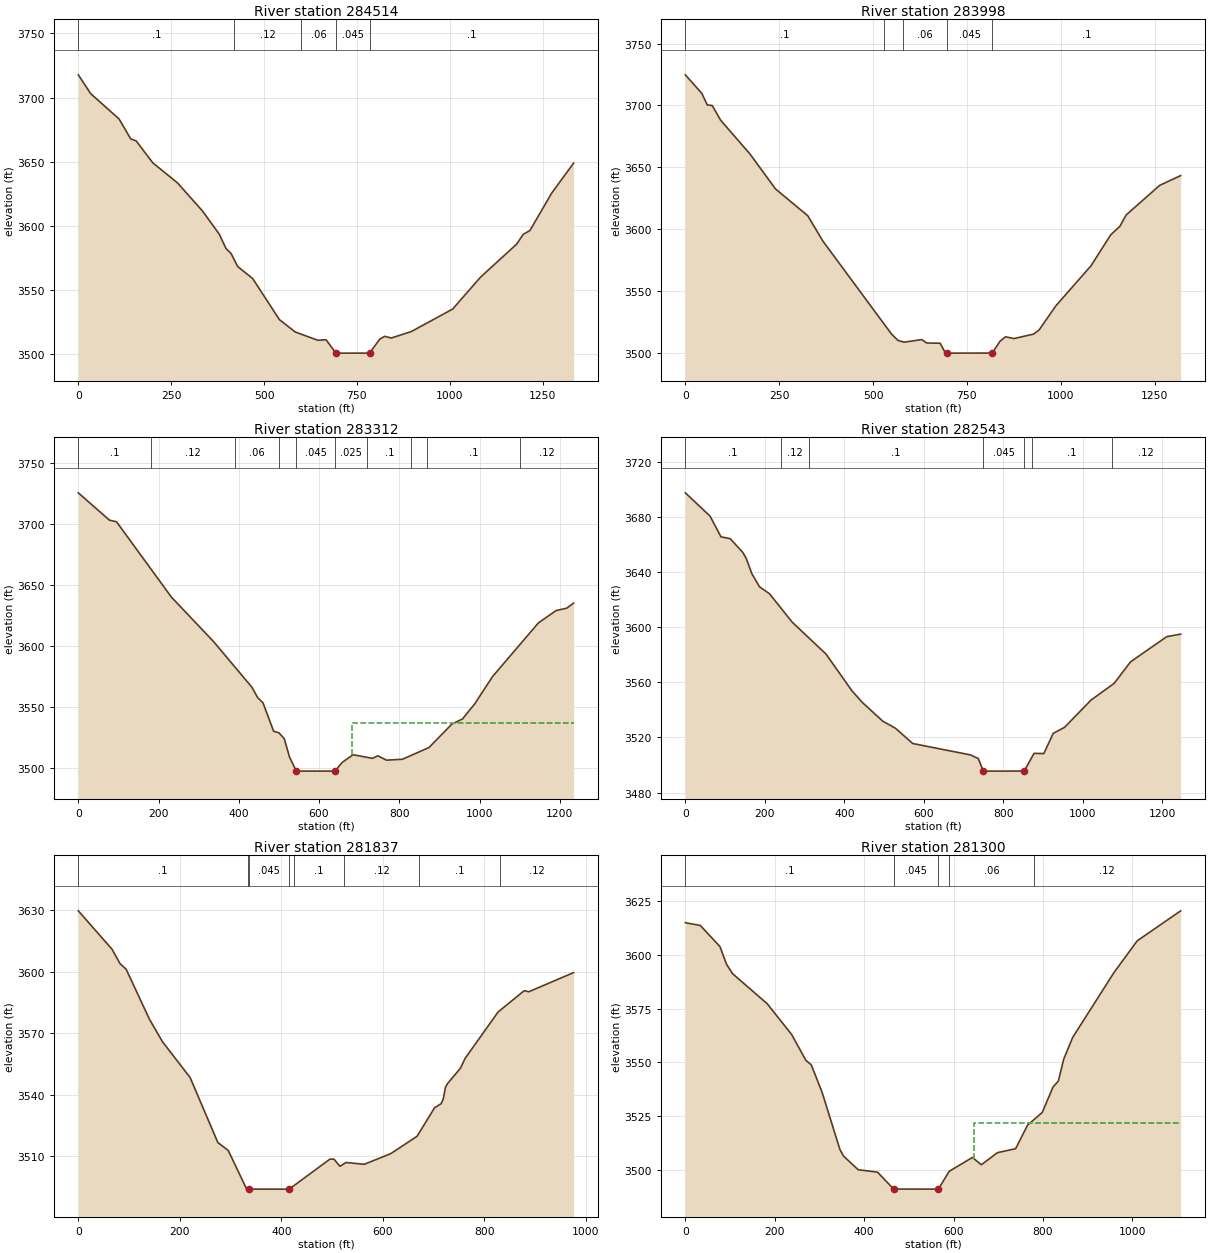
Type RM Length L Ch R = 1 ,284514  ,518.7,516.2,515.1
XS GIS Cut Line= 2
2292826.51490138600316.8820217162294012.70832945600925.900795186
#Sta/Elev= 30
       0 3717.73    33.3 3703.05   109.8 3683.26   141.1 3667.72   155.9 3666.11
   200.5 3649.06   267.2 3633.36   334.2  3611.5   379.6 3593.34   397.5 3582.22
   411.5 3578.19     429 3568.15   469.5 3558.74   541.4 3526.69   583.8 3517.07
   644.9 3510.56     667 3510.97   693.7 3500.54   784.2 3500.55   811.2 3511.33
   824.7 3513.67   842.7 3512.34   896.7 3517.41  1007.8 3534.94  1082.9 3559.86
  1179.9 3585.56  1197.9 3593.26  1215.9 3596.25  1274.3 3625.41  1333.4 3648.84
#Mann= 5 ,-1,0
       0      .1       0     420     .12       0     600     .06       0
   693.7    .045       0   784.2      .1       0
Bank Sta=693.7,784.2
XS Rating Curve= 0 ,0
Exp/Cntr(USF)=0,0
Exp/Cntr=0.3,0.1

Type RM Length L Ch R = 1 ,283998  ,676.5,685.7,680.9
XS GIS Cut Line= 2
2292543.89834637600762.6996859552293726.11125958 601347.83537027
#Sta/Elev= 30
       0  3724.8    43.9 3709.81    58.3 3700.48    71.7 3699.93      94 3688.09
   171.9 3660.87     240 3632.55   326.1 3610.82   366.3 3590.34   549.3 3515.05
   566.3 3509.98   582.7  3508.6   629.6 3510.67     643  3507.9   678.7 3507.73
   692.1 3500.08   696.6 3499.72   817.2 3499.78     838 3509.33   852.9 3512.93
   875.1  3511.5   927.6 3515.11   942.5  3518.6   986.7 3537.95  1080.4 3570.38
  1132.8 3595.36  1157.4 3602.34  1174.1 3611.51  1263.4 3635.43  1319.1 3643.28
#Mann= 5 ,-1,0
       0      .1       0     530     .12       0     580     .06       0
   696.6    .045       0   817.2      .1       0
Bank Sta=696.6,817.2
XS Rating Curve= 0 ,0
Exp/Cntr(USF)=0,0
Exp/Cntr=0.3,0.1

Type RM Length L Ch R = 1 ,283312  ,786.6,769.2,751.6
XS GIS Cut Line= 2
2292213.51561305601327.9327959732293336.02080337601841.419212821
#Sta/Elev= 30
       0 3725.79    77.7 3703.31    95.3 3701.98   232.3 3639.99   337.2 3603.52
   432.6 3566.07   447.2 3557.43   460.4 3553.17   486.8 3529.87     500 3528.59
   513.2 3523.81   526.4 3508.67   543.2 3497.14   636.7  3497.1   639.8 3497.15
   657.9 3504.33   684.7 3510.57   733.1 3507.61   746.3  3509.7   768.3 3506.11
   807.9 3506.87   873.9 3516.48     931 3535.76   957.4 3539.94   988.2 3552.48
  1032.2 3574.73  1146.6 3618.89  1190.6 3629.03    1217 3630.98  1234.4 3635.17
#Mann= 10 ,-1,0
       0      .1       0     180     .12       0     390     .06       0
     500      .1       0   543.2    .045       0   639.8    .025       0
     720      .1       0     830     .12       0     870      .1       0
    1100     .12       0
#XS Ineff= 2 , 0
                          683.32          3536.9
Permanent Ineff=
       F       F
Bank Sta=543.2,639.8
XS Rating Curve= 0 ,0
Exp/Cntr(USF)=0,0
Exp/Cntr=0.3,0.1

Type RM Length L Ch R = 1 ,282543  ,785.3,706.5,642.4
XS GIS Cut Line= 4
 2291876.1257163602541.3084949942292245.35973193602299.178421638
2292734.96305962602335.0030553722293037.48218892602251.412243327
#Sta/Elev= 30
       0 3697.32    62.2 3680.44    89.7 3665.42   112.8 3664.11   144.6 3654.11
   153.1 3649.86   167.5 3638.63   186.6  3629.2   211.8 3624.14   268.8 3603.58
     354 3580.41     419 3553.87     446 3545.16   496.5 3531.83   528.6 3526.66
   572.2 3515.57   717.1 3507.33   737.1 3504.67   749.7 3495.69   756.2 3495.55
   852.6 3495.61   877.5 3508.44     902 3508.28   925.6 3522.91   954.4 3527.37
  1020.9 3547.09    1079 3559.19  1120.3  3574.8  1211.3 3593.03  1246.3 3594.89
#Mann= 7 ,-1,0
       0      .1       0     240     .12       0     310      .1       0
   749.7    .045       0   852.6     .12       0  871.54      .1       0
 1072.46     .12       0
Bank Sta=749.7,852.6
XS Rating Curve= 0 ,0
Exp/Cntr(USF)=0,0
Exp/Cntr=0.3,0.1

Type RM Length L Ch R = 1 ,281837  ,538.9,536.4,535.1
XS GIS Cut Line= 4
2292862.33953512 603178.872205542292949.91086202602908.197195109
 2292961.8524066602522.0872537582293077.28733752602239.470698749
#Sta/Elev= 30
       0  3629.6    66.3 3610.93    82.2 3603.88    94.3 3601.12   140.5  3576.6
   165.7 3565.84   220.4 3548.28     275  3516.6   295.5 3512.74   331.5 3494.05
   335.5 3493.88   415.6 3493.88   495.6 3508.47   503.6 3508.54   515.6 3505.02
   527.6 3506.87   563.6    3506   615.7 3511.19   667.7 3519.66     702 3533.53
     715 3535.54   719.3 3537.93   723.6 3543.59   727.9 3545.44     753 3552.82
   762.5 3557.72   827.3 3580.27   878.8 3590.67   887.8 3590.14   976.1 3599.48
#Mann= 8 ,-1,0
       0      .1       0  334.49    .025       0   335.5    .045       0
   415.6    .025       0  424.49      .1       0  524.49     .12       0
  670.78      .1       0  830.78     .12       0
Bank Sta=335.5,415.6
XS Rating Curve= 0 ,0
Exp/Cntr(USF)=0,0
Exp/Cntr=0.3,0.1

Type RM Length L Ch R = 1 ,281300  ,427.5,450.7,476.9
XS GIS Cut Line= 2
2293507.18294232603250.5214730072293455.43624915602143.938342126
#Sta/Elev= 30
       0 3615.02    33.4 3613.74    77.4 3603.93    92.1 3595.67   105.5  3591.3
   183.1 3577.28   237.7 3562.98   269.6 3550.91   281.6 3548.84   305.7 3536.13
   345.7 3509.41   353.7 3506.35   386.7 3499.95   429.8 3498.85   465.9 3490.96
     566 3490.93     590 3499.21     642 3505.68   662.1 3502.28   698.1 3507.92
   738.7 3509.76   765.4 3520.74   798.2 3526.63   822.2 3538.43   834.3 3541.28
   846.3 3551.49   866.3 3561.58   958.4 3591.72  1010.6 3606.57  1107.8 3620.55
#Mann= 5 ,-1,0
       0      .1       0   465.9    .045       0     566    .025       0
     590     .06       0     780     .12       0
#XS Ineff= 2 , 0
                          645.49         3521.66
Permanent Ineff=
       F       F
Bank Sta=465.9,566
XS Rating Curve= 0 ,0
Exp/Cntr(USF)=0,0
Exp/Cntr=0.3,0.1