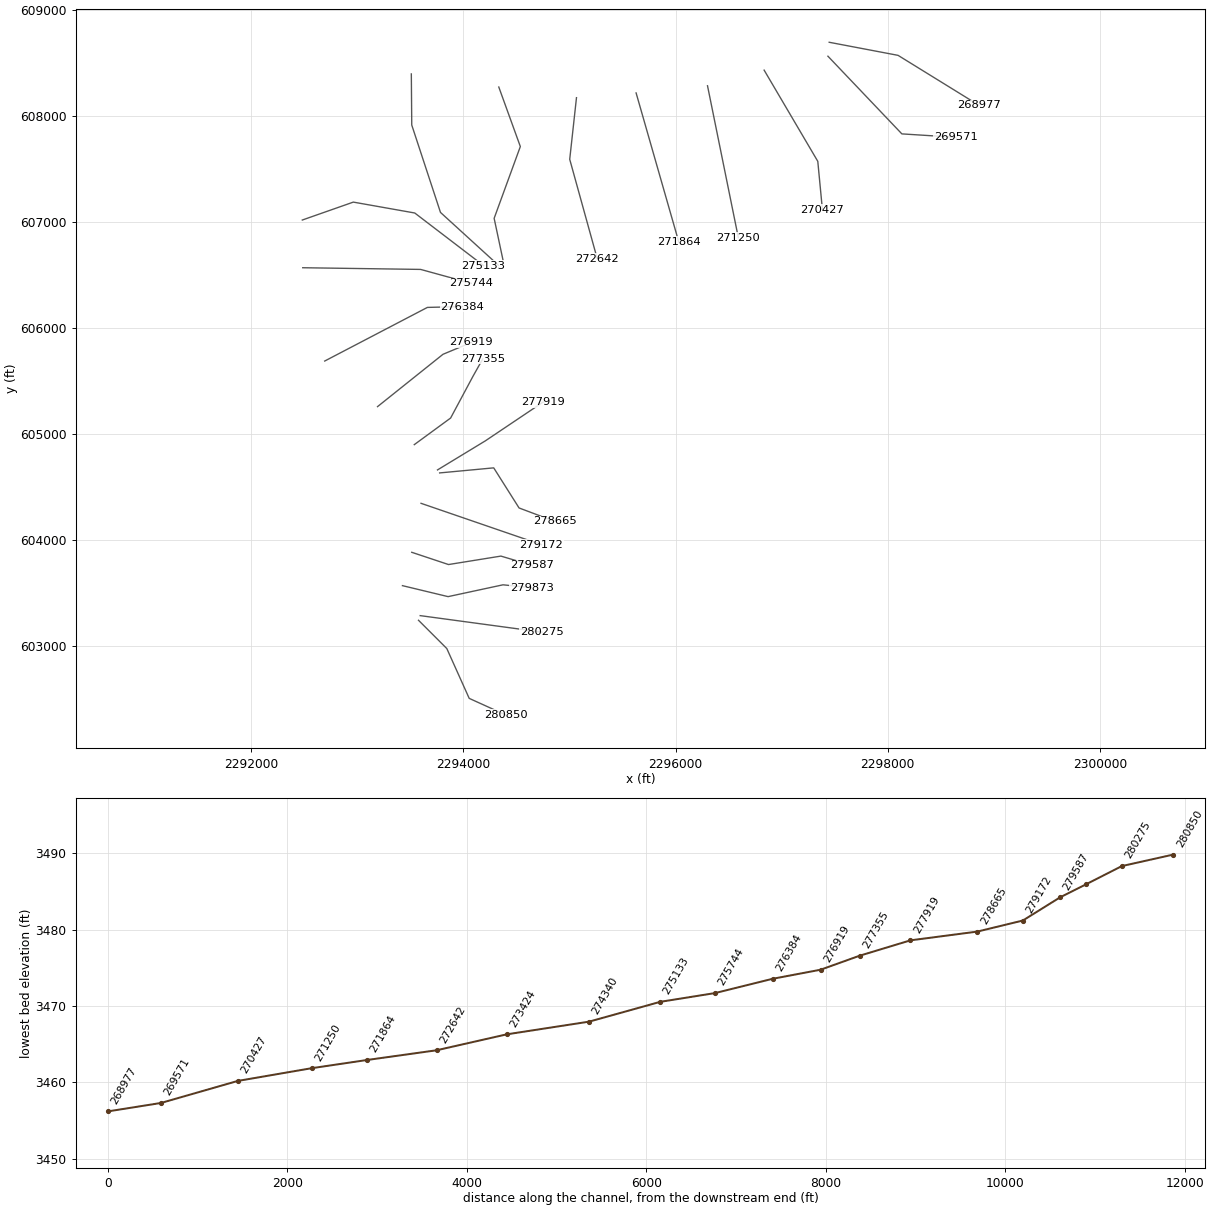
HEC-RAS study SHAVERSFK.prj: SHAVERSFK

--- SHAVERSFK.g01 (geometry) --- (continued)

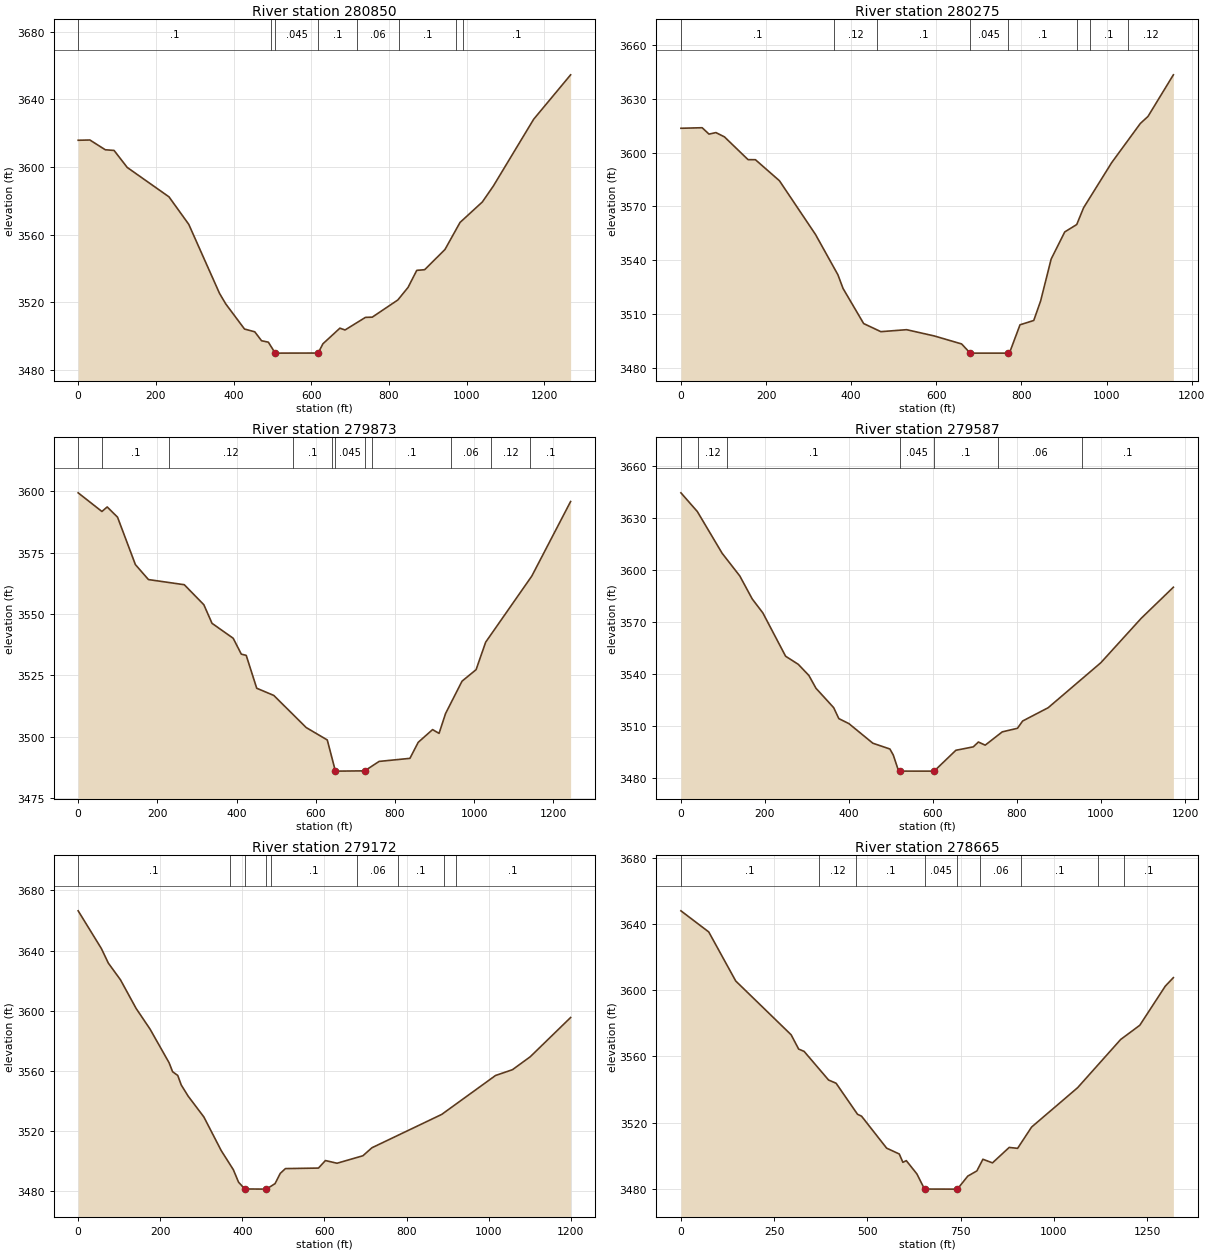
Type RM Length L Ch R = 1 ,280850  ,529.2,574.5,625.6
XS GIS Cut Line= 4
2293578.83220979603242.5604432892293845.52670536602975.865947717
 2294056.4939929602506.165194321 2294398.8182708602350.925114809
#Sta/Elev= 30
       0 3615.84    30.2    3616    69.8 3610.22    92.5 3609.81   126.3 3599.76
   233.9 3582.34   284.8 3566.06   363.9 3525.24   380.1 3518.94   428.3 3504.11
   454.7 3502.47   472.2 3497.18   489.7 3496.34   507.3 3489.85   617.9  3489.9
   630.1 3495.36   673.9 3504.63   687.1 3503.55   739.7 3511.01   757.2 3511.14
     823 3521.31   849.3 3528.73   871.8 3538.84   892.1 3539.23   944.4 3551.19
   983.2  3567.2  1040.6 3579.31  1068.8 3588.69  1172.8 3628.29  1267.9 3654.57
#Mann= 8 ,-1,0
       0      .1       0  497.16    .025       0   507.3    .045       0
   617.9      .1       0  717.16     .06       0  827.16      .1       0
  972.07     .12       0  992.07      .1       0
Bank Sta=507.3,617.9
XS Rating Curve= 0 ,0
Exp/Cntr(USF)=0,0
Exp/Cntr=0.3,0.1

Type RM Length L Ch R = 1 ,280275  ,384.9,402.3,420.3
XS GIS Cut Line= 2
2293594.75426922603286.346106741 2294741.1425487603131.106027229
#Sta/Elev= 30
       0 3613.53    49.9 3613.84      66 3610.28    82.2 3611.13   102.3 3608.74
   157.7 3596.07     175 3596.03   231.5 3584.31   316.3 3554.35   368.8 3531.97
   380.9 3524.34   429.3  3504.8   469.7 3500.29   530.2 3501.39   594.8 3497.93
   659.4 3493.46   679.6 3488.34   768.4 3488.34   772.4 3488.75   796.6 3504.11
   828.9 3506.52   845.1 3517.43   869.7 3540.67   901.7 3555.82   929.8 3559.92
     946 3569.28  1011.9 3594.38  1079.2 3616.18  1097.3 3620.14  1156.9 3643.29
#Mann= 8 ,-1,0
       0      .1       0     360     .12       0     460      .1       0
   679.6    .045       0   768.4      .1       0     930     .06       0
     960      .1       0    1050     .12       0
Bank Sta=679.6,768.4
XS Rating Curve= 0 ,0
Exp/Cntr(USF)=0,0
Exp/Cntr=0.3,0.1

Type RM Length L Ch R = 1 ,279873  ,287.4,285.9,283.7
XS GIS Cut Line= 4
2293427.57264513 603568.962661752293857.46824994603465.469275408
2294374.93518164603576.9236914682294645.61019207603549.060087453
#Sta/Elev= 30
       0 3599.44      60 3591.83    73.3 3593.68    99.4 3589.52   144.6 3570.15
   177.5 3564.06     268 3561.96   317.4  3553.8     338 3546.22   391.5 3540.12
     412 3533.64   424.4 3533.15   450.9 3519.74     494 3516.81   575.9  3503.7
   629.1 3498.64   649.5    3486   652.9 3485.93   723.6 3486.04     760 3489.89
   837.8 3491.14   858.7 3497.67     895 3502.87   911.4 3501.33   927.8 3509.42
   969.4 3522.62  1004.9 3527.32  1029.1 3538.53  1145.7 3565.52  1243.6  3595.9
#Mann= 11 ,-1,0
       0     .12       0      60      .1       0     230     .12       0
  542.18      .1       0  642.18    .025       0   649.5    .045       0
   723.6    .025       0  742.18      .1       0  942.18     .06       0
 1041.51     .12       0 1141.51      .1       0
Bank Sta=649.5,723.6
XS Rating Curve= 0 ,0
Exp/Cntr(USF)=0,0
Exp/Cntr=0.3,0.1

Type RM Length L Ch R = 1 ,279587  ,426.7,415,399.8
XS GIS Cut Line= 4
2293515.14397204603883.423335633 2293861.4487648603767.988404714
2294355.03260735  603847.59870192294649.59070693603760.027374995
#Sta/Elev= 30
       0 3644.76      39 3633.99    98.1 3609.91   140.2  3596.8   169.7 3583.56
     195 3575.52   249.2 3550.52   279.4 3545.84   304.7  3539.4   321.5 3532.04
   363.7 3520.83   375.9 3514.53   399.9 3511.65   456.9 3500.34   497.5    3497
   505.6 3493.48   517.7 3484.67   521.8 3484.25   602.8 3484.24   654.5 3496.26
     696 3498.24   708.1 3501.02   724.4 3499.23   764.9 3506.88   801.1 3508.95
   813.5 3513.15   874.3 3520.82   999.7 3546.78  1095.7 3572.37  1172.3 3590.31
#Mann= 7 ,-1,0
       0      .1       0      40     .12       0     110      .1       0
   521.8    .045       0   602.8      .1       0  755.04     .06       0
     955      .1       0
Bank Sta=521.8,602.8
XS Rating Curve= 0 ,0
Exp/Cntr(USF)=0,0
Exp/Cntr=0.3,0.1

Type RM Length L Ch R = 1 ,279172  ,525.3,506.8,485.9
XS GIS Cut Line= 2
2293602.71529894 604345.163059312294737.16203384  603955.0726031
#Sta/Elev= 30
       0 3666.44    56.5 3641.36    73.5 3631.65   103.1 3620.51   141.1  3601.5
     175 3587.76   221.5 3565.32     230 3559.36   242.6 3556.86   251.1 3550.53
     268 3543.07   306.1 3529.28   348.4  3506.9     378 3494.14   390.7 3485.83
   405.9 3481.32   458.4  3481.2   479.6 3484.85   492.3 3491.67   504.9 3494.87
   585.3 3495.21   602.3 3500.22   630.6 3498.43   693.6 3503.41   715.6 3508.73
   885.6 3530.93  1016.7 3556.84  1057.9 3560.69  1101.3 3569.32  1199.6 3595.43
#Mann= 9 ,-1,0
       0      .1       0     370    .025       0   405.9    .045       0
   458.4    .025       0     470      .1       0     680     .06       0
     780      .1       0     890     .12       0     920      .1       0
Bank Sta=405.9,458.4
XS Rating Curve= 0 ,0
Exp/Cntr(USF)=0,0
Exp/Cntr=0.3,0.1

Type RM Length L Ch R = 1 ,278665  ,680.8,745.9,815.9
XS GIS Cut Line= 4
2293777.85795275604631.7601291782294287.36385474 604679.52630749
 2294526.1947463604301.3773958582294864.53850934604174.000920361
#Sta/Elev= 30
       0 3647.95    74.6  3635.2     147 3605.54   295.6 3573.02   315.7  3564.4
   330.3 3563.01     396 3545.68   416.1 3543.75   473.6 3524.98   484.4 3523.83
   551.7  3504.5   585.5 3500.99   595.2 3495.96   604.4 3496.97   632.8 3488.92
   653.2  3479.8   736.9 3479.75   741.6 3479.84   769.2 3487.62   793.6 3490.77
   809.8 3497.81   835.4 3495.62   880.3 3504.95   902.8  3504.4   940.3 3517.26
  1063.7 3541.04  1179.1 3570.18  1230.4 3578.77  1298.8 3602.43  1320.5 3607.56
#Mann= 9 ,-1,0
       0      .1       0     370     .12       0     470      .1       0
   653.2    .045       0   741.6    .025       0  801.74     .06       0
  911.74      .1       0 1118.99     .12       0 1188.99      .1       0
Bank Sta=653.2,741.6
XS Rating Curve= 0 ,0
Exp/Cntr(USF)=0,0
Exp/Cntr=0.3,0.1

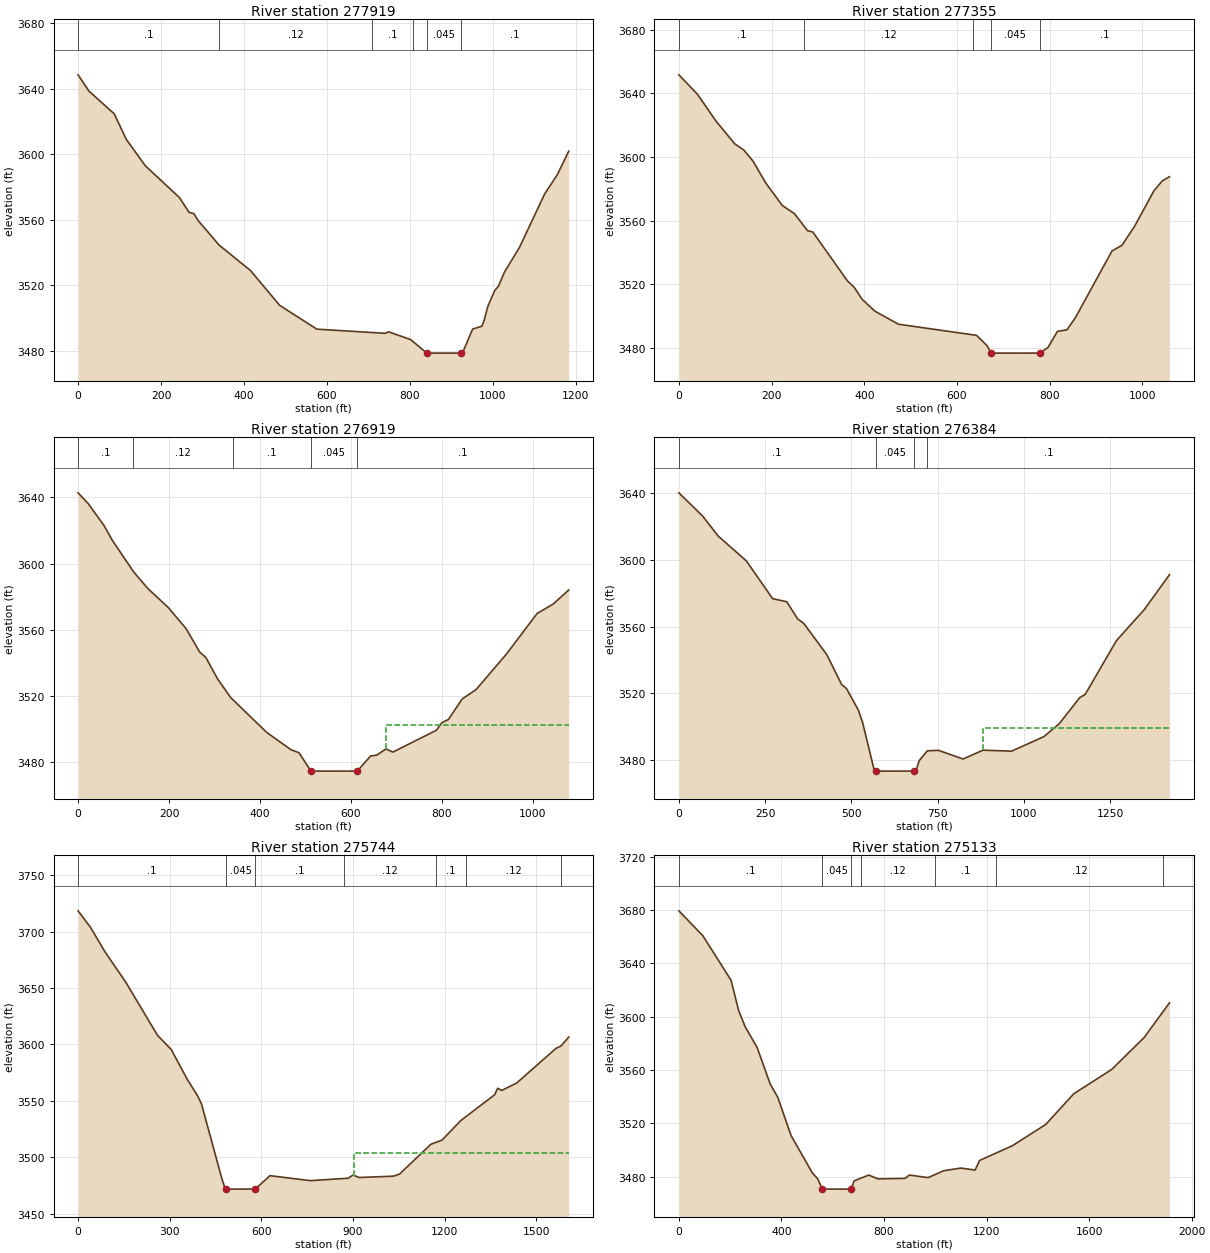
Type RM Length L Ch R = 1 ,277919  ,543.7,564.3,583.7
XS GIS Cut Line= 3
2293757.67954498604660.0282889572294209.20189116604934.518314162
2294752.47835697605299.515305953
#Sta/Elev= 30
       0 3648.63    26.3 3638.67    87.2 3624.79   116.2 3609.23   162.1 3593.07
   244.3 3573.67   267.6 3564.61   279.2 3563.84   288.5 3559.89     340  3544.6
   416.1 3528.96   485.9 3507.81   575.7 3493.24     740 3490.71   748.8  3491.6
   801.9 3486.86   840.9  3478.6   922.3 3478.62   927.4 3479.07   951.2 3493.32
   973.5 3495.01   979.2 3498.86   987.9 3507.23  1004.2 3516.66  1013.9 3519.77
  1028.3 3528.31    1064  3543.1  1124.7 3575.78  1155.1 3587.52  1182.9 3601.99
#Mann= 6 ,-1,0
       0      .1       0     340     .12       0  708.41      .1       0
  808.41     .12       0   840.9    .045       0   922.3      .1       0
Bank Sta=840.9,922.3
XS Rating Curve= 0 ,0
Exp/Cntr(USF)=0,0
Exp/Cntr=0.3,0.1

Type RM Length L Ch R = 1 ,277355  ,457.5,436.3,417.5
XS GIS Cut Line= 4
2293539.02706119 604898.454624752293881.35133909605149.227060885
2294092.31862663605543.298031954 2294183.8704684605706.499141185
#Sta/Elev= 30
       0  3651.7      40 3639.52      80 3622.65   120.4 3608.32   140.3 3604.34
   160.2 3597.28   187.4 3583.69   223.1  3569.5   249.3 3564.35   277.5 3553.66
     289 3552.78   363.4 3522.15   378.3 3518.01   394.9 3510.56   422.9    3503
   473.7 3494.78   642.2 3487.77   664.8 3481.28   673.8 3476.59   778.2 3476.62
   796.3 3480.15   816.5 3490.22   837.2 3491.28   855.3 3498.83   934.3 3540.84
   956.1  3544.5   983.6 3556.65  1024.8 3578.73  1042.7 3584.96  1058.5  3587.6
#Mann= 5 ,-1,0
       0      .1       0     270     .12       0  634.35    .025       0
   673.8    .045       0   778.2      .1       0
Bank Sta=673.8,778.2
XS Rating Curve= 0 ,0
Exp/Cntr(USF)=0,0
Exp/Cntr=0.3,0.1

Type RM Length L Ch R = 1 ,276919  ,544.4,534.5,522.1
XS GIS Cut Line= 3
2293192.72226844605256.7009620852293809.70207163605750.284804637
 2294076.3965672605861.739220696
#Sta/Elev= 30
       0 3642.79    22.7 3636.16    56.9 3623.11    76.1 3613.77   122.2 3595.07
     153 3585.13   199.1 3573.33   237.7 3560.77   267.5 3546.63     281 3543.41
   306.6 3530.54   335.8 3519.11   415.4 3498.02   468.2 3487.69   485.9 3485.87
   512.2 3474.75     614 3474.78   643.1 3483.78   657.3 3484.47   677.3 3488.19
   692.3 3486.24   788.2 3499.45   800.3 3504.04   814.5 3505.92   844.8 3518.32
   875.2 3523.92   942.9 3545.68  1009.6 3569.93  1044.9 3575.61  1079.2 3584.12
#Mann= 5 ,-1,0
       0      .1       0     120     .12       0     340      .1       0
   512.2    .045       0     614      .1       0
#XS Ineff= 2 , 0
                          677.55         3502.76
Permanent Ineff=
       F       F
Bank Sta=512.2,614
XS Rating Curve= 0 ,0
Exp/Cntr(USF)=0,0
Exp/Cntr=0.3,0.1

Type RM Length L Ch R = 1 ,276384  ,665.4,640.3,616.6
XS GIS Cut Line= 3
2292695.15791103605686.5965668882293662.42302183606192.121954017
2293992.80575515606200.082983735
#Sta/Elev= 30
       0 3639.93    68.8 3626.05     114 3614.07   195.6 3599.23   271.9 3576.61
   312.6 3574.85   344.2 3564.57   362.2 3561.81   428.7 3543.19   471.9 3525.27
   485.8 3522.89   520.2 3510.01   532.4 3502.67   565.3  3474.8   569.8 3473.56
   682.7 3473.59   687.2 3473.74   696.3 3479.81     720 3485.71   752.6 3485.97
   823.7  3480.8   881.3 3486.08   964.1 3485.49  1057.9 3494.19    1102 3501.84
  1161.8 3517.53  1177.2 3519.34  1268.4 3551.67  1349.2 3570.25  1421.9 3591.07
#Mann= 4 ,-1,0
       0      .1       0   569.8    .045       0   682.7    .025       0
     720      .1       0
#XS Ineff= 2 , 0
                           882.6          3499.1
Permanent Ineff=
       F       F
Bank Sta=569.8,682.7
XS Rating Curve= 0 ,0
Exp/Cntr(USF)=0,0
Exp/Cntr=0.3,0.1

Type RM Length L Ch R = 1 ,275744  ,619.7,611.1,602.6
XS GIS Cut Line= 3
2292488.17113834 606566.290350792293598.73478408606550.368291352
 2294076.3965672606419.011300996
#Sta/Elev= 30
       0 3718.47      40 3704.12      88 3682.14     156 3655.28     260 3608.05
   304.8 3595.58     356 3569.71   392.6 3553.76     404 3547.17   470.4 3481.27
   480.1 3473.07   484.1 3471.69   580.1 3471.76   628.1 3483.62   760.1 3479.22
   884.1 3481.35   900.1 3484.22   920.1    3482  1032.1 3483.18  1052.1 3485.01
  1155.1 3511.52    1191 3515.12  1253.2 3532.59  1363.4 3555.32  1373.5 3561.12
  1386.7  3559.2  1435.8  3565.8  1564.4 3596.53    1581 3598.67  1606.1 3606.53
#Mann= 7 ,-1,0
       0      .1       0   484.1    .045       0   580.1      .1       0
     870     .12       0 1170.68      .1       0 1270.68     .12       0
 1580.68      .1       0
#XS Ineff= 2 , 0
                          904.55         3503.79
Permanent Ineff=
       F       F
Bank Sta=484.1,580.1
XS Rating Curve= 0 ,0
Exp/Cntr(USF)=0,0
Exp/Cntr=0.3,0.1

Type RM Length L Ch R = 1 ,275133  ,846.9,793.3,725.3
XS GIS Cut Line= 4
2292484.19062348607016.088529888 2292964.7568405607184.963554963
2293543.48994413607082.2460477212294191.83149812606586.192925086
#Sta/Elev= 30
       0 3679.44    93.3 3660.78   203.5 3627.37   233.2 3604.45   258.6 3592.42
   305.2 3576.84   356.1 3549.46   385.8  3539.4   437.6 3510.73     521 3482.55
   541.3 3478.32559.48753470.601   671.3 3470.54671.55653470.596   683.5 3476.74
   740.3 3481.08   776.9 3478.25   882.5  3478.6   898.8 3481.11   971.9 3479.18
  1032.8 3484.35  1098.9 3486.34  1155.5 3484.87  1172.6 3492.05    1301 3503.16
  1430.4 3519.05  1540.7 3542.23  1687.3 3560.27  1814.6 3584.36  1913.5 3610.43
#Mann= 7 ,-1,0
       0      .1       0559.4875    .045       0671.5565      .1       0
  709.37     .12       0  999.37      .1       0 1237.15     .12       0
 1887.15      .1       0
Bank Sta=559.4875,671.5565
XS Rating Curve= 0 ,0
Exp/Cntr(USF)=0,0
Exp/Cntr=0.3,0.1

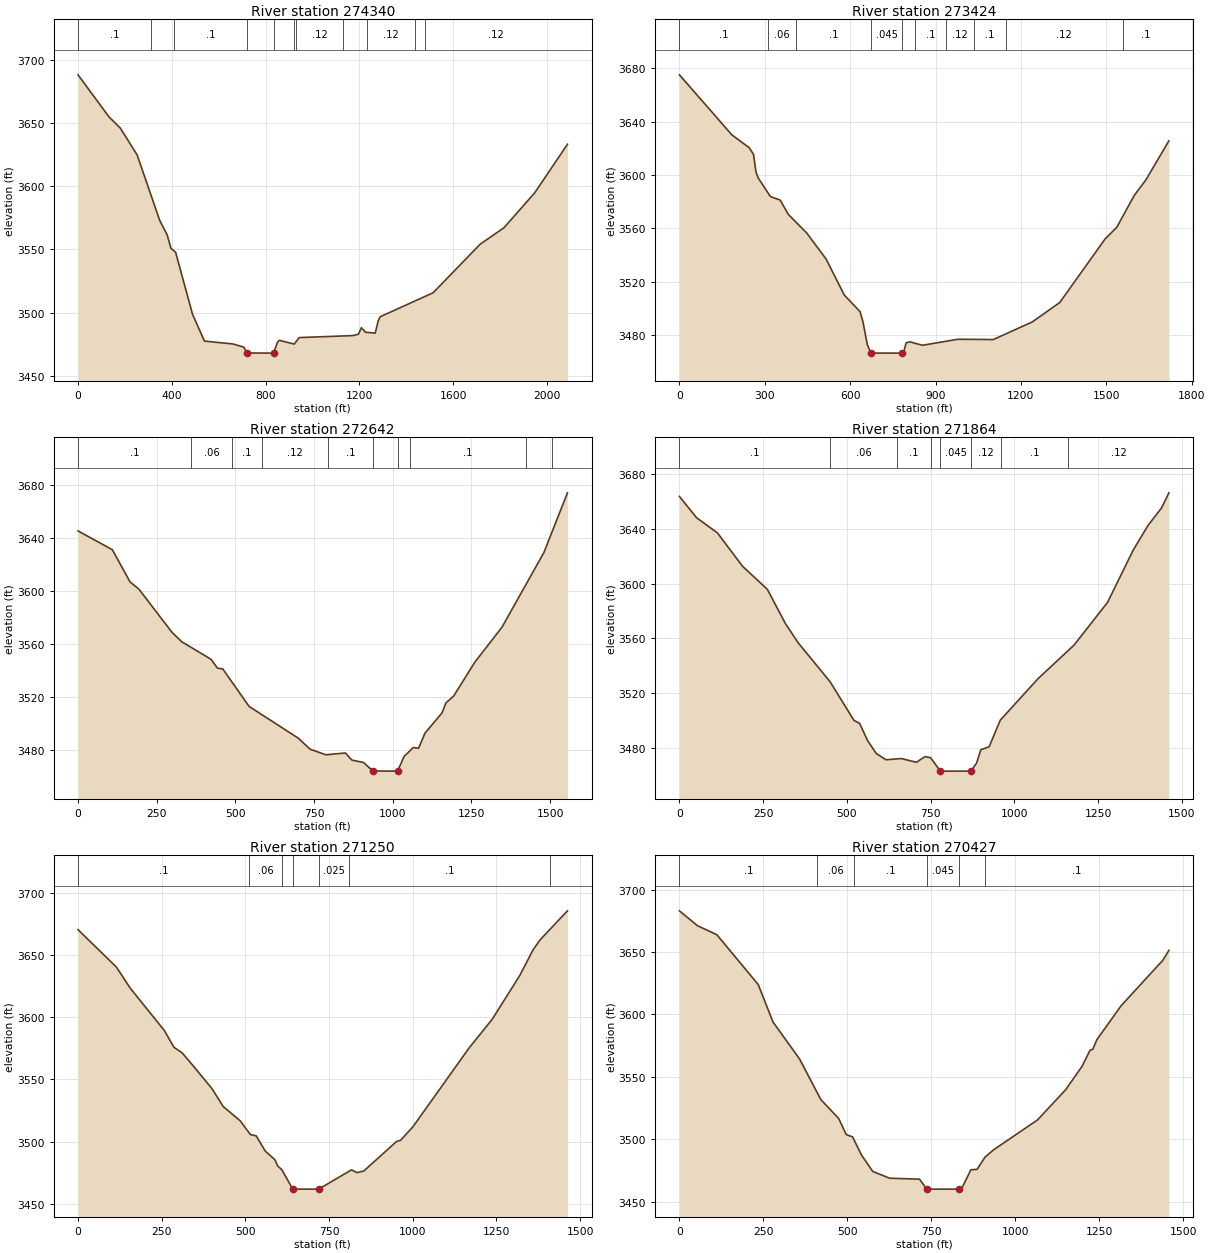
Type RM Length L Ch R = 1 ,274340  ,948,915.6,873.1
XS GIS Cut Line= 4
2293511.16345718  608393.34667122293515.14397204607911.704373227
2293785.81898247607087.7377973562294331.14951819606590.173439945
#Sta/Elev= 30
       0 3688.24   132.1 3654.97   180.2 3646.12   252.2 3624.82   348.2 3573.11
   380.2 3561.56   396.2 3550.93   416.2 3547.78   488.5 3498.66   539.1 3477.46
   661.1 3475.19   707.5 3472.65   720.1 3468.08   833.8 3467.94   850.6 3476.55
   858.4 3478.06   922.2 3475.09   943.2 3480.25  1172.2 3481.82  1195.9 3482.91
  1208.5 3488.08  1226.1 3484.49  1267.3 3483.75  1279.9 3493.29  1288.5 3496.72
  1514.6 3515.75  1714.8 3554.12  1816.8 3567.26  1947.8  3594.9  2087.2 3633.27
#Mann= 11 ,-1,0
       0      .1       0     310     .06       0     410      .1       0
   720.1    .045       0   833.8     .12       0  921.66      .1       0
  931.66     .12       0 1131.66      .1       0 1231.66     .12       0
 1438.95      .1       0 1478.95     .12       0
Bank Sta=720.1,833.8
XS Rating Curve= 0 ,0
Exp/Cntr(USF)=0,0
Exp/Cntr=0.3,0.1

Type RM Length L Ch R = 1 ,273424  ,755.8,782.1,795.1
XS GIS Cut Line= 4
2294335.13003305608269.9507105632294538.13629087607708.698115404
 2294291.3443696607032.0105893262294374.93518164606637.939618257
#Sta/Elev= 30
       0 3675.18   183.7 3630.22   245.1 3620.46   260.3 3615.46   268.8  3602.5
   276.3 3597.93   319.8 3583.78   353.9 3581.17   382.5 3570.45   447.5 3556.38
   515.5 3536.85   579.3 3509.87   634.6 3497.47   644.8 3489.91   660.4 3472.45
     673 3466.34   783.7 3466.28   787.9 3466.77   796.4 3473.96   809.2 3474.79
   854.1 3472.17   978.6  3476.7    1103 3476.48  1239.2 3489.61  1336.4 3504.24
  1495.8    3552  1536.7 3560.69  1598.1 3584.58    1639 3596.27    1720 3625.63
#Mann= 10 ,-1,0
       0      .1       0     310     .06       0     410      .1       0
     673    .045       0   783.7    .025       0  826.84      .1       0
  936.84     .12       0 1036.84      .1       0 1146.84     .12       0
 1557.12      .1       0
Bank Sta=673,783.7
XS Rating Curve= 0 ,0
Exp/Cntr(USF)=0,0
Exp/Cntr=0.3,0.1

Type RM Length L Ch R = 1 ,272642  ,777.5,778,778.3
XS GIS Cut Line= 3
2295067.08600622608169.5911385882295003.39776847607588.435969133
2295262.13123432606653.014977201
#Sta/Elev= 30
       0 3645.63   109.1 3631.42   165.4 3607.08   193.6 3601.64   298.2 3569.17
   329.4 3561.93   422.9 3548.61     443    3542     460 3541.38   543.6 3513.07
   700.1 3489.05   737.4 3480.75   787.2 3476.54   849.5 3477.91   870.2  3472.5
   907.6 3470.69   936.6 3464.29  1011.3 3464.19  1015.5  3464.3  1036.2 3475.29
  1065.3 3482.03  1082.1 3481.45  1102.6  3492.9  1156.6 3508.16    1169 3515.71
  1193.9 3520.97  1260.3 3546.28  1347.5 3573.03  1480.3 3629.25  1555.2 3674.39
#Mann= 10 ,-1,0
       0      .1       0     360     .06       0     490      .1       0
  584.63     .12       0  794.63      .1       0   936.6    .045       0
  1015.5    .025       0 1054.63      .1       0 1424.63     .12       0
 1504.63      .1       0
Bank Sta=936.6,1015.5
XS Rating Curve= 0 ,0
Exp/Cntr(USF)=0,0
Exp/Cntr=0.3,0.1

Type RM Length L Ch R = 1 ,271864  ,617.7,613.5,612.6
XS GIS Cut Line= 2
2295628.79736232608214.2235025332296030.82936311606809.101757206
#Sta/Elev= 30
       0  3663.6      51 3648.08   113.4 3636.99   188.3 3612.61   262.4 3595.78
   317.1 3570.45   354.7 3556.62     450 3528.17   521.1 3499.97   537.8 3497.87
   561.9 3485.23   587.7 3475.78   616.8 3471.22   662.6  3472.1   707.6 3469.37
   733.3 3473.52     750 3472.68   779.1 3462.91   870.5 3462.91   887.3 3468.79
   899.9 3478.54   924.7 3480.72   957.9 3500.12  1070.3 3530.34  1178.5 3555.06
  1278.4 3586.24  1354.5  3624.2    1399 3642.38  1439.9 3655.34  1461.5 3666.25
#Mann= 8 ,-1,0
       0      .1       0     450     .06       0     650      .1       0
     750    .025       0   779.1    .045       0   870.5     .12       0
     960      .1       0    1160     .12       0
Bank Sta=779.1,870.5
XS Rating Curve= 0 ,0
Exp/Cntr(USF)=0,0
Exp/Cntr=0.3,0.1

Type RM Length L Ch R = 1 ,271250  ,803.2,823.1,837
XS GIS Cut Line= 2
2296301.50437354 608281.892255142296592.08195826606848.906905799
#Sta/Elev= 30
       0 3670.27   114.9 3640.13   155.8 3623.36   257.9 3589.25   286.4 3575.85
   310.9 3571.35   343.6 3561.03   400.7 3542.38   433.8 3528.17   484.7 3516.69
     515 3505.68   532.2 3504.63   559.4 3492.42   588.5 3485.39   596.6  3480.4
   608.9 3477.45   641.5 3461.84   719.1 3461.84     817 3477.34   833.3 3475.11
   853.7  3476.4   951.7 3500.14   963.2    3501  1000.7    3512    1168 3575.13
  1237.4 3598.31  1319.5 3633.37  1359.8 3654.26  1380.2 3662.02  1462.1 3685.38
#Mann= 7 ,-1,0
       0      .1       0     510     .06       0     610    .025       0
   641.5    .045       0   719.1    .025       0     810      .1       0
    1410     .12       0
Bank Sta=641.5,719.1
XS Rating Curve= 0 ,0
Exp/Cntr(USF)=0,0
Exp/Cntr=0.3,0.1

Type RM Length L Ch R = 1 ,270427  ,850,856.1,860.6
XS GIS Cut Line= 3
2296834.89336468608429.1713049342297340.41875181607569.380095329
2297384.20441526607111.620886511
#Sta/Elev= 30
       0    3683    53.5 3671.12   111.4 3663.86   234.7 3623.92   278.4 3594.03
   357.3 3564.54   420.8 3531.91   474.3 3516.67   496.5 3503.87   515.5 3502.01
   541.5 3487.71   575.4 3474.34     626 3468.91   714.6 3468.15   736.5 3460.17
   833.7 3460.18   839.6 3460.27   867.7 3475.66   886.3 3476.04   909.5  3485.7
     936 3491.77  1065.9 3515.53  1150.3 3539.89  1199.1 3558.71  1222.6 3571.49
  1230.7 3572.15  1242.7 3579.81    1315 3607.02  1439.6 3643.53  1457.2 3651.33
#Mann= 6 ,-1,0
       0      .1       0     410     .06       0     520      .1       0
   736.5    .045       0   833.7     .12       0     910      .1       0
Bank Sta=736.5,833.7
XS Rating Curve= 0 ,0
Exp/Cntr(USF)=0,0
Exp/Cntr=0.3,0.1

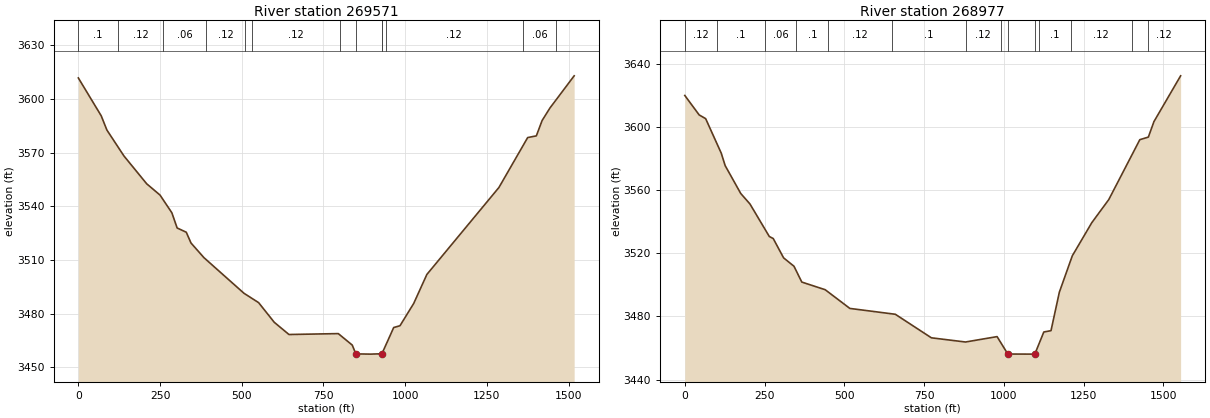
Type RM Length L Ch R = 1 ,269571  ,581.5,593.8,602.6
XS GIS Cut Line= 3
2297435.95110843 608560.528295292298132.54120881607828.113561182
2298638.06659594607796.269442308
#Sta/Elev= 30
       0 3611.84      70 3590.66    87.4 3582.68   139.6 3568.18   209.3 3552.58
   249.9 3546.31   286.2  3536.4   302.4 3527.86   330.3 3525.51   344.9 3519.44
   384.5 3511.25     507 3491.32   551.7  3486.1   599.5 3475.11   644.6 3468.26
   795.5 3468.76   838.2 3462.35   849.2 3457.42   894.2 3457.28     929 3457.48
   965.1 3472.17   984.3 3473.17  1026.4 3485.67  1066.5 3501.85    1287 3550.51
  1375.1 3578.47  1401.6 3579.42  1419.2    3588    1443 3594.96  1517.3 3613.02
#Mann= 13 ,-1,0
       0      .1       0     120     .12       0     260     .06       0
     390     .12       0     510      .1       0     530     .12       0
     800      .1       0   849.2    .045       0     929      .1       0
     930    .025       0     940     .12       0 1360.78     .06       0
 1460.78     .12       0
Bank Sta=849.2,929
XS Rating Curve= 0 ,0
Exp/Cntr(USF)=0,0
Exp/Cntr=0.3,0.1

Type RM Length L Ch R = 1 ,268977  ,515.9,557.6,585.3
XS GIS Cut Line= 3
2297447.89265301608691.8852856472298096.71657507608568.489325009
 2298856.9949132608098.788571613
#Sta/Elev= 30
       0 3619.81    45.1 3607.49    65.4 3605.14   114.3 3583.28   126.5 3575.44
   175.4 3557.79   204.4 3551.12   264.9 3530.58   277.2 3529.29   309.7 3517.07
   342.3 3511.75   366.7 3501.76     440 3496.92   517.4 3485.08   659.9 3481.38
   772.9 3466.49   879.8 3463.84   978.8 3467.25  1012.5 3456.23  1097.1 3456.17
  1125.3 3470.18  1147.8 3471.01    1174 3495.36  1214.6 3518.37  1275.6  3539.3
  1328.9 3553.94  1426.2 3591.83    1453 3593.48  1470.4 3603.24  1554.1 3632.23
#Mann= 14 ,-1,0
       0     .12       0     100      .1       0     250     .06       0
     350      .1       0     450     .12       0     650      .1       0
  880.45     .12       0  990.45      .1       0  1012.5    .045       0
  1097.1     .12       0 1110.45      .1       0 1210.45     .12       0
 1400.45     .06       0 1450.45     .12       0
Bank Sta=1012.5,1097.1
XS Rating Curve= 0 ,0
Exp/Cntr(USF)=0,0
Exp/Cntr=0.3,0.1