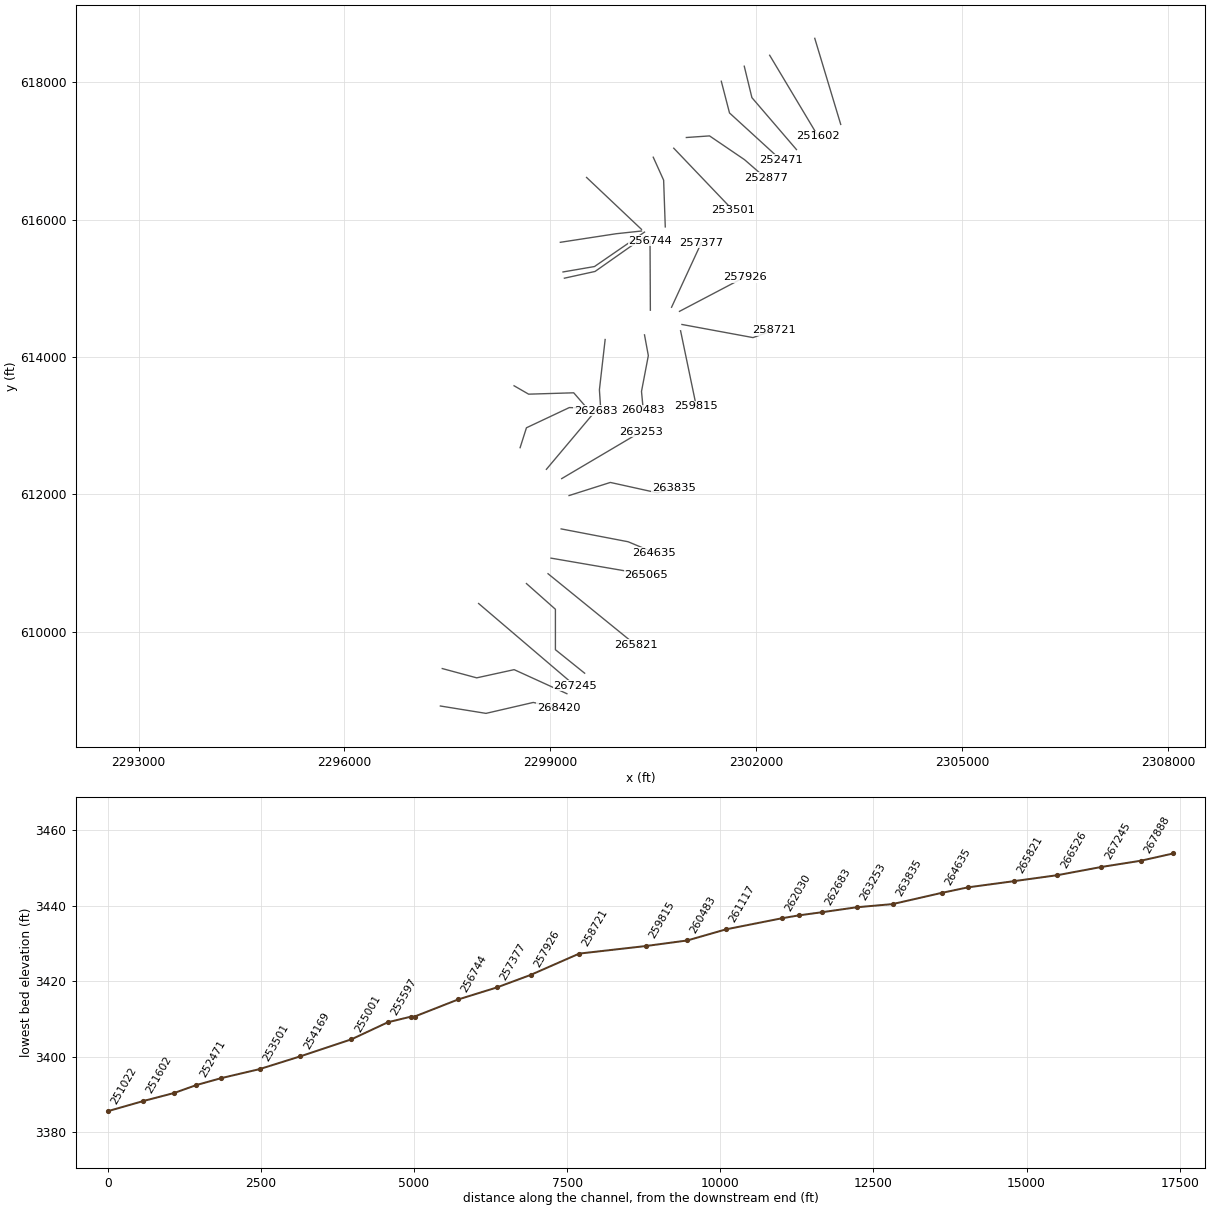
HEC-RAS study SHAVERSFK.prj: SHAVERSFK

--- SHAVERSFK.g01 (geometry) --- (continued)

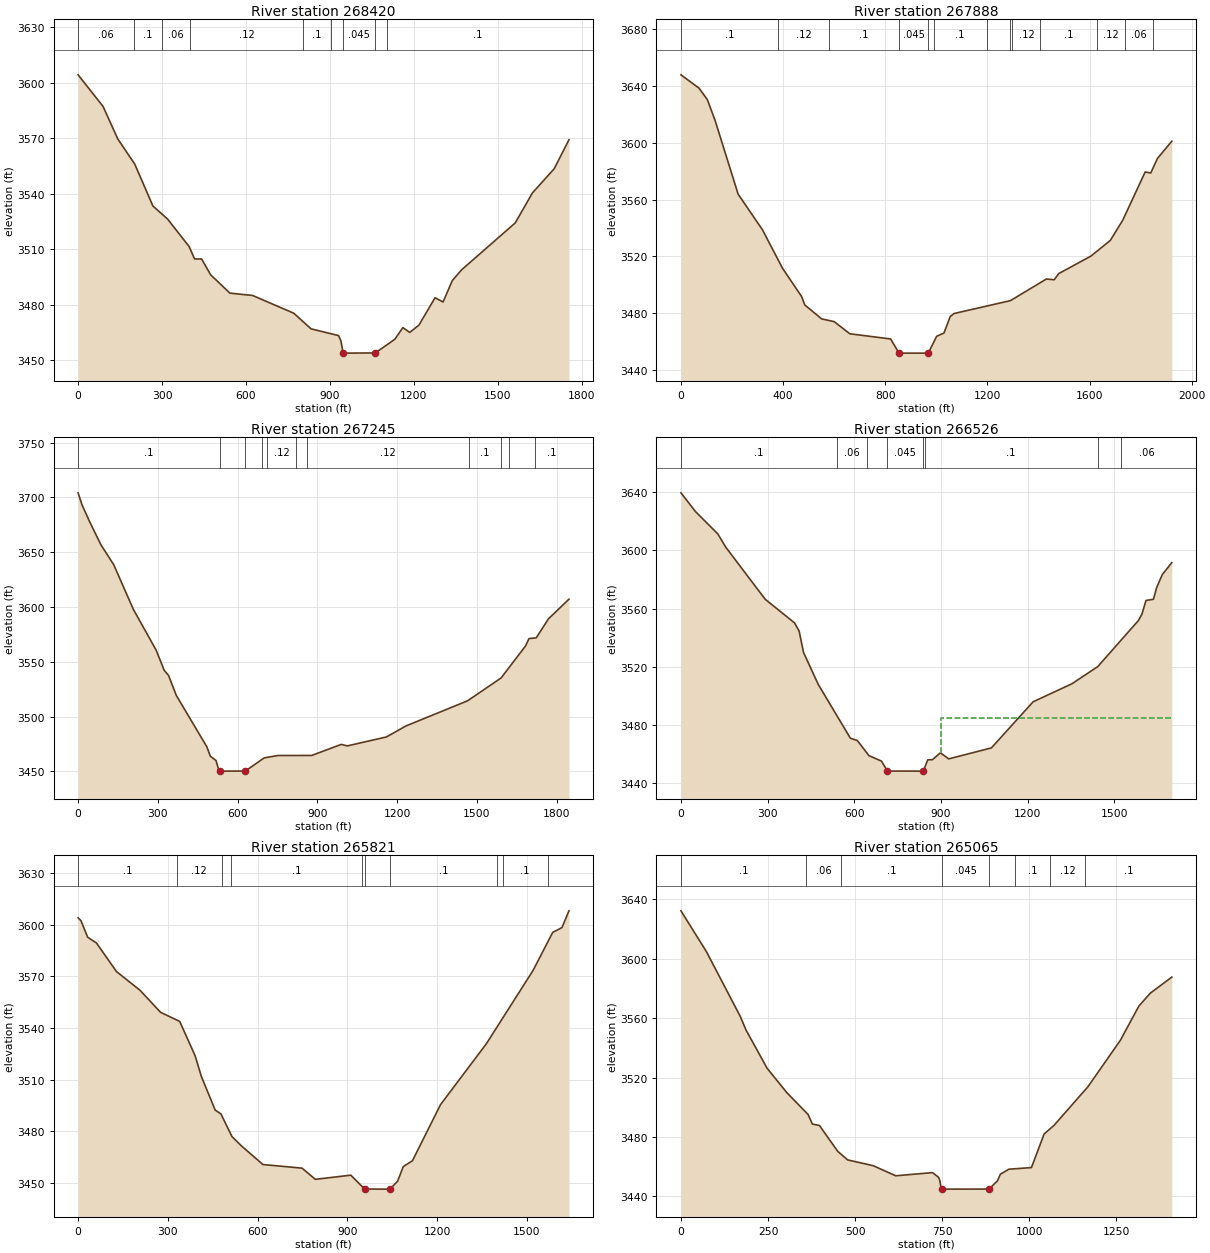
Type RM Length L Ch R = 1 ,268420  ,533.2,531.6,532
XS GIS Cut Line= 4
2297396.14595984608918.7746326262298060.89194134608811.300731425
  2298749.521012608970.5213257962299115.72837905608890.911028611
#Sta/Elev= 30
       0  3604.2    89.2 3587.16   141.8  3569.6   202.6 3555.98   267.5 3533.36
   320.1 3526.28   397.1 3511.43   416.5 3504.76   441.7 3504.72   474.1 3496.15
     543 3486.28     624 3485.02   771.2 3475.43   832.8    3467   931.3 3463.35
   939.5  3460.6   947.7 3453.88  1062.7 3453.98  1132.5 3461.38  1161.2 3467.66
  1185.8 3465.08  1218.7 3469.04  1276.2  3483.8  1304.9  3481.5  1337.7 3493.03
  1370.6 3498.81    1563 3524.23  1624.4 3540.43  1702.2 3553.48  1754.9 3569.12
#Mann= 9 ,-1,0
       0     .06       0     200      .1       0     300     .06       0
     400     .12       0  803.38      .1       0  903.38     .12       0
   947.7    .045       0  1062.7     .12       0 1103.38      .1       0
Bank Sta=947.7,1062.7
XS Rating Curve= 0 ,0
Exp/Cntr(USF)=0,0
Exp/Cntr=0.3,0.1

Type RM Length L Ch R = 1 ,267888  ,698,642.9,604.1
XS GIS Cut Line= 4
2297424.00956385609464.1051683472297925.55443612609328.767663132
2298470.88497185 609448.183108912299239.12433969609097.897801293
#Sta/Elev= 30
       0 3647.79    70.6 3638.46   103.4 3630.37   134.1 3615.47   223.9  3563.8
   319.2 3538.73   397.9 3511.61   472.5 3491.79   484.9 3485.85   550.8 3476.05
     600  3474.1   661.4 3465.56   821.1 3461.91   853.8 3451.94   968.5 3451.94
  1001.3 3463.81  1029.9 3466.07  1054.5 3477.72  1069.6 3479.82  1290.2 3488.88
  1430.8 3504.08  1461.6 3503.58  1479.2  3507.9  1605.6 3520.26  1681.4 3531.29
  1730.2 3545.57  1817.7 3579.41  1839.7 3578.72    1866 3588.99  1922.1 3601.06
#Mann= 13 ,-1,0
       0      .1       0     380     .12       0  579.48      .1       0
   853.8    .045       0   968.5    .025       0  989.48      .1       0
 1197.74     .12       0 1287.74      .1       0 1297.74     .12       0
 1407.74      .1       0 1627.74     .12       0 1737.74     .06       0
 1847.74      .1       0
Bank Sta=853.8,968.5
XS Rating Curve= 0 ,0
Exp/Cntr(USF)=0,0
Exp/Cntr=0.3,0.1

Type RM Length L Ch R = 1 ,267245  ,767.2,719.3,684.1
XS GIS Cut Line= 2
2297953.41804014610411.4677048572299358.53978547609213.332732213
#Sta/Elev= 30
       0 3704.25    14.9 3693.23    43.3 3677.98    85.9 3656.86   134.1 3638.66
   207.9 3597.91   293.3 3560.88   324.3 3542.16   340.1  3537.7   369.6 3519.33
   484.4 3472.51   497.3 3464.02   518.8 3459.99   529.3 3451.31   534.2 3450.29
   629.2 3450.37   700.2 3462.38   752.6 3464.58   878.9 3464.59   989.9 3474.66
  1012.9 3473.31  1160.1 3481.48  1233.7 3491.54    1465 3514.43  1591.2 3535.27
  1683.3 3564.51  1696.3 3571.26  1723.5 3571.93  1769.9 3589.37  1846.6 3607.19
#Mann= 11 ,-1,0
       0      .1       0   534.2    .045       0   629.2    .025       0
     690      .1       0     710     .12       0     820      .1       0
     860     .12       0    1470      .1       0    1590     .12       0
    1620     .06       0    1720      .1       0
Bank Sta=534.2,629.2
XS Rating Curve= 0 ,0
Exp/Cntr(USF)=0,0
Exp/Cntr=0.3,0.1

Type RM Length L Ch R = 1 ,266526  ,655.5,705,735.2
XS GIS Cut Line= 4
2298650.00814051610702.045289584 2299071.9427156610327.876892812
 2299071.9427156609738.7606936382299497.85780554 609396.43641574
#Sta/Elev= 30
       0 3639.67    50.3 3626.78   127.9 3611.33   155.2 3602.25   291.6 3566.42
   393.2 3550.16   409.2 3544.52   424.3 3529.85   475.3 3507.82   586.6 3470.77
   610.6 3469.18   650.9 3458.78   694.6 3454.96   714.6 3448.16   838.9 3448.11
   854.6  3455.9   870.6 3455.99   898.4 3460.71   926.9 3456.54  1074.9  3464.1
  1219.4 3495.85  1353.5 3508.22  1442.9 3520.02    1584  3551.8  1596.1 3556.18
  1610.1 3565.58  1635.8  3566.4  1647.2 3574.53  1666.5 3583.41  1699.5 3591.63
#Mann= 8 ,-1,0
       0      .1       0     540     .06       0  643.94      .1       0
   714.6    .045       0   838.9    .025       0  843.94      .1       0
 1443.06     .12       0 1523.06     .06       0
#XS Ineff= 2 , 0
                          899.35         3484.48
Permanent Ineff=
       F       F
Bank Sta=714.6,838.9
XS Rating Curve= 0 ,0
Exp/Cntr(USF)=0,0
Exp/Cntr=0.3,0.1

Type RM Length L Ch R = 1 ,265821  ,729.3,756,767.8
XS GIS Cut Line= 2
 2298964.4688144610845.3438245192300238.23356937609810.409961105
#Sta/Elev= 30
       0    3604     9.9 3602.25      32 3592.75    61.5 3589.36   128.5 3572.78
   207.5 3561.88   275.7 3549.15   339.8 3543.86   391.3 3523.95   411.9 3512.05
   458.3 3492.43   477.6  3490.2   514.6 3477.02   545.9 3471.66   618.1  3460.8
   748.8 3458.71   793.2 3452.22   911.9 3454.63   958.1 3446.56  1040.6 3446.53
  1043.5 3446.57  1068.9 3451.31  1087.1 3459.59    1118 3463.01  1211.8 3495.56
  1365.4 3530.99  1521.2 3573.44    1587 3595.53  1617.9 3598.32  1641.2 3608.04
#Mann= 10 ,-1,0
       0      .1       0     330     .12       0     480     .06       0
     510      .1       0     950    .025       0   958.1    .045       0
  1043.5      .1       0    1400     .12       0    1420      .1       0
    1570     .06       0
Bank Sta=958.1,1043.5
XS Rating Curve= 0 ,0
Exp/Cntr(USF)=0,0
Exp/Cntr=0.3,0.1

Type RM Length L Ch R = 1 ,265065  ,431.9,429.8,430.1
XS GIS Cut Line= 2
2299008.25447785611072.2331714982300397.45416374610833.402279941
#Sta/Elev= 30
       0  3632.2      73 3604.79   170.4 3561.11   186.6 3552.08   247.5 3526.21
   304.3 3509.76   365.2  3495.1   377.4 3488.68   397.7 3487.72   450.4 3470.29
   478.8 3464.55   551.9 3460.67   616.8 3453.86   722.4    3456   738.6 3453.08
   742.7  3451.3   746.7 3446.23   750.8 3444.88   884.7 3444.91   909.1 3450.52
   917.2 3454.91   941.5 3458.28  1006.5 3459.39    1043 3482.04  1071.4 3487.82
  1168.8 3513.82  1262.2 3545.19  1314.9 3568.05  1347.4 3576.69  1409.6  3587.6
#Mann= 8 ,-1,0
       0      .1       0     360     .06       0     460      .1       0
   750.8    .045       0   884.7    .025       0     960      .1       0
    1060     .12       0    1160      .1       0
Bank Sta=750.8,884.7
XS Rating Curve= 0 ,0
Exp/Cntr(USF)=0,0
Exp/Cntr=0.3,0.1

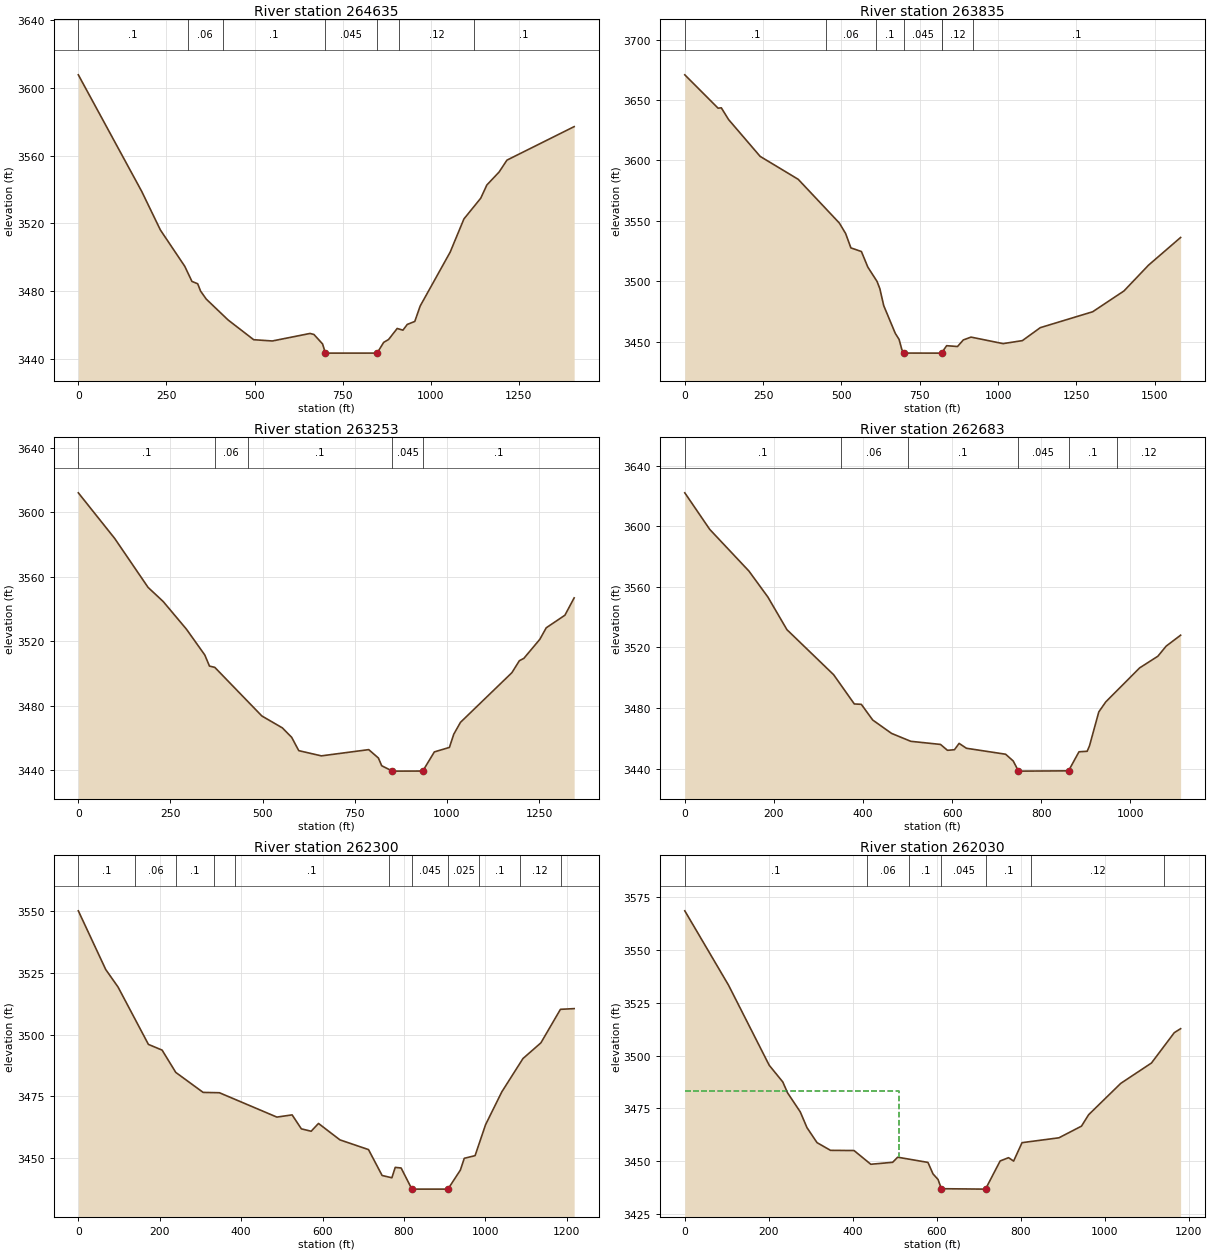
Type RM Length L Ch R = 1 ,264635  ,801,800.7,800.5
XS GIS Cut Line= 3
2299155.53352764611498.1482614412300130.75966817611311.064063055
2300512.88909466611151.843468683
#Sta/Elev= 30
       0 3607.67   179.9 3538.86   232.8 3516.12   302.1 3494.64   322.4 3485.73
   338.7 3484.35   346.9 3480.04   363.1 3475.28   425.1 3462.96   497.6 3451.33
   550.5 3450.58   657.5 3455.03   668.6 3454.41   693.1 3448.83   701.2 3443.41
   847.8 3443.43   866.4 3449.74   880.4 3451.46   904.8 3457.96   921.1 3456.97
   933.4 3460.35   954.8 3462.12     970  3471.2  1055.2 3503.04  1094.2 3522.61
  1141.9 3534.85  1159.2 3542.63  1193.9 3550.28  1216.3 3557.32    1407 3577.09
#Mann= 7 ,-1,0
       0      .1       0     310     .06       0     410      .1       0
   701.2    .045       0   847.8    .025       0     910     .12       0
 1123.01      .1       0
Bank Sta=701.2,847.8
XS Rating Curve= 0 ,0
Exp/Cntr(USF)=0,0
Exp/Cntr=0.3,0.1

Type RM Length L Ch R = 1 ,263835  ,543.2,581.8,617.5
XS GIS Cut Line= 4
2299270.96845856611983.7710742732299872.02620231612174.835787519
2300556.67475811612023.5762228662300799.01024785612087.600980783
#Sta/Elev= 30
       0 3670.91   106.2  3643.3   116.6 3643.57   139.8 3633.86   240.5 3603.37
     362 3584.38   493.2  3548.2   513.3  3539.5   530.1  3527.6   563.7 3524.58
   584.2 3511.68   613.6 3499.81   622.5 3493.85   634.9 3479.79   671.8 3456.83
   684.1 3451.73   692.6 3443.48   699.3 3440.49   819.3 3440.44   835.7 3446.59
   870.4 3445.92   888.9 3451.35   913.5 3453.71  1015.9 3448.31  1077.4  3450.8
  1134.7 3461.54  1301.8  3474.7  1401.5 3491.89    1480 3513.28  1582.5 3536.23
#Mann= 7 ,-1,0
       0      .1       0     450     .06       0     610      .1       0
   699.3    .045       0   819.3      .1       0  820.69     .12       0
  920.69      .1       0
Bank Sta=699.3,819.3
XS Rating Curve= 0 ,0
Exp/Cntr(USF)=0,0
Exp/Cntr=0.3,0.1

Type RM Length L Ch R = 1 ,263253  ,562.8,569.4,584.8
XS GIS Cut Line= 2
2299163.49455736612230.5629955492300321.82438141612915.211551346
#Sta/Elev= 30
       0  3612.1    98.8 3583.79   189.3 3553.47   230.2 3544.76   293.5 3527.55
   343.2 3511.59   355.8 3504.73   370.4 3503.91     498  3473.8   553.7 3466.41
     579 3460.54   598.2  3452.3   659.5 3449.07     788 3452.94   814.3 3447.74
   823.2 3442.96   852.2 3439.65   854.1 3439.61   934.7 3439.66   966.1 3451.52
    1007 3454.31  1018.7 3462.43    1037 3469.85  1176.5 3500.62  1196.8 3508.04
  1208.9 3509.48  1252.3 3521.29  1269.8 3528.46  1320.4 3536.24  1345.5 3546.99
#Mann= 5 ,-1,0
       0      .1       0     370     .06       0     460      .1       0
   852.2    .045       0   934.7      .1       0
Bank Sta=852.2,934.7
XS Rating Curve= 0 ,0
Exp/Cntr(USF)=0,0
Exp/Cntr=0.3,0.1

Type RM Length L Ch R = 1 ,262683  ,404.3,383.7,369
XS GIS Cut Line= 2
2298940.58572524612365.9005007652299657.07839991613217.730680651
#Sta/Elev= 30
       0 3622.02      56 3597.88     144 3570.37   186.6 3553.19   229.3 3531.68
   334.2 3501.92   380.6 3482.63   396.3 3482.39   421.9 3472.02   464.2 3463.19
   507.4 3457.97     574 3455.92   589.7 3452.03   605.4 3452.43   615.8  3456.6
   632.3 3453.38   720.2 3449.45   737.3 3444.98   748.7 3438.55   751.5 3438.29
   861.5 3438.48   884.9 3451.06   903.3  3451.4   908.5 3454.97   929.4 3477.38
   945.1 3484.01  1021.2 3506.47    1062 3514.14  1080.6 3520.81  1113.1 3528.03
#Mann= 6 ,-1,0
       0      .1       0     350     .06       0     500      .1       0
   748.7    .045       0   861.5      .1       0     970     .12       0
Bank Sta=748.7,861.5
XS Rating Curve= 0 ,0
Exp/Cntr(USF)=0,0
Exp/Cntr=0.3,0.1

Type RM Length L Ch R = 1 ,262300  ,291.9,269.7,253.2
XS GIS Cut Line= 4
2298557.78325842612681.0750496562298650.00814051612970.938759376
2299274.94897342613265.4968589632299497.85780554613257.535829244
#Sta/Elev= 30
       0 3550.22    67.3 3526.44    97.5 3519.36   172.2 3496.09   205.8 3493.78
   239.4 3484.74   306.6 3476.64   346.6  3476.5   487.8 3466.63   525.2 3467.53
   547.9 3461.87     572  3460.9     590 3464.06   642.7  3457.4   712.9 3453.46
   746.3 3442.97   770.3 3442.04   778.5 3446.25     793 3446.01   819.5 3437.44
     908 3437.44   938.6 3445.17   948.1 3449.93   974.7 3451.01  1000.4 3463.53
  1040.3 3476.84  1092.3 3490.35  1136.4 3496.72  1184.4  3510.3  1218.1 3510.59
#Mann= 11 ,-1,0
       0      .1       0     140     .06       0     240      .1       0
  334.18     .06       0  384.18      .1       0  764.18     .06       0
   819.5    .045       0     908    .025       0  984.18      .1       0
 1085.06     .12       0 1185.06      .1       0
Bank Sta=819.5,908
XS Rating Curve= 0 ,0
Exp/Cntr(USF)=0,0
Exp/Cntr=0.3,0.1

Type RM Length L Ch R = 1 ,262030  ,1008.5,913.1,818.2
XS GIS Cut Line= 4
2298469.87541134613582.7482560272298681.85225939613460.542087067
2299338.63721117613480.444661364 2299521.7408947613269.477373822
#Sta/Elev= 30
       0 3568.59   104.2 3533.35   201.2 3495.36   233.5 3487.47   244.7 3482.35
     275 3473.32     291 3465.85     315 3458.72   347.1 3455.07   403.1 3454.98
   443.1 3448.47   495.1  3449.4   507.1 3451.82   579.2 3449.35   591.2 3443.92
   603.2 3441.28   611.2 3436.89   715.2 3436.69   716.9 3436.92   751.2 3450.04
   771.2  3451.6   783.3 3449.98   803.3 3458.71   891.3 3461.02   944.9 3466.54
   961.9 3471.94  1038.5 3486.81  1111.6 3496.46    1166 3510.84  1181.1 3512.73
#Mann= 7 ,-1,0
       0      .1       0  434.68     .06       0  534.68      .1       0
   611.2    .045       0   716.9      .1       0  824.68     .12       0
 1141.77      .1       0
#XS Ineff= 2 , 0
           510.3 3482.98
Permanent Ineff=
       F       F
Bank Sta=611.2,716.9
XS Rating Curve= 0 ,0
Exp/Cntr(USF)=0,0
Exp/Cntr=0.3,0.1

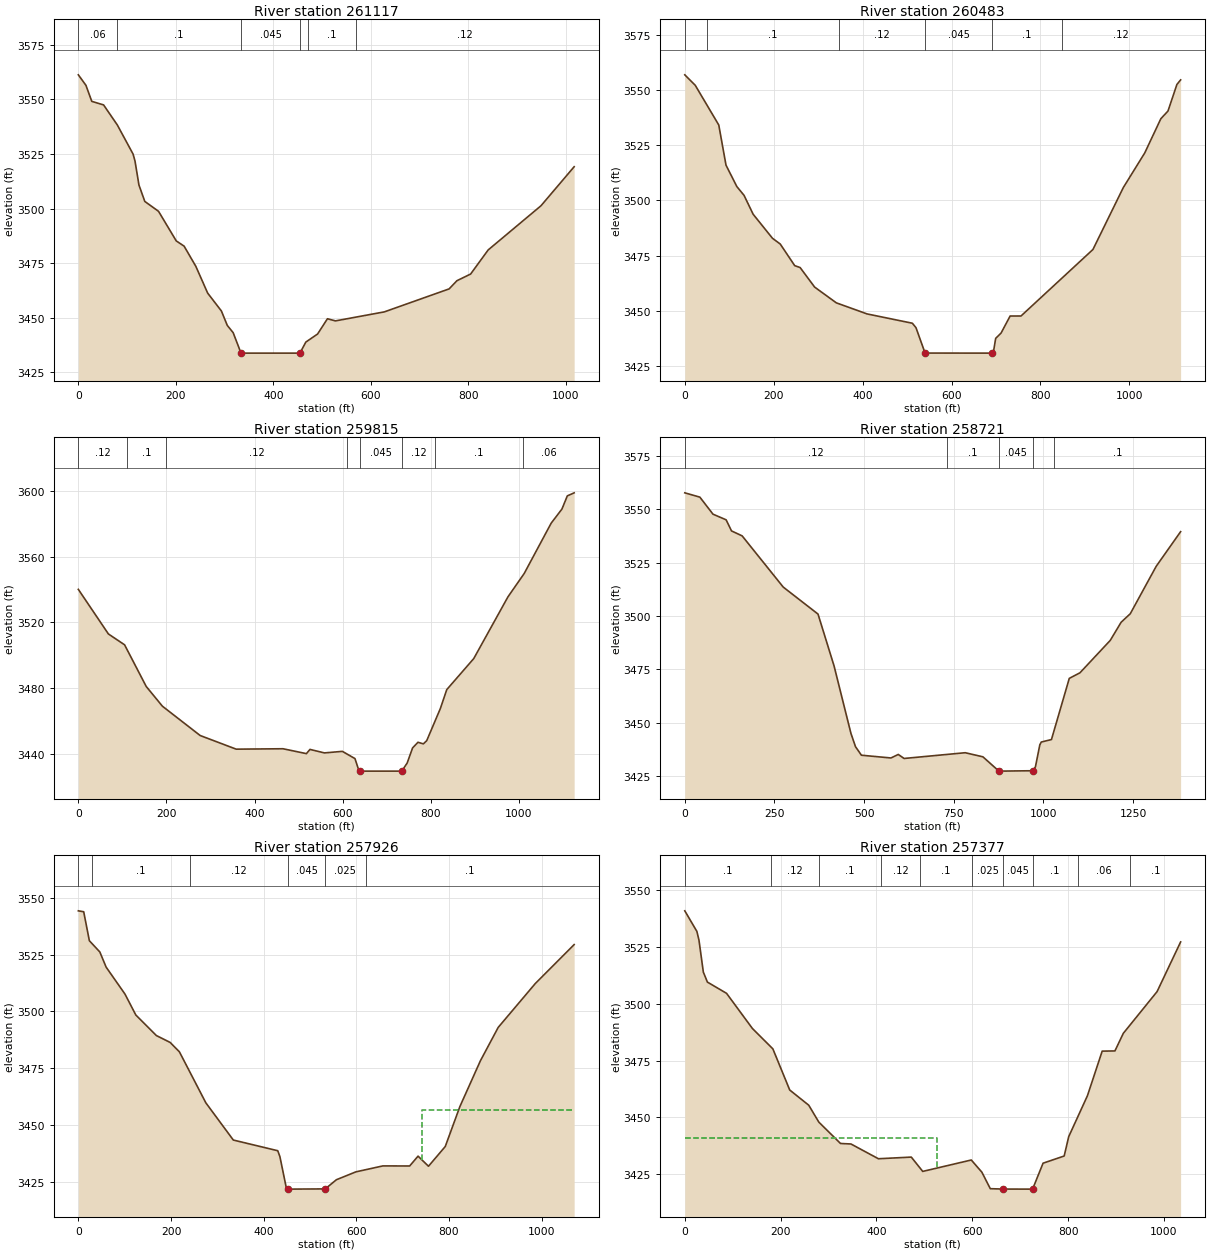
Type RM Length L Ch R = 1 ,261117  ,637.6,633.6,630
XS GIS Cut Line= 3
2299796.39641999614256.6450589242299712.80560794613524.230324816
2299731.38077643613245.345183257
#Sta/Elev= 30
       0 3561.27    15.6 3556.46    27.6 3549.11    51.8 3547.48      80 3538.28
   112.2 3524.98   116.2 3521.78   124.3 3510.78   136.3 3503.26   164.5 3498.72
   200.8 3485.17   216.9 3482.77     241  3473.5   265.2 3461.26   293.4 3453.05
   305.4 3446.47   317.5 3443.12   333.6 3433.75   454.4 3433.75   466.5 3438.81
   490.6 3442.51   510.8  3449.5   527.3 3448.52   627.5 3452.65   760.3 3463.18
   776.3 3466.93   804.4 3469.99   840.4 3481.03   948.7 3501.28  1016.7 3519.16
#Mann= 6 ,-1,0
       0     .06       0      80      .1       0   333.6    .045       0
   454.4    .025       0     470      .1       0     570     .12       0
Bank Sta=333.6,454.4
XS Rating Curve= 0 ,0
Exp/Cntr(USF)=0,0
Exp/Cntr=0.3,0.1

Type RM Length L Ch R = 1 ,260483  ,649.6,668.6,697.3
XS GIS Cut Line= 4
2300369.59055972614324.3138115322300425.31776775614021.794682226
2300325.80489627 613500.347235662300352.09199307613224.862507381
#Sta/Elev= 30
       0 3556.82    23.5 3552.08    76.4 3534.11    92.7 3515.92   117.1 3506.21
   133.3 3502.24   153.7  3493.7   197.2  3482.8   214.7  3480.2   247.2 3470.42
   259.4 3469.55     292 3460.71   340.8 3453.57     410 3448.55   511.8 3444.34
     520 3442.32   540.4 3430.83     691  3430.8   695.1 3432.44   699.2 3437.47
   711.4  3439.9   731.7  3447.6   756.2 3447.61     918 3477.73   986.3 3505.77
  1034.5 3521.45  1070.7 3536.93  1086.8 3540.43  1106.8 3552.44  1115.2 3554.53
#Mann= 6 ,-1,0
       0     .06       0      50      .1       0  347.61     .12       0
   540.4    .045       0     691      .1       0  848.47     .12       0
Bank Sta=540.4,691
XS Rating Curve= 0 ,0
Exp/Cntr(USF)=0,0
Exp/Cntr=0.3,0.1

Type RM Length L Ch R = 1 ,259815  ,1038.7,1094.1,1148.1
XS GIS Cut Line= 2
2300895.01852115614384.0215344212301124.39547709613282.000722541
#Sta/Elev= 30
       0 3540.06    68.3 3512.89     105 3506.29   154.1 3480.92   190.8 3468.91
   276.6 3451.03   358.4 3442.72   464.6 3442.97   517.7    3440   525.9 3442.56
   558.6 3440.44   599.4 3441.38     628 3436.98   636.2 3430.28   640.3 3429.34
   734.2 3429.34   746.5 3434.26   758.8 3443.48     771 3446.91   783.3 3445.95
   790.9 3447.89   821.8 3467.43   836.4 3478.99   897.7 3497.91   975.3  3535.5
  1012.1 3549.69  1073.4 3580.37  1097.9    3589  1110.1 3597.01  1125.6 3598.87
#Mann= 8 ,-1,0
       0     .12       0     110      .1       0     200     .12       0
     610    .025       0   640.3    .045       0   734.2     .12       0
     810      .1       0    1010     .06       0
Bank Sta=640.3,734.2
XS Rating Curve= 0 ,0
Exp/Cntr(USF)=0,0
Exp/Cntr=0.3,0.1

Type RM Length L Ch R = 1 ,258721  ,765.1,794.2,830.1
XS GIS Cut Line= 3
2300914.92109545614475.5733761852301949.85495886614284.508662939
2302260.33511788614395.963078999
#Sta/Elev= 30
       0 3557.67      42 3555.65    78.6 3547.67   115.2 3545.03   130.2 3539.84
   159.9  3537.5   274.4 3513.53   371.4 3500.88   416.2 3476.56   463.2    3445
   475.9 3438.77   492.4 3434.77   574.8 3433.48   595.1 3435.13   611.4 3433.25
   781.8 3435.94   831.1 3434.02   875.8 3427.32   969.4  3427.5   977.5  3429.3
   989.7  3439.6   993.8 3440.94  1022.2 3442.11  1071.9 3470.76  1101.7 3473.38
  1186.1 3488.55  1216.4 3497.04  1241.9 3501.03  1314.3 3523.28  1382.3 3539.48
#Mann= 5 ,-1,0
       0     .12       0     730      .1       0   875.8    .045       0
   969.4    .025       0    1030      .1       0
Bank Sta=875.8,969.4
XS Rating Curve= 0 ,0
Exp/Cntr(USF)=0,0
Exp/Cntr=0.3,0.1

Type RM Length L Ch R = 1 ,257926  ,534.1,549.7,573
XS GIS Cut Line= 2
2300879.09646171 614666.638089432301826.45899822615164.202446841
#Sta/Elev= 30
       0  3544.3    11.6 3543.89    23.8 3531.13    46.4 3526.17      60 3519.49
   100.6 3507.64   124.1 3498.39   168.4 3489.34   198.2  3486.3   218.1 3482.18
   275.2 3459.69   334.5 3443.29   430.4 3438.58     435 3436.02   448.5 3422.59
   452.8  3421.7     453 3421.66   532.9 3421.76   556.9 3425.79     599 3429.27
   657.3 3431.89   715.1 3431.86   733.2  3436.2   755.7 3431.75   791.9 3440.43
   823.5 3458.05   867.7 3478.19   906.2 3492.93   986.2 3512.25  1070.1 3529.42
#Mann= 6 ,-1,0
       0     .12       0      30      .1       0     240     .12       0
   452.8    .045       0   532.9    .025       0     620      .1       0
#XS Ineff= 2 , 0
                          741.53         3456.49
Permanent Ineff=
       F       F
Bank Sta=452.8,532.9
XS Rating Curve= 0 ,0
Exp/Cntr(USF)=0,0
Exp/Cntr=0.3,0.1

Type RM Length L Ch R = 1 ,257377  ,635.9,632.5,647
XS GIS Cut Line= 2
2300763.66153079614726.3458123192301197.53765046 615665.74731911
#Sta/Elev= 30
       0 3541.03    25.2 3531.97    29.6 3528.09    38.7 3514.02    47.2 3509.61
    87.1 3504.67   141.2 3489.14   183.8 3480.18     219 3462.04   258.7 3455.34
   279.8 3447.87     325 3438.47   346.8 3438.25   404.1 3431.74   472.7 3432.47
   496.6 3426.16   597.9 3431.19     620 3425.82   637.6 3418.54   664.93418.378
   725.9 3418.35   747.7 3429.78   791.8 3432.95   801.2 3441.46   840.3 3459.51
   871.1 3479.18   897.7 3479.27   915.2 3487.03   985.7 3505.43  1034.8 3527.31
#Mann= 10 ,-1,0
       0      .1       0     180     .12       0     280      .1       0
     410     .12       0     490      .1       0     600    .025       0
   664.9    .045       0   725.9      .1       0     820     .06       0
     930      .1       0
#XS Ineff= 2 , 0
          526.79 3440.83
Permanent Ineff=
       F       F
Bank Sta=664.9,725.9
XS Rating Curve= 0 ,0
Exp/Cntr(USF)=0,0
Exp/Cntr=0.3,0.1

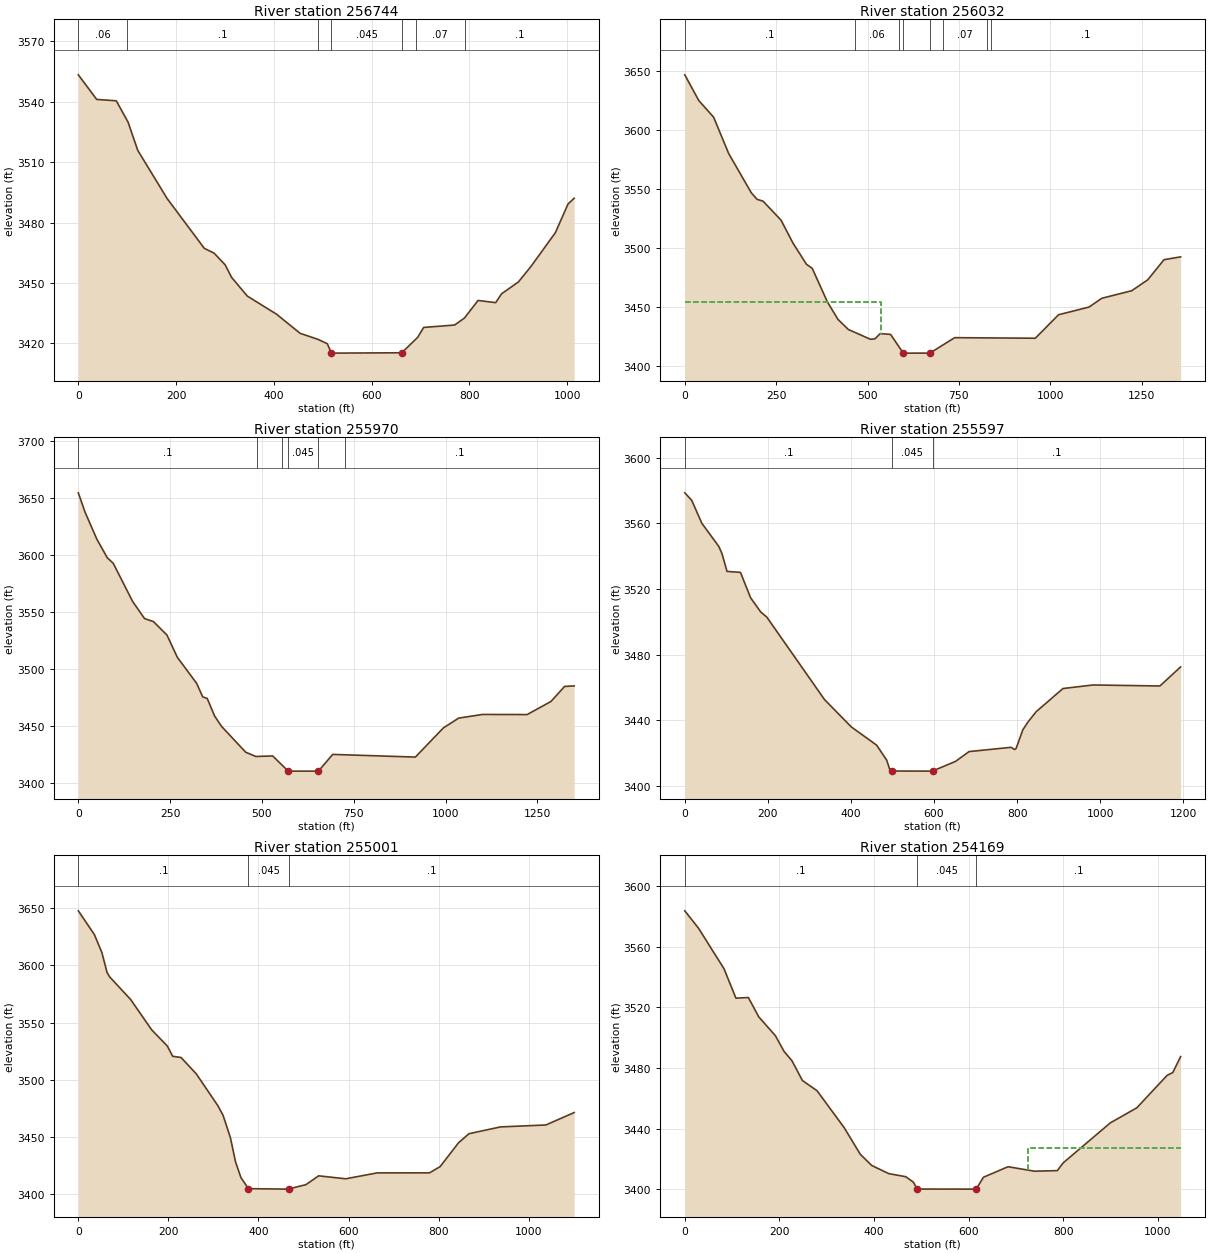
Type RM Length L Ch R = 1 ,256744  ,746.9,712.3,671.8
BEGIN DESCRIPTION:
Structure XS 4
END DESCRIPTION:
XS GIS Cut Line= 2
2300454.95509804614683.545366082 2300450.0300599615697.591437984
#Sta/Elev= 30
       0 3553.41    37.6 3541.19    77.6 3540.51   101.6 3529.99   121.6 3515.87
   181.6 3491.97   257.6 3467.22   277.6 3464.85   300.3 3459.01   313.6 3452.75
   345.6  3443.5   405.6 3434.47   453.6    3425     490 3422.02   509.3 3419.83
   517.4 3415.26   517.6 3415.16   661.6 3415.34   694.2 3423.05   706.3 3427.92
   769.6 3429.12   789.6 3432.56   817.6 3441.33   853.6 3440.24   865.6 3444.63
   900.1 3450.52   925.6 3458.17   975.7    3475  1001.6 3489.27  1014.1 3492.09
#Mann= 7 ,-1,0
       0     .06       0     100      .1       0     490    .025       0
   517.4    .045       0   661.6      .1       0     690     .07       0
     790      .1       0
Bank Sta=517.4,661.6
XS Rating Curve= 0 ,0
Exp/Cntr(USF)=0,0
Exp/Cntr=0.3,0.1

Type RM Length L Ch R = 1 ,256032  ,62.2,62,62.1
BEGIN DESCRIPTION:
Structure XS 3
END DESCRIPTION:
XS GIS Cut Line= 3
2299202.96870579615149.7732932962299649.11737019615247.793258885
2300385.51261916615765.260190592
#Sta/Elev= 30
       0 3646.63    38.1 3624.92      79 3610.66     120 3579.97   181.8 3546.68
   197.8 3541.03   214.2  3539.5   263.3 3523.41   296.1 3503.91     333 3485.96
   348.8 3482.49   390.3    3454     419  3439.3   447.6 3430.66   507.9 3422.39
   520.3 3422.69   534.6 3427.16   563.2 3426.49   597.4  3410.8   602.3 3410.62
   670.7 3410.64   738.5 3423.73   959.2 3423.25  1022.7 3443.16  1106.2 3449.69
    1141 3457.11  1223.2 3463.57  1266.8 3472.76  1311.2 3489.83  1356.8 3492.26
#Mann= 8 ,-1,0
       0      .1       0  466.79     .06       0  586.79     .07       0
   597.4    .045       0   670.7     .08       0  706.79     .07       0
  826.79     .08       0  836.79      .1       0
#XS Ineff= 2 , 0
          537.76 3453.88
Permanent Ineff=
       F       F
Bank Sta=597.4,670.7
XS Rating Curve= 0 ,0
Exp/Cntr(USF)=0,0
Exp/Cntr=0.3,0.1

Type RM Length L Ch R = 1 ,255970  ,386.7,372.6,348.9
BEGIN DESCRIPTION:
Structure XS 2
END DESCRIPTION:
XS GIS Cut Line= 3
2299182.48602991615240.4959320712299641.15634048615319.442526352
2300369.59055972615820.987398622
#Sta/Elev= 30
       0  3654.9    17.9 3638.26    50.4 3614.24    78.8 3597.91    95.1 3593.02
   147.8 3559.54   180.3 3544.53   204.7 3541.81   241.2 3530.08   269.6  3510.5
   322.4 3487.49   338.6 3475.79   350.8 3474.43   371.1 3458.92   389.9 3449.87
   455.7 3427.18   483.2 3423.46   529.2 3423.91   571.1  3410.7   575.9 3410.59
   653.6 3410.59   692.5 3425.27   917.5 3422.92   993.6 3448.47  1035.4 3457.13
  1100.4 3460.36  1221.8 3460.24  1286.7 3471.75  1323.8 3484.95  1349.8 3485.42
#Mann= 6 ,-1,0
       0      .1       0  485.41     .06       0  555.41      .1       0
   571.1    .045       0   653.6     .08       0  725.41      .1       0
Bank Sta=571.1,653.6
XS Rating Curve= 0 ,0
Exp/Cntr(USF)=0,0
Exp/Cntr=0.3,0.1

Type RM Length L Ch R = 1 ,255597  ,642.2,595.9,557.3
BEGIN DESCRIPTION:
Structure XS 1
END DESCRIPTION:
XS GIS Cut Line= 3
2299143.67558439615672.4645443452299955.61701436615797.104309467
2300325.80489627615836.909458059
#Sta/Elev= 30
       0  3578.5    16.7 3573.95      41 3559.98    81.8 3545.91    89.5 3541.53
   101.7 3530.66   134.1 3530.09   158.3  3514.7   182.6 3506.04   197.5 3502.85
   336.4 3452.68   401.1 3435.99   461.8 3424.95   486.1 3415.84   494.2 3409.56
   498.3 3409.19   595.4 3409.12   597.3 3409.27     652 3415.06   684.4 3421.01
   785.6 3423.61   793.9 3422.28   797.7 3422.92   813.9 3434.28     826 3438.95
   846.2 3445.34   910.5 3459.39   982.9 3461.56  1143.9 3460.94  1193.8 3472.55
#Mann= 3 ,-1,0
       0      .1       0   498.3    .045       0   597.3      .1       0
Bank Sta=498.3,597.3
XS Rating Curve= 0 ,0
Exp/Cntr(USF)=0,0
Exp/Cntr=0.3,0.1

Type RM Length L Ch R = 1 ,255001  ,872.5,832.4,803.1
XS GIS Cut Line= 2
2299525.72140956616617.0903704792300325.80489627615860.792547215
#Sta/Elev= 30
       0 3647.75    35.6 3627.04    52.3  3611.3    63.9 3593.78    69.7 3589.99
   116.3 3570.21   162.9 3543.77   197.8 3529.53   209.5 3520.66     228  3519.6
     262 3505.27   310.1 3477.34   321.4 3469.08   337.6 3449.68   349.2 3428.26
     361 3414.75   377.7 3404.98   465.7 3404.59   468.5 3404.89   505.3 3408.48
   533.6 3416.21   593.8 3413.62   663.7 3418.78   779.8 3418.81   803.4 3424.26
   844.2 3445.06   867.5 3453.01   937.4 3458.95  1038.2 3460.64    1101 3471.49
#Mann= 3 ,-1,0
       0      .1       0   377.7    .045       0   468.5      .1       0
Bank Sta=377.7,468.5
XS Rating Curve= 0 ,0
Exp/Cntr(USF)=0,0
Exp/Cntr=0.3,0.1

Type RM Length L Ch R = 1 ,254169  ,633.6,667.5,698.4
XS GIS Cut Line= 3
2300496.96703522616911.6484700662300648.22659987616577.285221886
2300672.10968903615896.617180949
#Sta/Elev= 30
       0 3583.61    29.1 3572.11    82.9 3545.43   108.1 3526.02   134.4 3526.44
   156.4 3513.67   191.5 3501.28   209.8 3490.92   226.6 3484.71   248.6 3471.72
   279.4 3465.03   336.8 3440.67   371.1 3423.02   395.1  3415.7   431.1 3410.32
   467.2 3408.27   483.2 3404.68   491.2 3400.15   615.2 3400.09     616 3400.13
   631.3 3407.93   683.3 3414.87   739.3 3411.91   787.4 3412.29   800.1 3417.48
   899.4 3443.75   955.5 3453.72  1019.5 3475.09  1031.5 3476.95  1048.1 3487.46
#Mann= 3 ,-1,0
       0      .1       0   491.2    .045       0     616      .1       0
#XS Ineff= 2 , 0
                           725.2          3426.9
Permanent Ineff=
       F       F
Bank Sta=491.2,616
XS Rating Curve= 0 ,0
Exp/Cntr(USF)=0,0
Exp/Cntr=0.3,0.1

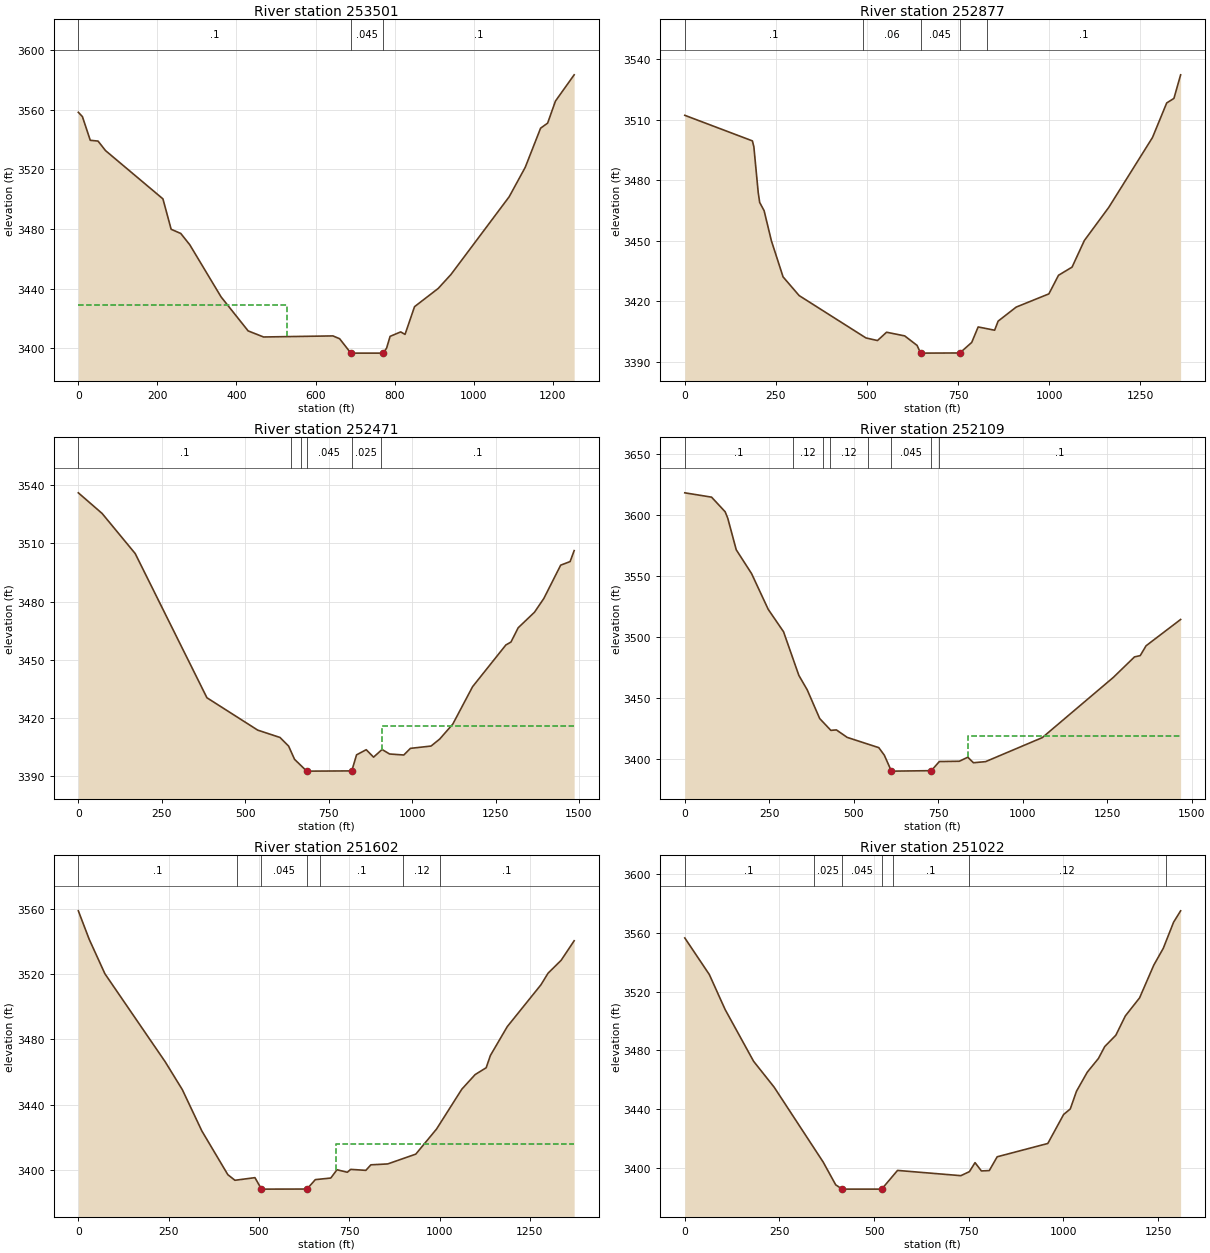
Type RM Length L Ch R = 1 ,253501  ,615.2,624.1,629.4
XS GIS Cut Line= 2
2300795.50564967617043.0054604222301661.68138178616135.780775239
#Sta/Elev= 30
       0 3558.37    10.3 3555.49    30.2 3539.58    49.9 3539.04    68.9 3532.63
     214 3500.25   234.8 3479.84   259.2 3477.02   281.9 3469.45   361.1 3434.44
   429.6 3411.61   468.6 3407.53     644 3408.25     661 3406.36   689.3 3396.74
   692.1 3396.69   771.3 3396.69   779.8 3400.04   788.7 3407.96   815.5 3410.93
   826.5 3409.27   850.5 3427.88   910.4 3440.12   942.7  3449.5  1089.9 3501.66
  1130.6 3521.46  1169.4 3547.71  1187.2  3551.1    1207 3565.91  1254.3 3583.53
#Mann= 3 ,-1,0
       0      .1       0   689.3    .045       0   771.3      .1       0
#XS Ineff= 2 , 0
          526.64 3429.31
Permanent Ineff=
       F       F
Bank Sta=689.3,771.3
XS Rating Curve= 0 ,0
Exp/Cntr(USF)=0,0
Exp/Cntr=0.3,0.1

Type RM Length L Ch R = 1 ,252877  ,416.3,406.5,395.9
XS GIS Cut Line= 4
2300979.02563726617198.7437427532301316.95309623 617222.12862909
2301826.45899822616875.8238363322302132.95864239 616609.12934076
#Sta/Elev= 30
       0 3512.21   185.6 3499.53   189.6 3496.59   201.6 3473.85   205.6    3469
   217.7 3464.94   237.7 3450.01   269.8  3432.1   313.9 3422.84   497.2 3401.85
   528.9 3400.55   553.9 3404.67   603.7 3402.85   637.7 3398.13   647.3 3394.31
     755 3394.39   787.6  3399.6   805.3 3407.29   850.5 3405.67   860.1 3410.17
   909.7 3417.13   999.5 3423.69  1025.9 3432.91  1063.1 3436.95  1096.8 3450.13
  1163.9 3466.58  1283.9 3501.22  1322.9 3518.34  1342.7 3520.58  1361.1 3532.28
#Mann= 5 ,-1,0
       0      .1       0  488.74     .06       0   647.3    .045       0
     755     .12       0  828.74      .1       0
Bank Sta=647.3,755
XS Rating Curve= 0 ,0
Exp/Cntr(USF)=0,0
Exp/Cntr=0.3,0.1

Type RM Length L Ch R = 1 ,252471  ,369.7,362.3,354.7
XS GIS Cut Line= 3
2301488.11523518618018.2316009462301607.53068096 617556.49187727
2302351.88695965616875.823836332
#Sta/Elev= 30
       0 3536.11    71.3 3525.46   170.5 3504.74   385.3 3430.34   537.4 3413.64
   604.3 3409.84     630 3405.41   647.8 3398.57   683.8 3392.56   695.2 3392.47
   819.3 3392.59   833.6 3400.87   862.6 3403.52   884.6 3399.69   910.1 3403.63
   932.7 3401.31   975.2 3400.79     995 3404.22  1056.8 3405.41  1082.8 3409.03
    1122 3416.75  1181.3 3436.06    1281 3457.59  1296.3  3459.1  1317.9 3466.46
  1366.7 3474.48  1394.7 3481.57  1445.2 3498.77  1473.5 3500.63  1485.6 3506.28
#Mann= 6 ,-1,0
       0      .1       0  636.93    .025       0  666.93      .1       0
   683.8    .045       0   819.3    .025       0  906.93      .1       0
#XS Ineff= 2 , 0
                          910.32         3415.86
Permanent Ineff=
       F       F
Bank Sta=683.8,819.3
XS Rating Curve= 0 ,0
Exp/Cntr(USF)=0,0
Exp/Cntr=0.3,0.1

Type RM Length L Ch R = 1 ,252109  ,516.6,506.5,496.2
XS GIS Cut Line= 3
2301822.47848336618237.1599182072301933.93289942617779.400709389
2302582.75682149617023.102886126
#Sta/Elev= 30
       0 3618.03    79.3 3614.49   119.4 3602.55   127.2 3597.23   152.3 3571.43
   197.6 3551.98     247 3522.68   292.3 3504.38   337.6 3468.69   362.3 3456.91
   399.3 3433.38   432.3 3423.72   448.7 3424.09   480.7 3417.97   574.2 3409.58
   590.6 3403.41   611.1 3390.65   616.4 3390.37   729.6 3390.74   753.4 3398.21
   812.5 3398.45   837.7 3401.74   854.4 3397.23   890.4 3398.14  1058.2 3417.79
  1268.6 3467.08    1331  3483.8    1348 3484.86  1365.3 3492.91  1467.6 3514.43
#Mann= 8 ,-1,0
       0      .1       0     320     .12       0     410      .1       0
     430     .12       0  541.13      .1       0   611.1    .045       0
   729.6    .025       0  751.13      .1       0
#XS Ineff= 2 , 0
                          837.55         3419.31
Permanent Ineff=
       F       F
Bank Sta=611.1,729.6
XS Rating Curve= 0 ,0
Exp/Cntr(USF)=0,0
Exp/Cntr=0.3,0.1

Type RM Length L Ch R = 1 ,251602  ,591.9,579.7,566.1
XS GIS Cut Line= 2
2302192.66636528618396.3805125782302897.21749537 617218.14811423
#Sta/Elev= 30
       0 3558.74    30.2 3541.24    73.6 3520.17   240.7 3466.18     288 3449.15
     342 3423.87   413.9 3397.09   433.6 3393.64     489 3395.25   507.1 3388.22
   632.9 3388.27   656.2 3394.04     699 3395.02   716.1  3400.1   744.8 3398.55
   754.1 3400.33     796 3399.72     810 3403.11   856.6 3403.66   934.3 3409.66
   991.8 3425.04  1061.7 3449.43  1098.6  3458.4  1129.2 3462.59  1140.9 3470.11
  1187.5 3487.76  1280.7 3513.38  1300.6 3520.53  1336.7 3528.42  1372.8 3540.39
#Mann= 7 ,-1,0
       0      .1       0     440    .025       0   507.1    .045       0
   632.9    .025       0     670      .1       0     900     .12       0
    1000      .1       0
#XS Ineff= 2 , 0
                          714.66         3415.69
Permanent Ineff=
       F       F
Bank Sta=507.1,632.9
XS Rating Curve= 0 ,0
Exp/Cntr(USF)=0,0
Exp/Cntr=0.3,0.1

Type RM Length L Ch R = 1 ,251022  ,506.5,496.8,486.2
XS GIS Cut Line= 2
2302849.45131706618643.1724338542303227.60022869 617389.31025318
#Sta/Elev= 30
       0 3556.57    64.8 3531.66   106.5 3507.85   181.7  3472.6     236 3454.96
   365.6 3403.92   398.6 3388.45   415.7 3385.53   520.1 3385.54   561.9 3398.27
   729.2  3394.7   751.7 3397.43   766.6 3403.56   783.4 3397.92   804.2 3398.16
   825.1 3407.55   958.8 3416.62  1000.6 3436.36  1018.1 3440.11  1034.6  3452.2
    1063 3465.16  1092.5  3474.5  1109.2 3482.62  1138.5 3490.33  1163.6 3503.47
  1201.2 3515.77  1238.8 3538.11  1263.8 3549.52    1291 3567.28  1309.6 3575.04
#Mann= 7 ,-1,0
       0      .1       0     340    .025       0   415.7    .045       0
   520.1    .025       0     550      .1       0     750     .12       0
    1270      .1       0
Bank Sta=415.7,520.1
XS Rating Curve= 0 ,0
Exp/Cntr(USF)=0,0
Exp/Cntr=0.3,0.1