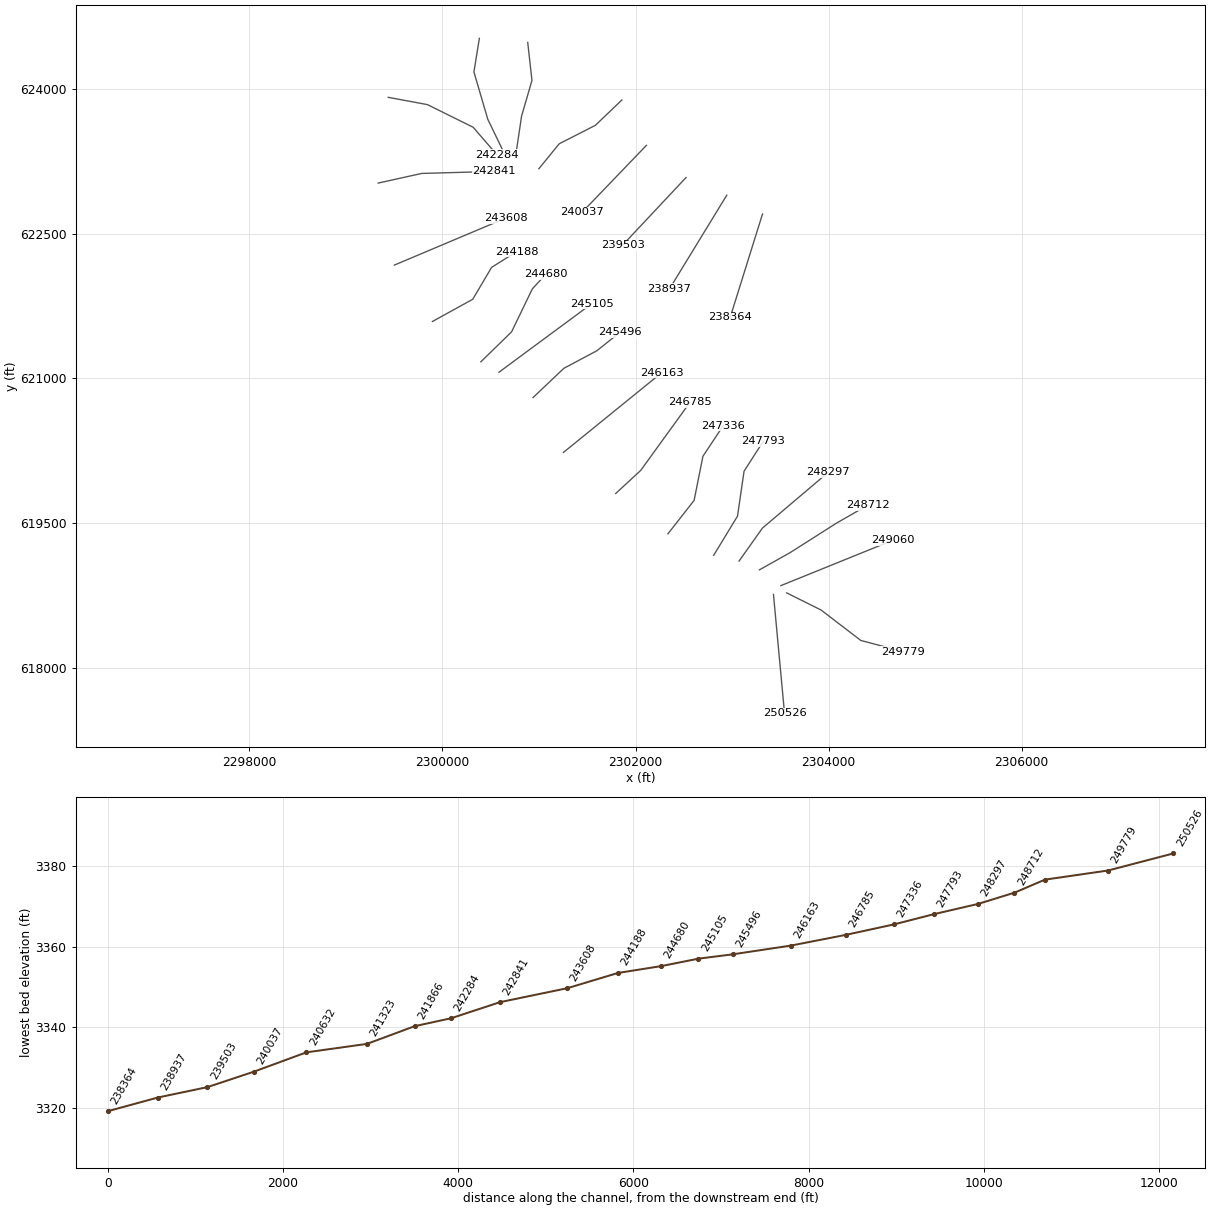
HEC-RAS study SHAVERSFK.prj: SHAVERSFK

--- SHAVERSFK.g01 (geometry) --- (continued)

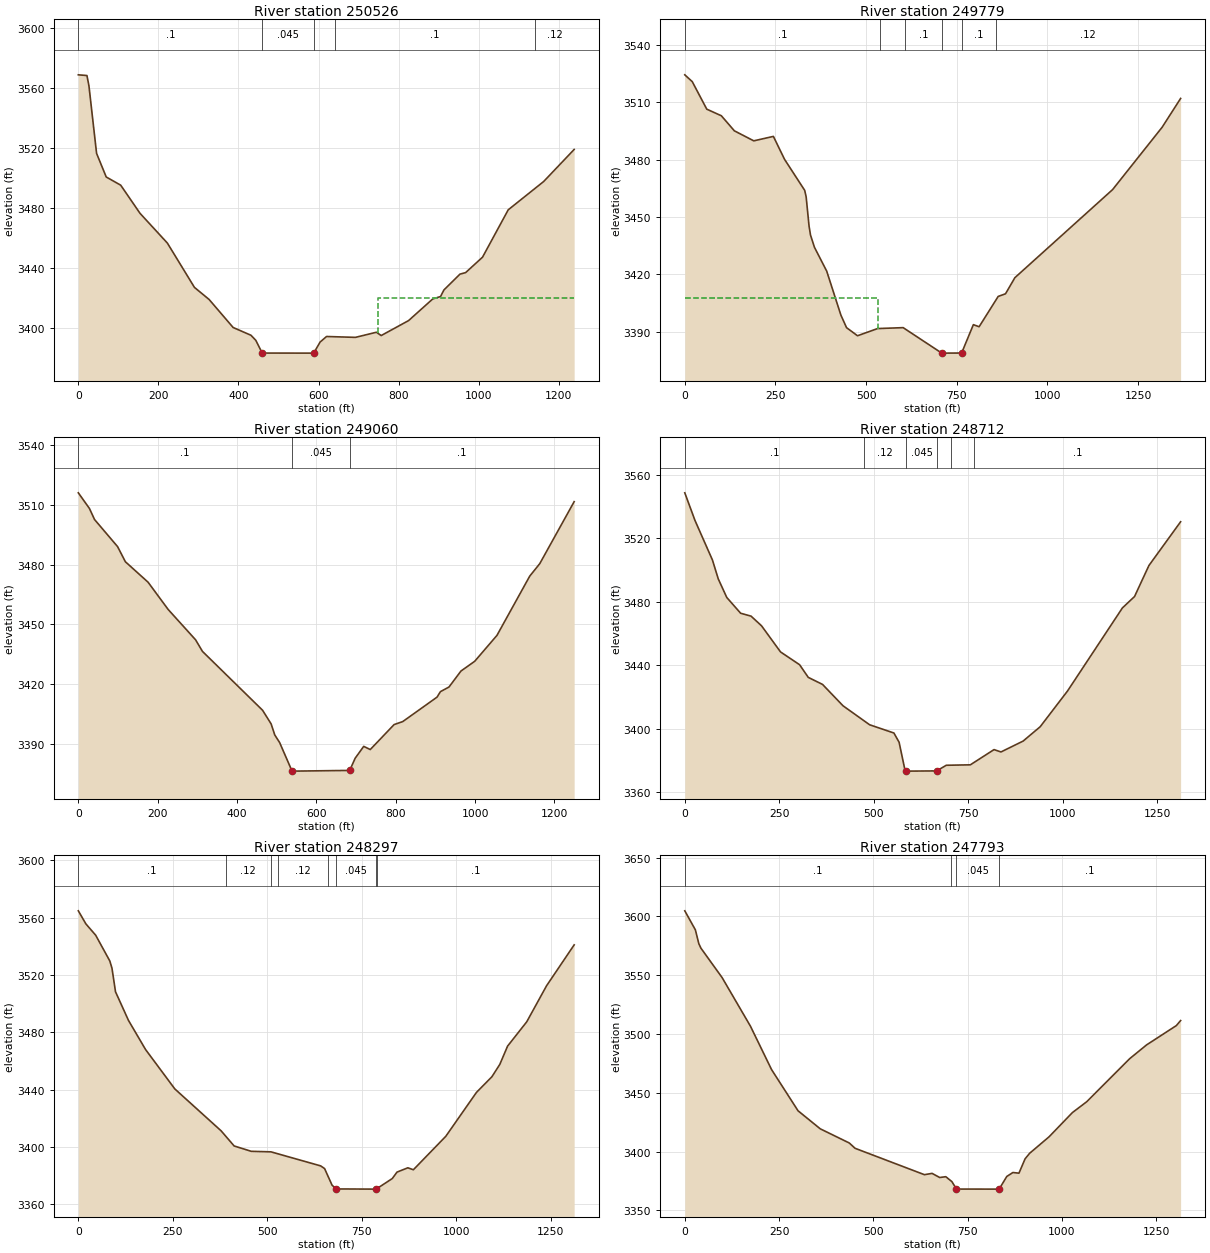
Type RM Length L Ch R = 1 ,250526  ,734.4,746.9,785.1
XS GIS Cut Line= 2
2303428.78258045618758.6073647732303543.38660582617525.227859975
#Sta/Elev= 30
       0 3568.81    21.5 3568.34    26.5 3561.47    45.6 3516.36    69.7 3500.61
   105.9 3495.13   154.1 3476.35   222.4  3456.5   290.1  3426.9   326.8 3418.81
   386.7 3400.13   431.3 3394.94   443.3 3391.58   459.4 3383.05     588 3383.01
     604  3390.4   620.1 3394.11   692.4 3393.53   744.6 3396.95   756.7 3394.75
     825 3404.72   885.2 3419.13     905 3420.82   913.3 3425.17   953.5 3435.76
   967.5 3436.75  1009.8 3447.07    1074 3478.69  1162.6  3497.6  1238.7 3518.99
#Mann= 5 ,-1,0
       0      .1       0   459.4    .045       0     588    .025       0
     640      .1       0    1140     .12       0
#XS Ineff= 2 , 0
                          749.03         3419.83
Permanent Ineff=
       F       F
Bank Sta=459.4,588
XS Rating Curve= 0 ,0
Exp/Cntr(USF)=0,0
Exp/Cntr=0.3,0.1

Type RM Length L Ch R = 1 ,249779  ,700.8,719.1,771
XS GIS Cut Line= 4
2303565.94399173 618774.529424212303921.86822018 618597.06466152
2304333.35415658618281.609284563 2304769.4687838618165.925252234
#Sta/Elev= 30
       0 3524.38    20.6 3520.81    60.6 3506.41   100.8 3502.97   136.6  3495.1
   190.2 3489.84   244.3 3492.17   275.1 3480.17   330.7 3463.92   334.7  3460.5
   342.7 3445.21   346.7 3440.55   357.6 3434.14   391.4 3421.66   430.4 3398.72
     446 3392.12   476.3 3387.87   531.7 3391.63   602.2 3392.11   708.1 3378.86
   713.1 3378.78   763.5 3378.84   795.8 3393.67   811.7 3392.59   864.3 3408.44
   884.5 3409.83   910.3 3418.24  1179.8 3464.33  1316.4 3496.95  1367.4 3512.03
#Mann= 6 ,-1,0
       0      .1       0  537.71    .025       0  607.71      .1       0
   708.1    .045       0   763.5      .1       0  857.71     .12       0
#XS Ineff= 2 , 0
          533.72 3407.79
Permanent Ineff=
       F       F
Bank Sta=708.1,763.5
XS Rating Curve= 0 ,0
Exp/Cntr(USF)=0,0
Exp/Cntr=0.3,0.1

Type RM Length L Ch R = 1 ,249060  ,337.6,347.7,377
XS GIS Cut Line= 2
2303506.23626884618850.1592065362304664.56609289619319.859959932
#Sta/Elev= 30
       0 3515.94      28  3508.1    40.9 3502.56      99 3488.98   118.6 3481.42
   175.8 3471.17   226.5  3457.5   295.6 3442.31   312.9 3436.51   464.5 3407.01
     486 3400.19   495.2 3394.65   507.5 3390.83   538.2 3376.78   541.2 3376.53
   684.1 3376.88   697.9    3383   719.4 3388.93   735.9 3387.34   796.1 3399.86
   817.9 3401.36   904.2 3413.59   912.8 3416.34   934.4 3418.67   964.6 3426.68
   999.2 3431.55  1055.3 3444.53  1137.9  3474.2  1163.2 3480.46  1249.9 3511.51
#Mann= 3 ,-1,0
       0      .1       0   538.2    .045       0   684.1      .1       0
Bank Sta=538.2,684.1
XS Rating Curve= 0 ,0
Exp/Cntr(USF)=0,0
Exp/Cntr=0.3,0.1

Type RM Length L Ch R = 1 ,248712  ,409.9,415.2,421.1
XS GIS Cut Line= 4
2303283.32743672619013.3603157672303601.76862546619192.483484435
2304083.41092344619498.983128599 2304409.8131419619686.067326986
#Sta/Elev= 30
       0 3548.63    26.9 3531.27    73.1 3506.36    88.6 3494.41   111.1 3482.72
   147.8 3472.77   175.4 3470.95   203.2 3464.85   253.4 3448.41   303.9 3440.34
   326.8 3432.38   364.7 3427.92   418.8 3414.48   489.3 3402.51   553.5 3397.33
   567.3 3391.49     582 3374.93   586.3 3373.31   666.9 3373.45   692.1    3377
   755.9 3377.28   818.6 3386.87     837 3385.39   895.6 3392.24   940.7 3401.26
  1013.1 3423.78  1158.4 3476.12  1190.5  3483.3  1228.6 3502.84  1312.5  3530.4
#Mann= 6 ,-1,0
       0      .1       0  475.36     .12       0   586.3    .045       0
   666.9      .1       0  705.36    .025       0  765.36      .1       0
Bank Sta=586.3,666.9
XS Rating Curve= 0 ,0
Exp/Cntr(USF)=0,0
Exp/Cntr=0.3,0.1

Type RM Length L Ch R = 1 ,248297  ,477.1,503.5,554.8
XS GIS Cut Line= 3
2303072.36014918 619104.912157532303315.17155559619447.236435429
2303995.83959653620024.411090025
#Sta/Elev= 30
       0 3564.78    19.9  3555.7      46 3547.73    83.3 3529.78      89  3524.8
    98.4 3508.27   132.7 3488.31   177.9 3467.98   255.3 3440.48   377.9 3411.21
   412.3 3400.66   457.7 3396.92   509.8 3396.55   641.3 3386.75   651.7 3384.86
   671.5 3373.26   682.9 3370.67   788.1 3370.53   830.9 3377.93   843.3 3382.41
     872 3385.42   886.6 3384.05   972.4 3407.39  1053.6 3438.05  1094.4 3448.96
  1115.4 3457.62  1135.9 3470.33  1186.7 3487.35  1239.1 3512.48  1312.1 3541.02
#Mann= 8 ,-1,0
       0      .1       0     390     .12       0  509.69      .1       0
  529.69     .12       0  659.69    .025       0   682.9    .045       0
   788.1    .025       0  789.69      .1       0
Bank Sta=682.9,788.1
XS Rating Curve= 0 ,0
Exp/Cntr(USF)=0,0
Exp/Cntr=0.3,0.1

Type RM Length L Ch R = 1 ,247793  ,460.1,457.7,455
XS GIS Cut Line= 4
2302809.64616846 619164.619880422303056.43808974619570.632396067
2303124.10684235620036.3526346032303323.13258531620346.832793627
#Sta/Elev= 30
       0 3604.69      28 3588.55    37.2 3576.73    42.8 3572.93      99 3547.86
   173.9 3506.67     230 3469.69   300.2 3434.64   359.1 3419.29     436 3407.25
   451.5 3402.72   635.3 3380.28   655.6 3381.39   675.8 3377.88   691.9 3378.57
   708.1 3374.38   720.2 3368.06   833.4    3368   853.6 3378.76   869.8 3382.12
   885.9 3381.57   902.1 3393.74   914.2 3398.48   965.7 3412.49  1027.5 3433.07
  1065.5 3442.32  1179.5 3478.96  1224.3 3490.67  1303.1 3507.08  1314.5 3511.36
#Mann= 4 ,-1,0
       0      .1       0  705.13    .025       0   720.2    .045       0
   833.4      .1       0
Bank Sta=720.2,833.4
XS Rating Curve= 0 ,0
Exp/Cntr(USF)=0,0
Exp/Cntr=0.3,0.1

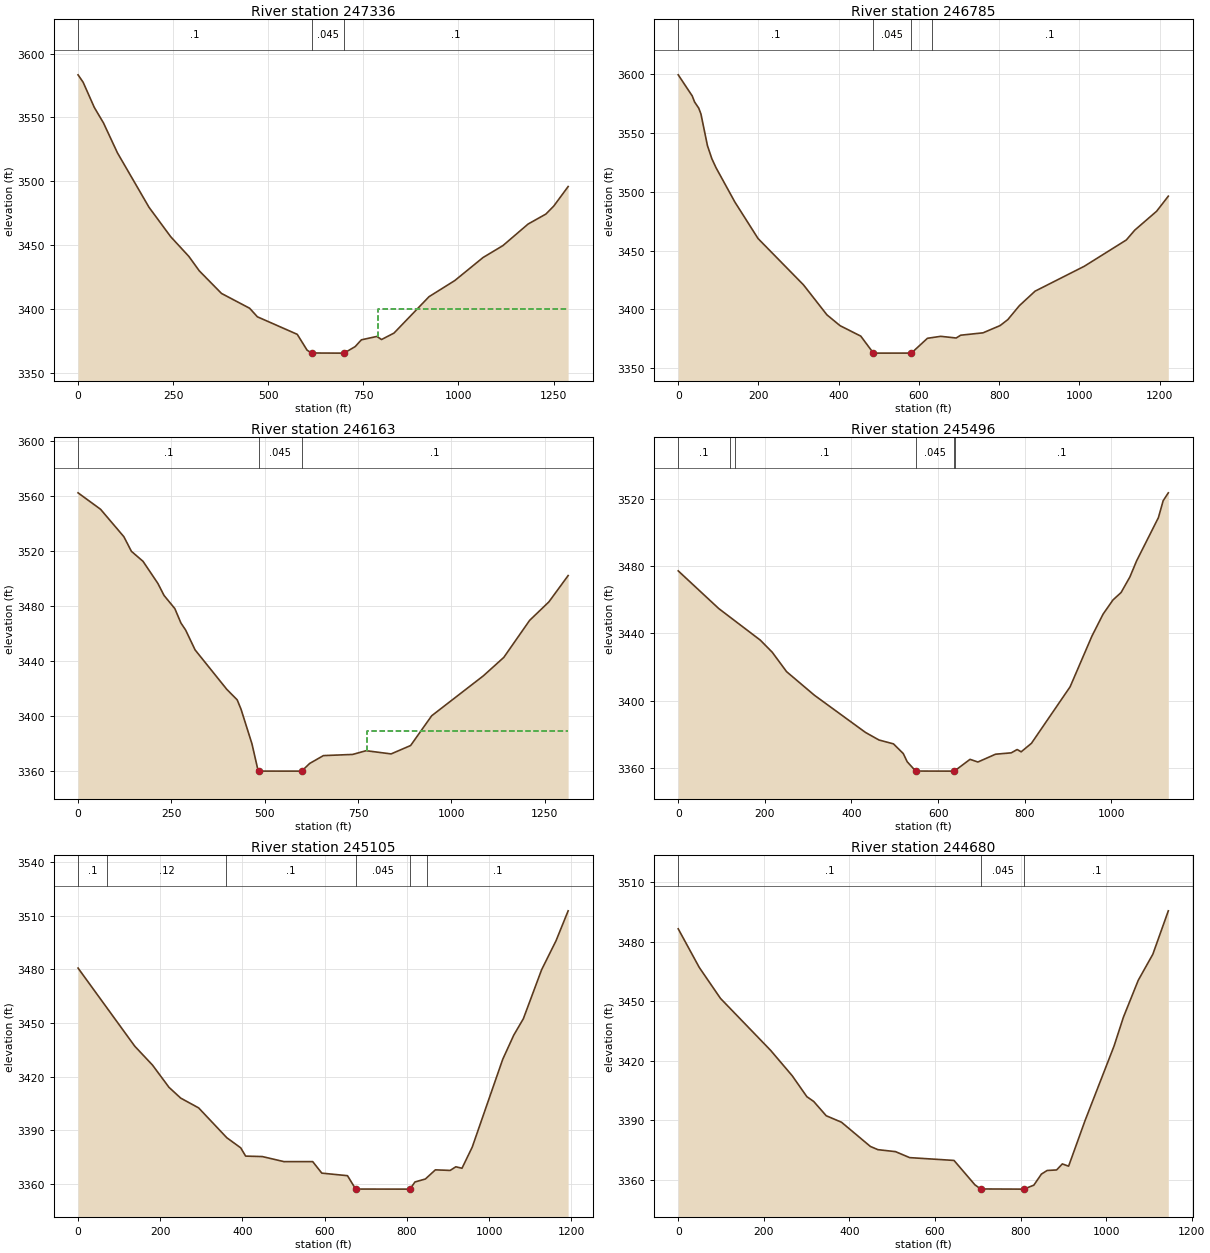
Type RM Length L Ch R = 1 ,247336  ,568.4,550.8,530.2
XS GIS Cut Line= 4
2302335.96490021 619387.528712542302606.63991064619733.833505297
 2302698.1917524620191.5927141152302909.15903995620510.033902857
#Sta/Elev= 30
       0 3583.35    13.3 3577.58    42.7 3557.84    66.9 3545.67   103.6 3522.25
   186.5 3479.67   243.5 3456.63   291.5 3441.12   318.6 3429.92   377.1 3412.19
   451.1 3400.58   471.5 3393.89   576.3 3380.16     602  3367.8   613.7 3365.56
   687.7 3365.46   699.9 3365.56   728.5 3370.58   744.8 3375.88   785.6 3378.52
   797.8 3376.11   830.5 3381.15   922.7 3409.67   990.3 3422.27  1064.8 3440.35
  1116.7 3449.61  1183.1 3466.54  1229.7 3474.32  1250.4 3480.56  1288.3 3495.88
#Mann= 3 ,-1,0
       0      .1       0   613.7    .045       0   699.9      .1       0
#XS Ineff= 2 , 0
                          788.45            3400
Permanent Ineff=
       F       F
Bank Sta=613.7,699.9
XS Rating Curve= 0 ,0
Exp/Cntr(USF)=0,0
Exp/Cntr=0.3,0.1

Type RM Length L Ch R = 1 ,246785  ,635.4,622.3,606
XS GIS Cut Line= 3
2301794.61487935619805.482772764 2302053.3483452620044.313664321
2302562.85424719620748.864794414
#Sta/Elev= 30
       0 3599.62    34.9 3581.68    40.8 3576.52    51.1 3571.31    56.6 3566.38
    72.9 3539.34    83.8 3528.29    94.3 3520.57   141.1 3491.48     199 3460.35
   312.3 3420.92   370.6 3395.46   403.5 3386.21     455 3377.35   486.6 3362.87
   581.1  3362.9   621.2 3375.49   654.3 3377.16   692.8 3375.74   704.2 3378.13
   759.7 3380.13   802.4 3386.32   821.7 3391.44   850.3 3403.22   889.4 3415.56
  1012.2 3436.77  1116.8  3459.1  1138.1 3467.54  1192.4 3483.56  1221.6  3496.4
#Mann= 4 ,-1,0
       0      .1       0   486.6    .045       0   581.1    .025       0
  632.11      .1       0
Bank Sta=486.6,581.1
XS Rating Curve= 0 ,0
Exp/Cntr(USF)=0,0
Exp/Cntr=0.3,0.1

Type RM Length L Ch R = 1 ,246163  ,677.7,666.5,653.9
XS GIS Cut Line= 2
2301253.26485849620231.3978627082302272.27666246621059.344953438
#Sta/Elev= 30
       0 3562.44    60.4 3550.47   122.8 3530.54   142.9 3519.96   174.1 3512.67
   213.8 3496.66   230.5 3487.84   259.3 3478.33   275.6 3467.88   288.3 3462.72
   313.6 3448.31   398.6 3419.63   426.4 3412.01   436.7 3405.19   465.9 3380.09
     481 3362.22   484.9 3360.27   599.1 3360.24   620.4 3365.79   657.3 3371.52
   735.6 3372.36   771.7 3375.08   838.7 3372.75   890.9 3378.83   947.4 3400.46
  1086.1 3429.53  1140.7  3442.9  1209.8 3469.77  1261.3 3483.17    1313 3502.32
#Mann= 3 ,-1,0
       0      .1       0   484.9    .045       0   599.1      .1       0
#XS Ineff= 2 , 0
                          775.31         3389.22
Permanent Ineff=
       F       F
Bank Sta=484.9,599.1
XS Rating Curve= 0 ,0
Exp/Cntr(USF)=0,0
Exp/Cntr=0.3,0.1

Type RM Length L Ch R = 1 ,245496  ,383.8,390.6,399.2
XS GIS Cut Line= 4
 2300938.8041846620800.6114875852301257.24537334621103.130616891
2301598.07674535621284.8249958492301837.48773849621475.475107599
#Sta/Elev= 30
       0 3477.03    93.7 3454.62   189.5 3435.89   217.1 3428.69   250.2 3417.15
   314.4 3403.16   432.2 3381.08   463.6 3376.55   496.9 3374.27   519.6 3368.51
   528.6 3363.65   548.2 3358.11   637.5 3358.07   673.7 3365.07   691.9 3363.49
   732.6 3368.12   768.9 3368.93   782.5  3370.9   791.8 3369.55   815.5 3374.59
   904.8 3408.18   955.3 3438.37   980.9 3451.34  1003.7 3459.75  1022.5 3464.19
  1042.9 3473.48  1058.2 3482.93  1108.6 3508.65  1119.6  3518.7  1131.5 3523.39
#Mann= 6 ,-1,0
       0      .1       0     120     .12       0     130      .1       0
   548.2    .045       0   637.5    .025       0  639.23      .1       0
Bank Sta=548.2,637.5
XS Rating Curve= 0 ,0
Exp/Cntr(USF)=0,0
Exp/Cntr=0.3,0.1

Type RM Length L Ch R = 1 ,245105  ,392.5,425.9,450.7
XS GIS Cut Line= 2
2300585.11846371621062.6617653942301543.84244321 621771.85711325
#Sta/Elev= 30
       0 3480.72   138.1 3436.96   181.3 3426.39   221.3 3413.97   249.9 3407.92
   293.5 3402.45     362 3385.75   395.8 3380.11   407.8 3375.48   448.2 3375.23
   501.3 3372.38     571 3372.39   593.1 3365.95   655.6 3364.52   675.5 3357.04
   804.6    3357   807.6 3357.02   819.8 3361.01     845 3362.65   869.5 3367.79
   905.5 3367.47   919.2  3369.5   934.2 3368.68   959.1  3380.5  1033.3 3429.64
  1060.2 3443.19  1083.5 3452.36  1127.9 3479.76  1163.1 3496.04  1192.5 3512.75
#Mann= 6 ,-1,0
       0      .1       0      70     .12       0     360      .1       0
   675.5    .045       0   807.6    .025       0     850      .1       0
Bank Sta=675.5,807.6
XS Rating Curve= 0 ,0
Exp/Cntr(USF)=0,0
Exp/Cntr=0.3,0.1

Type RM Length L Ch R = 1 ,244680  ,497.3,491.6,490
XS GIS Cut Line= 4
2300397.45416374621170.7993694982300715.89535248621481.279528522
2300930.84315488621927.0971927622301070.16117496622078.356757415
#Sta/Elev= 30
       0 3486.53    49.2 3467.04    98.8  3451.4   216.1 3425.16   266.4 3412.38
   300.6 3401.82   316.6 3399.41   345.9 3392.19   381.6 3388.92   449.1 3376.69
   466.8 3375.07   507.8 3374.08   540.8 3371.06   644.5 3369.64   693.3 3357.35
   706.6 3355.25   804.6 3355.16   808.8 3355.26     831 3357.15   848.7 3362.74
   862.1 3364.57   884.3 3364.84   897.6 3367.88   912.3 3366.75   950.6 3389.68
  1018.4 3427.32  1040.4 3441.95  1075.1 3460.59  1109.1 3473.69  1145.3 3495.61
#Mann= 3 ,-1,0
       0      .1       0   706.6    .045       0   808.8      .1       0
Bank Sta=706.6,808.8
XS Rating Curve= 0 ,0
Exp/Cntr(USF)=0,0
Exp/Cntr=0.3,0.1

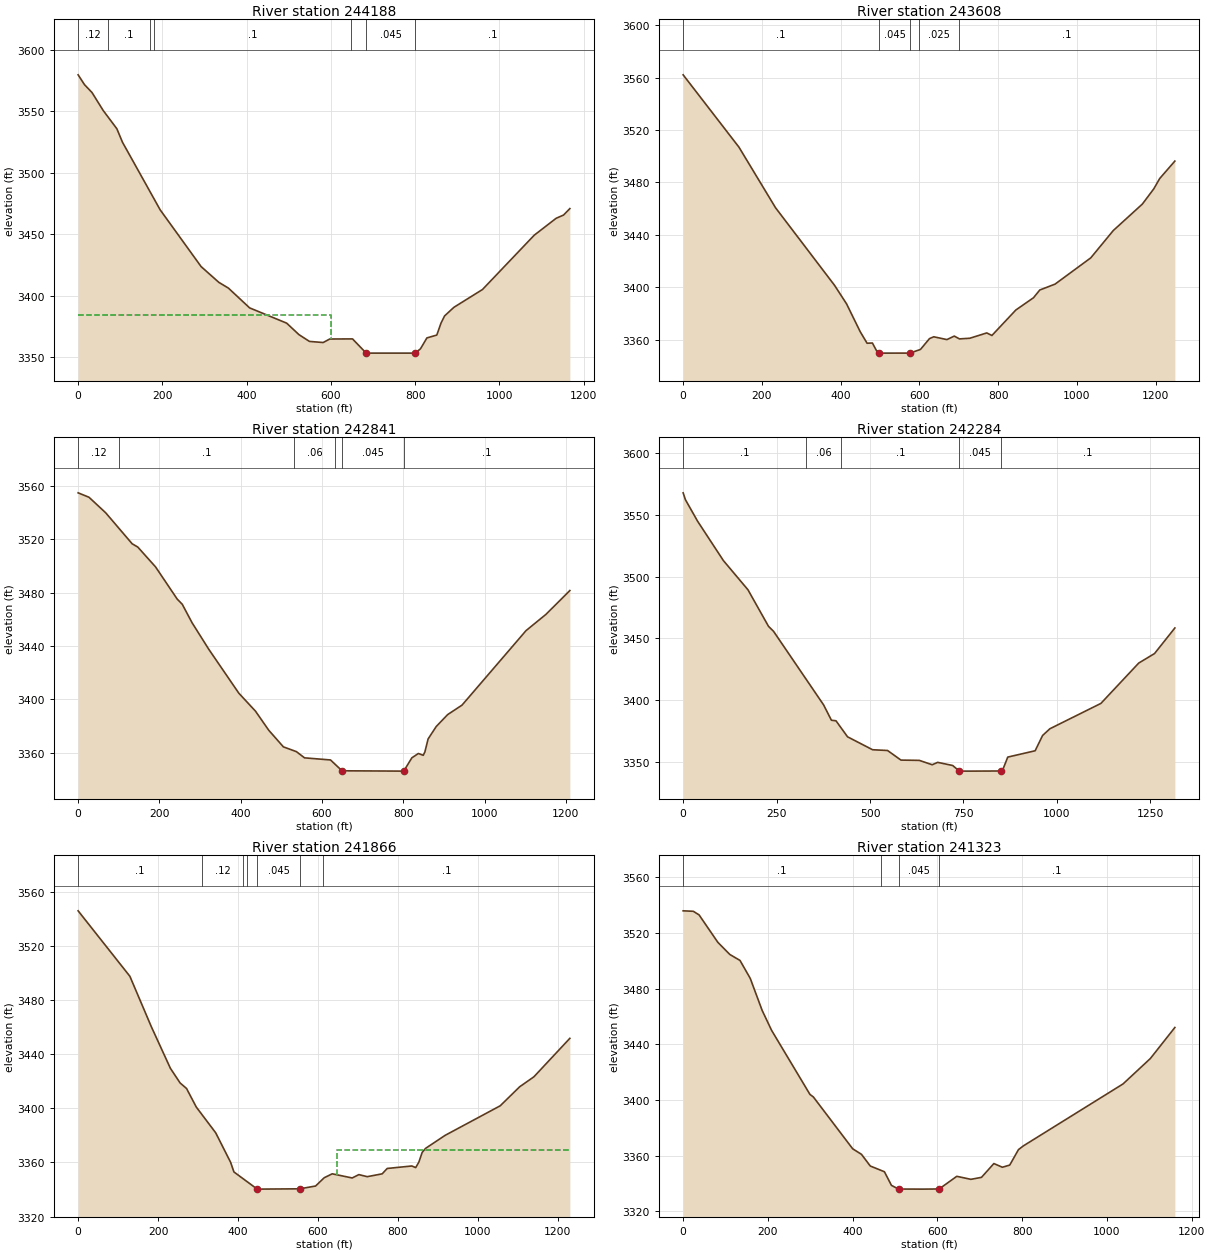
Type RM Length L Ch R = 1 ,244188  ,596.5,579.4,543.7
XS GIS Cut Line= 4
2299895.90929147621588.7534297232300313.86335169621819.623291562
 2300508.9085798622150.0060248822300767.64204565622313.207134113
#Sta/Elev= 30
       0  3579.5    15.2 3571.48    32.9 3565.15    59.4 3550.58    91.9  3535.7
   105.4 3524.67   194.8  3469.8   291.9 3423.74   333.9 3410.97   356.7 3406.27
     407 3390.22   494.9 3377.82   524.1 3368.48     549 3362.98   581.5 3362.08
   597.1 3364.93   651.2 3365.02   683.7 3353.48   799.8 3353.47   812.5 3356.98
   827.7 3365.82   851.2 3368.15   861.1 3377.77   869.7 3383.69   891.9  3390.7
   959.6 3405.13  1082.5 3449.27  1134.6 3463.02    1152 3465.61    1167 3470.86
#Mann= 7 ,-1,0
       0     .12       0      70      .1       0     170     .12       0
     180      .1       0  647.48    .025       0   683.7    .045       0
   799.8      .1       0
#XS Ineff= 2 , 0
          599.57 3384.05
Permanent Ineff=
       F       F
Bank Sta=683.7,799.8
XS Rating Curve= 0 ,0
Exp/Cntr(USF)=0,0
Exp/Cntr=0.3,0.1

Type RM Length L Ch R = 1 ,243608  ,771.9,767.5,752.1
XS GIS Cut Line= 2
 2299501.8383204622173.8891140382300652.20711473 622659.51192687
#Sta/Elev= 30
       0 3562.21   141.7    3507   234.7 3460.69   384.6 3401.43     415 3387.32
   449.7 3366.04   467.1 3357.26   480.6 3357.43   492.8 3350.59   497.5  3349.7
   575.7 3349.72   602.7 3352.52   625.6 3360.79   636.4 3362.18   669.8 3360.04
   688.5 3362.71   701.6 3360.56   727.9 3361.06     771 3365.12   784.1 3363.18
   844.8 3382.61   889.7 3391.99   905.6 3397.89   944.4 3402.39  1035.1 3422.43
  1092.3 3443.31  1166.1 3463.51    1195 3475.09  1210.2 3483.04  1248.7 3496.35
#Mann= 5 ,-1,0
       0      .1       0   497.5    .045       0   575.7      .1       0
     600    .025       0     700      .1       0
Bank Sta=497.5,575.7
XS Rating Curve= 0 ,0
Exp/Cntr(USF)=0,0
Exp/Cntr=0.3,0.1

Type RM Length L Ch R = 1 ,242841  ,586.9,557.3,522.1
XS GIS Cut Line= 3
2299334.07659473623024.1427867082299784.56338545623124.062300609
2300532.79166896623145.134739703
#Sta/Elev= 30
       0 3554.69    26.7 3551.38    67.7 3539.78     133 3516.51   146.8 3514.08
   190.6 3499.19   243.9 3475.06   256.2 3471.25   280.4 3457.38   321.7 3437.42
   395.5  3404.6   436.5 3391.14     469  3376.9   505.1 3364.42   537.1 3360.85
   557.1  3356.2   621.1 3354.61  649.36  3346.5   801.2 3346.25   821.2 3356.21
   837.2 3359.46   849.2 3358.11   853.2 3360.58   861.2 3370.35   881.2 3379.67
   909.2 3388.57   944.7  3395.7  1102.2  3451.5    1151 3463.62    1210  3481.5
#Mann= 6 ,-1,0
       0     .12       0     100      .1       0  531.43     .06       0
  631.43      .1       0  649.36    .045       0   801.2      .1       0
Bank Sta=649.36,801.2
XS Rating Curve= 0 ,0
Exp/Cntr(USF)=0,0
Exp/Cntr=0.3,0.1

Type RM Length L Ch R = 1 ,242284  ,451.7,417.4,370.6
XS GIS Cut Line= 4
2299438.15008265623913.374107544 2299844.1625983623837.744325218
2300317.84386655 623602.893948522300562.14817886623320.028292102
#Sta/Elev= 30
       0 3567.89     6.1 3562.33    38.7 3544.86   107.8 3512.93   173.4  3489.3
   228.3  3459.7     242 3455.56   375.8 3395.96   396.7 3383.52   408.9  3383.1
   439.8 3370.11   506.8 3359.62   546.9    3359   582.7 3351.22   631.8    3351
   666.4 3347.44   680.9 3349.39   721.1 3346.84   738.9 3342.31   765.5 3342.28
   850.5 3342.39     855 3343.32   868.4 3353.65   941.7 3358.79   961.6 3371.16
     981  3376.6  1117.6 3397.18  1218.8 3429.88  1261.1  3437.6  1315.5 3458.33
#Mann= 5 ,-1,0
       0      .1       0     330     .06       0     423      .1       0
   738.9    .045       0   850.5      .1       0
Bank Sta=738.9,850.5
XS Rating Curve= 0 ,0
Exp/Cntr(USF)=0,0
Exp/Cntr=0.3,0.1

Type RM Length L Ch R = 1 ,241866  ,567.1,543,507.4
XS GIS Cut Line= 4
2300382.02860456624525.0459900672300325.80489627624176.088088257
2300469.10343121623686.4847605652300628.32402558623356.102027245
#Sta/Elev= 30
       0 3545.79   129.5 3497.46   182.9  3460.4   230.8 3429.55   255.1 3418.72
   271.3 3414.59   295.6 3400.93   344.3 3381.85   381.5 3360.11   389.8 3352.99
   448.2 3340.31   554.4 3340.54   594.1  3342.6   615.6 3348.69   635.7 3351.62
   685.7 3348.55   702.4 3351.03   723.3 3349.51   760.7 3351.59   773.3 3355.56
   834.9  3357.4   844.6  3356.2   852.5 3360.27   860.8 3367.42   869.5 3370.45
   918.3 3380.03    1056 3401.83  1104.8  3415.9  1140.3 3423.24  1230.3 3451.66
#Mann= 7 ,-1,0
       0      .1       0     310     .12       0  413.46    .025       0
  423.46      .1       0   448.2    .045       0   554.4    .025       0
  613.46      .1       0
#XS Ineff= 2 , 0
                          647.94          3369.4
Permanent Ineff=
       F       F
Bank Sta=448.2,554.4
XS Rating Curve= 0 ,0
Exp/Cntr(USF)=0,0
Exp/Cntr=0.3,0.1

Type RM Length L Ch R = 1 ,241323  ,727.6,691.5,629.4
XS GIS Cut Line= 4
2300883.07697657624482.5877324222300926.86264002624088.516761353
2300819.38873882623718.3288794392300763.66153079623344.160482667
#Sta/Elev= 30
       0 3535.78      24 3535.45    37.6 3532.86    81.9 3513.16   110.1 3504.46
   134.2 3500.15   158.4 3487.24   186.5 3464.24   208.7 3449.98   299.2 3403.97
   307.3 3402.11     400 3364.92   420.8 3360.93   441.6 3352.53   474.9 3348.43
   491.6 3338.61   508.3    3336     566 3335.94   604.1 3336.05   645.7 3345.14
     679 3342.97     704  3344.4   733.2 3354.31   753.2 3351.65   770.7 3353.22
   791.2  3364.3   803.4 3367.11  1037.9 3411.46  1102.5 3429.74  1160.3 3452.02
#Mann= 4 ,-1,0
       0      .1       0   466.5    .025       0   508.3    .045       0
   604.1      .1       0
Bank Sta=508.3,604.1
XS Rating Curve= 0 ,0
Exp/Cntr(USF)=0,0
Exp/Cntr=0.3,0.1

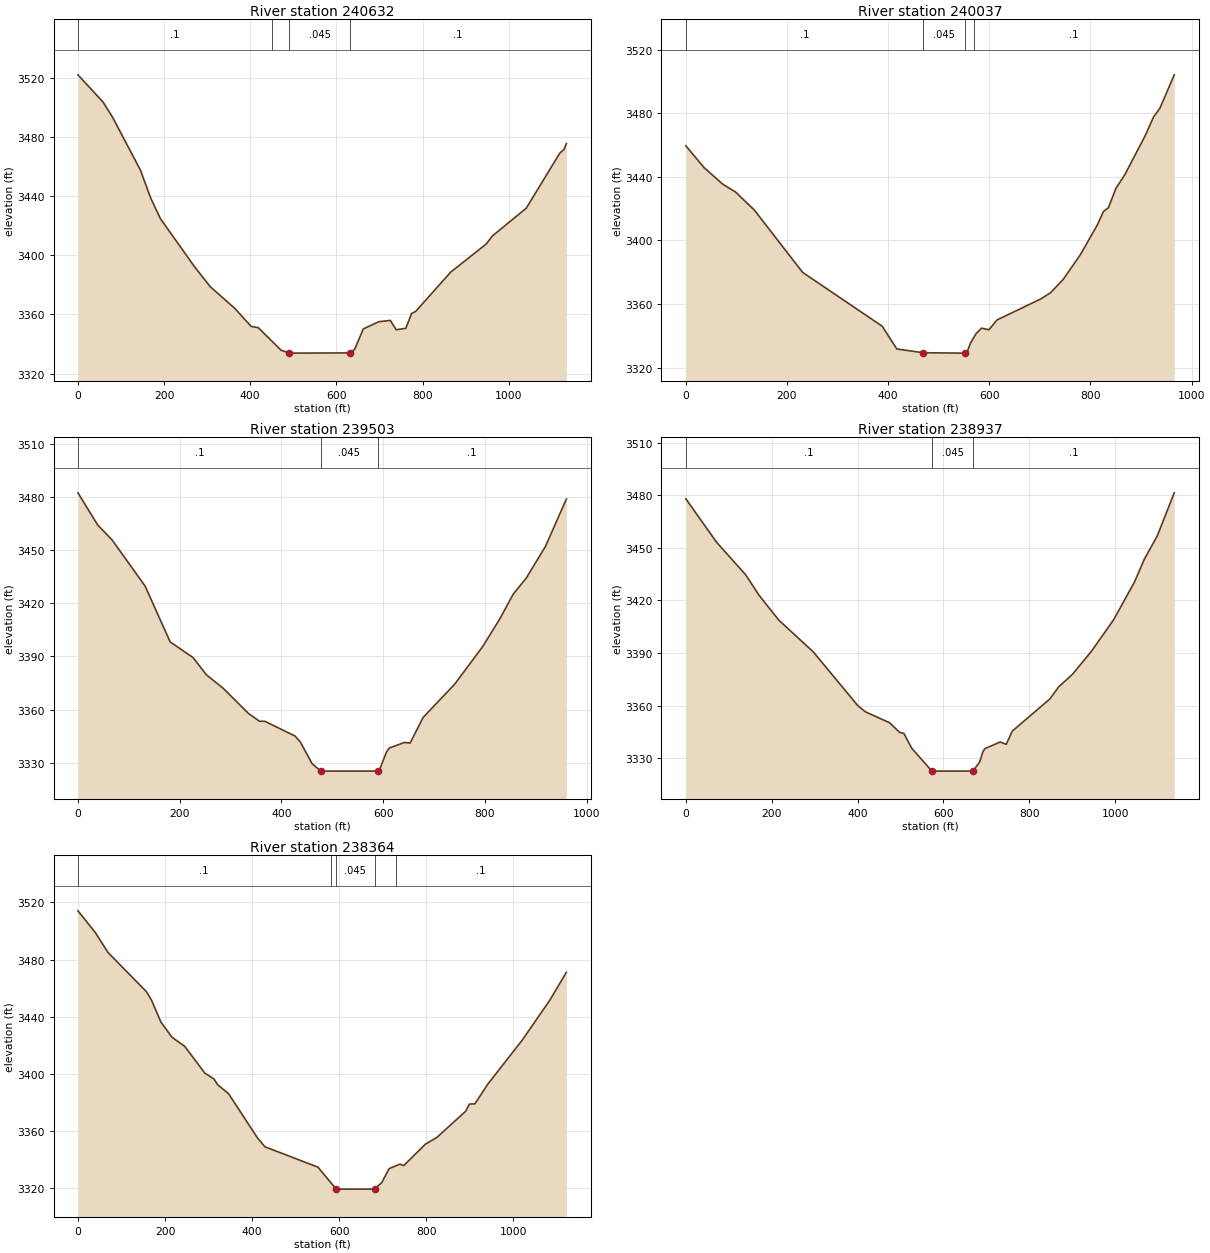
Type RM Length L Ch R = 1 ,240632  ,581.4,594.5,615.5
XS GIS Cut Line= 4
 2301858.3031171623885.5105035292301583.64759181623622.796522817
2301209.47919503623431.7318095712300998.51190749623172.998343718
#Sta/Elev= 30
       0 3522.07    58.3 3503.66      81 3493.06   145.2 3457.53     169 3438.64
   191.4 3424.79   270.5 3392.36   307.2 3378.76   365.1 3363.86   401.9 3351.97
   418.8 3351.05   471.6 3335.82   490.9 3333.96   496.3 3333.85     631    3334
   642.5 3336.41   662.4  3350.2   698.4 3355.08   725.3 3355.99   738.8 3349.66
   761.2 3350.64   774.7 3360.75   783.7 3361.94   865.5 3388.66     948 3407.68
   962.1 3413.05  1040.9  3431.9  1118.5 3469.01  1128.6 3471.71    1134 3475.62
#Mann= 4 ,-1,0
       0      .1       0  450.07    .025       0   490.9    .045       0
     631      .1       0
Bank Sta=490.9,631
XS Rating Curve= 0 ,0
Exp/Cntr(USF)=0,0
Exp/Cntr=0.3,0.1

Type RM Length L Ch R = 1 ,240037  ,534.2,534.1,534.4
XS GIS Cut Line= 2
2302113.05606809623415.8097501342301444.32957173622719.219649759
#Sta/Elev= 30
       0 3459.54    36.4 3445.71    73.2 3435.35    97.9 3430.56   135.4 3419.13
     231  3379.9   388.3 3346.03   417.1 3331.73   469.3 3329.35     550 3329.11
   552.6 3329.23     557 3330.57   562.6  3335.3   573.9 3341.42   584.6 3344.81
   599.4 3343.83   615.1 3349.95   702.3  3363.3   721.1 3367.11   746.4 3375.63
   780.5 3391.28   813.2 3409.57   825.7 3418.24   835.4 3420.58   850.3 3432.76
   867.7 3441.25   908.1 3465.87   924.7 3477.69     937 3483.03   965.6 3504.19
#Mann= 4 ,-1,0
       0      .1       0   469.3    .045       0   552.6    .025       0
     570      .1       0
Bank Sta=469.3,552.6
XS Rating Curve= 0 ,0
Exp/Cntr(USF)=0,0
Exp/Cntr=0.3,0.1

Type RM Length L Ch R = 1 ,239503  ,555.1,565.8,577
XS GIS Cut Line= 2
 2302523.0490986623081.4465019542301866.26414682 622380.87588672
#Sta/Elev= 30
       0 3482.34    38.7 3464.22    67.3 3455.69     132 3429.72   181.3 3398.21
   226.4 3389.32   252.6 3379.61   285.5 3372.03   334.8 3357.94   356.8 3353.41
   367.3 3353.39   426.7  3345.1     437  3341.8   460.4 3329.43   477.6 3325.28
   520.1 3325.26     589  3325.3   593.7 3326.54   606.6  3336.1   612.4 3338.33
   641.9 3341.44   653.1  3341.1   678.6 3355.56   740.6 3374.31   795.4 3395.42
   828.6 3410.79   855.7 3425.11   881.5 3434.26   919.1 3452.09   960.3 3478.84
#Mann= 3 ,-1,0
       0      .1       0   477.6    .045       0     589      .1       0
Bank Sta=477.6,589
XS Rating Curve= 0 ,0
Exp/Cntr(USF)=0,0
Exp/Cntr=0.3,0.1

Type RM Length L Ch R = 1 ,238937  ,564.7,573.2,586.5
XS GIS Cut Line= 2
2302944.98367368622898.3428184272302351.88695965621927.097192762
#Sta/Elev= 30
       0    3478    71.7 3453.22   139.7 3434.59   170.1 3423.17   216.5 3408.83
   296.6 3390.79   400.7 3360.07   418.5 3356.51   474.7 3350.29   498.2 3344.78
   508.1 3344.17   526.3 3335.76   573.2 3322.74   577.8 3322.69   669.3 3322.73
   684.6 3327.93   692.3 3333.79   696.9 3335.53   732.5 3339.31   746.6 3337.97
   760.6 3345.51   848.2 3363.85   868.8 3370.78   901.2 3377.98   945.6 3391.22
   996.6 3408.94  1045.4 3430.57  1068.4 3443.62  1098.1 3456.64    1138  3481.4
#Mann= 3 ,-1,0
       0      .1       0   573.2    .045       0   669.3      .1       0
Bank Sta=573.2,669.3
XS Rating Curve= 0 ,0
Exp/Cntr(USF)=0,0
Exp/Cntr=0.3,0.1

Type RM Length L Ch R = 1 ,238364  ,525.1,536.5,553.1
XS GIS Cut Line= 2
2303315.17155559622703.2975903222302980.80830741621632.539093175
#Sta/Elev= 30
       0 3514.11    39.9 3498.88    69.3 3484.84   157.3  3457.5   169.3 3451.32
   190.8  3436.1   215.9 3425.66   245.3 3419.21   291.4  3400.5   312.3 3396.41
   320.7 3392.42   345.8 3386.14   412.8 3354.93   429.6  3348.9   551.2 3334.68
   593.1  3319.3   681.1 3319.31   697.8 3323.94   714.6 3333.66   739.7 3336.81
   748.1 3335.78   798.4  3350.9   823.6 3355.32   890.6 3373.89     899 3378.83
   911.6    3379   940.9 3392.65  1020.5  3423.7  1083.3 3451.38  1121.7 3471.06
#Mann= 5 ,-1,0
       0      .1       0     580     .05       0   593.1    .045       0
   681.1     .05       0     730      .1       0
Bank Sta=593.1,681.1
XS Rating Curve= 0 ,0
Exp/Cntr(USF)=0,0
Exp/Cntr=0.3,0.1