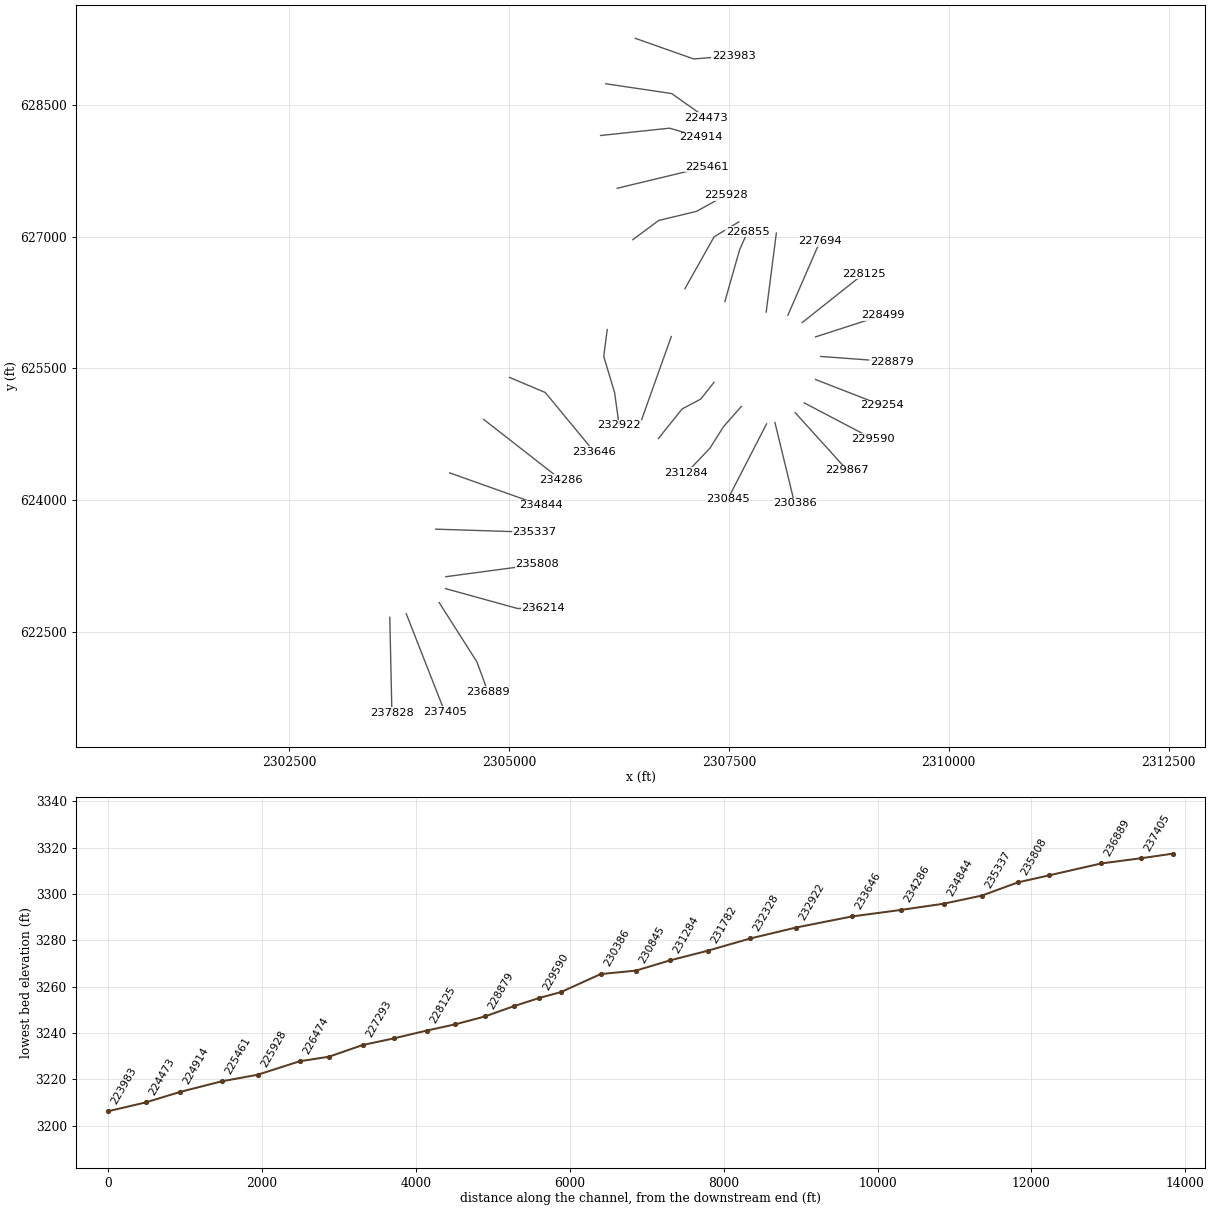
HEC-RAS study SHAVERSFK.prj: SHAVERSFK

--- SHAVERSFK.g01 (geometry) --- (continued)

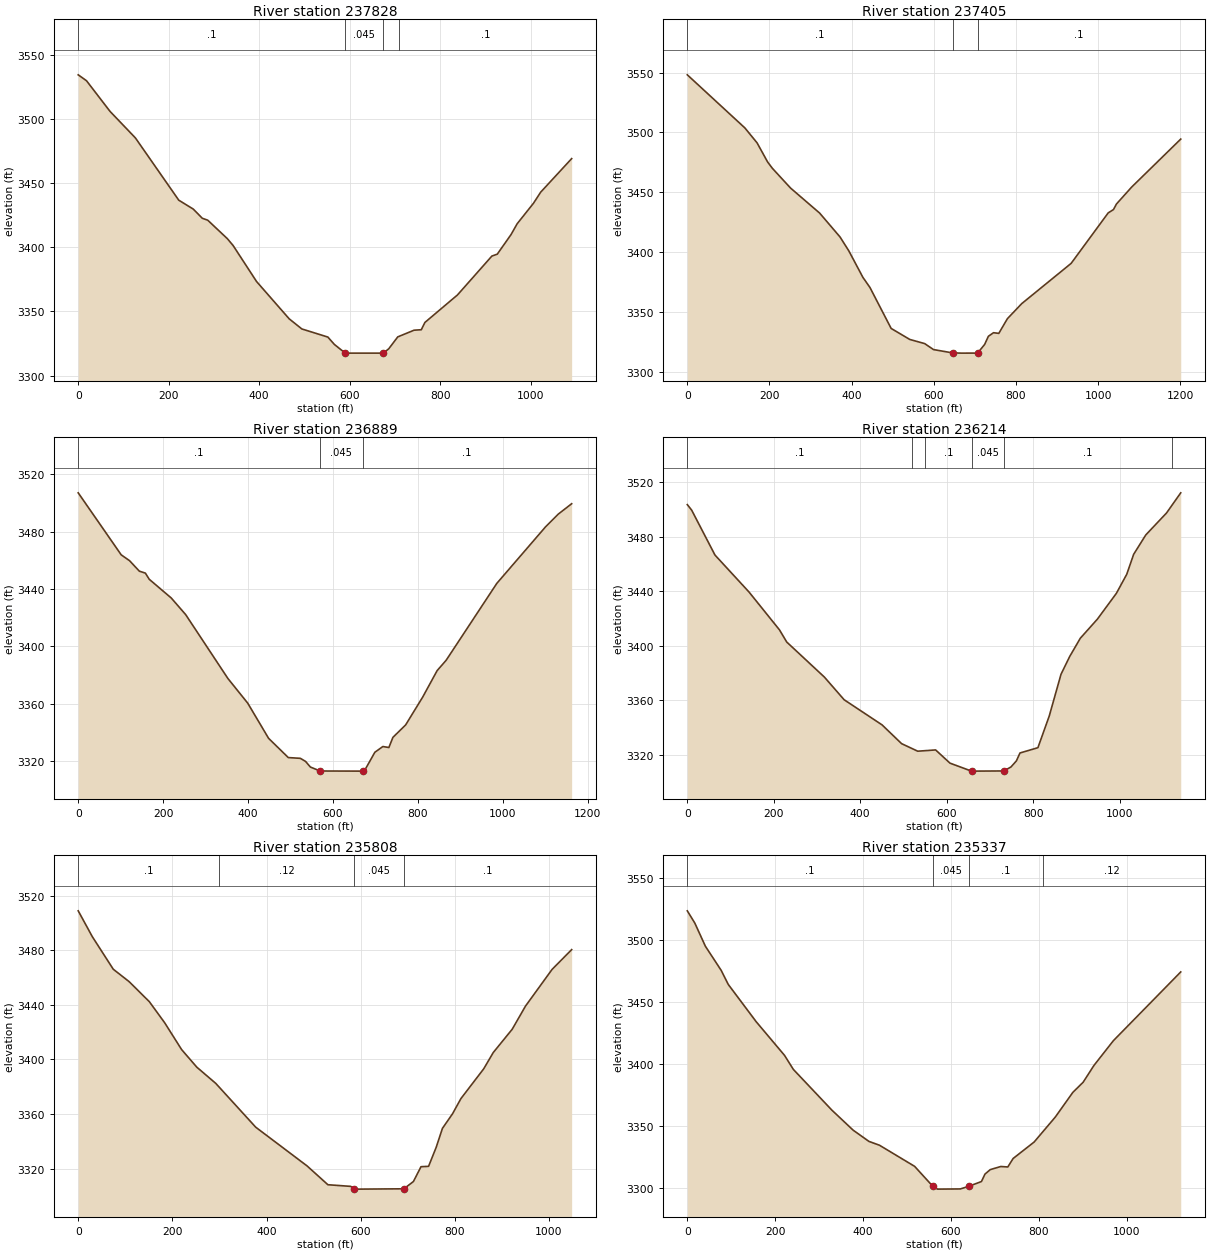
Type RM Length L Ch R = 1 ,237828  ,413.5,422.4,436
XS GIS Cut Line= 2
2303645.55428891622667.4729565892303669.43737807621576.811885145
#Sta/Elev= 30
       0 3534.66    18.3 3530.07    70.3 3506.15   126.5  3485.4   222.3 3436.83
   254.4 3429.87   274.4  3422.7   286.4  3421.2   329.8 3406.77   342.4 3401.48
   394.4 3373.31   466.4 3344.25   494.4 3336.34   551.9 3330.01   566.4 3324.23
   590.4 3317.47   674.5 3317.47   686.5 3320.84   706.5 3330.15   742.5 3335.36
   758.5 3335.73   766.5 3341.42   838.5 3362.88   914.5  3393.2   926.5 3394.72
   956.9 3409.99   970.5 3418.46  1006.5 3434.42  1022.5 3443.12  1090.9 3469.27
#Mann= 4 ,-1,0
       0      .1       0   590.4    .045       0   674.5    .025       0
     710      .1       0
Bank Sta=590.4,674.5
XS Rating Curve= 0 ,0
Exp/Cntr(USF)=0,0
Exp/Cntr=0.3,0.1

Type RM Length L Ch R = 1 ,237405  ,509.7,515.8,524.7
XS GIS Cut Line= 2
 2303832.6384873622707.2781051812304270.49512182621588.753429723
#Sta/Elev= 30
       0 3548.11   140.2  3503.7   169.8 3491.25   195.7 3475.15   207.2 3469.91
   251.4 3453.43   322.2 3432.51   371.7  3412.6   393.2 3400.94   427.5 3378.77
   444.7 3370.28   496.2  3336.1   541.5 3326.89   577.9  3323.4   599.3 3318.41
   646.6 3315.59     668 3315.44   706.7 3315.47   723.9 3322.75   732.9  3329.5
   745.4 3332.51   758.3 3331.95   779.2 3344.22   814.1 3356.82   934.4 3390.48
  1024.6 3432.68  1037.5 3435.47  1044.7  3440.1  1081.7 3454.26  1201.2 3494.38
#Mann= 3 ,-1,0
       0      .1       0   646.6    .045       0   706.7      .1       0
Bank Sta=646.6,706.7
XS Rating Curve= 0 ,0
Exp/Cntr(USF)=0,0
Exp/Cntr=0.3,0.1

Type RM Length L Ch R = 1 ,236889  ,649.9,675.4,711.9
XS GIS Cut Line= 3
2304206.80688407622834.6545806792304636.70248888  622157.9670546
2304760.09844951621819.623291561
#Sta/Elev= 30
       0 3506.93   101.3 3463.74   120.9  3459.7   143.9  3452.4   158.1 3451.05
   167.2 3446.76   218.9 3433.76   252.9 3422.21   352.4 3377.71   399.1 3360.53
   448.3 3336.02   494.7 3322.63     523 3322.11   535.3 3319.96   546.7 3316.04
   569.5 3313.29   669.9  3313.2   674.7 3313.85   698.4 3326.31   717.3 3330.32
   731.5 3329.65     741 3336.72   770.9 3345.35   811.1 3364.75   845.1 3383.17
   866.4  3390.4   985.6 3443.89  1100.6 3483.34  1130.4 3492.13  1161.8 3499.33
#Mann= 3 ,-1,0
       0      .1       0   569.5    .045       0   669.9      .1       0
Bank Sta=569.5,669.9
XS Rating Curve= 0 ,0
Exp/Cntr(USF)=0,0
Exp/Cntr=0.3,0.1

Type RM Length L Ch R = 1 ,236214  ,395.7,406.4,426.8
XS GIS Cut Line= 3
2304278.45615154 622993.875175052305098.44221255622766.985828071
2305389.01979728622774.946857789
#Sta/Elev= 30
       0 3503.41    10.1 3499.36      64 3466.46   142.9 3439.31   213.3 3411.59
     230  3402.7   317.2 3376.98   362.8  3360.4   450.6 3341.96   495.7 3328.23
     533 3322.69   574.5 3323.61   607.7 3313.93   657.5 3308.08   732.2 3308.21
   748.8 3311.14   761.3 3315.59   769.6 3321.38   811.1 3325.26   837.4 3348.56
   864.5 3379.05   884.5 3392.02   909.1 3405.44   948.6 3419.44   992.6 3438.38
  1016.6 3452.36  1032.6    3467  1060.6 3481.17  1108.6 3497.27  1141.5 3512.05
#Mann= 6 ,-1,0
       0      .1       0     520     .12       0     550      .1       0
   657.5    .045       0   732.2      .1       0  1120.8     .12       0
Bank Sta=657.5,732.2
XS Rating Curve= 0 ,0
Exp/Cntr(USF)=0,0
Exp/Cntr=0.3,0.1

Type RM Length L Ch R = 1 ,235808  ,470.7,470.5,461.5
XS GIS Cut Line= 2
 2304282.4366664623129.2126802662305321.35104467 623268.53070034
#Sta/Elev= 30
       0 3508.89      30 3489.94    74.4 3466.15   108.3 3456.98   151.1 3442.34
   183.8 3426.84   219.7 3407.24     252 3394.35   292.3 3382.46   377.1  3350.4
   486.1 3322.06   530.4 3308.26   578.9 3307.06   586.9 3305.08     595 3305.04
   691.9 3305.28   691.9 3305.29   712.1 3310.63   728.2 3321.47   744.3 3321.74
   760.5  3335.7   773.7 3349.55   795.1 3360.19     813 3371.36   861.4 3393.16
   881.6 3405.05   921.9 3422.14   950.2 3439.12  1006.7 3466.01  1048.2 3480.46
#Mann= 4 ,-1,0
       0      .1       0     300     .12       0   586.9    .045       0
   691.9      .1       0
Bank Sta=586.9,691.9
XS Rating Curve= 0 ,0
Exp/Cntr(USF)=0,0
Exp/Cntr=0.3,0.1

Type RM Length L Ch R = 1 ,235337  ,499.8,493.5,482.7
XS GIS Cut Line= 2
2304167.00173548623670.562701128 2305289.5069258623634.738067394
#Sta/Elev= 30
       0 3523.23    17.2 3513.32    41.2 3494.71    77.2 3475.28    93.2 3464.02
   156.9 3433.97   221.3 3406.94   241.3 3395.67   329.3 3362.79   377.4 3346.78
   413.4 3337.72   437.4 3334.63   517.4 3317.65  558.283301.792   569.5 3299.32
   621.5 3299.47   641.5 3301.71   669.5 3305.43   677.5 3311.41   689.5 3315.01
   713.5 3317.52   729.5 3317.15   741.6 3323.97   789.4 3337.21   837.6 3357.31
   877.6  3377.2     901 3385.33   925.6 3398.85   969.7 3418.72  1123.1 3474.06
#Mann= 4 ,-1,0
       0      .1       0  558.28    .045       0   641.5      .1       0
     810     .12       0
Bank Sta=558.28,641.5
XS Rating Curve= 0 ,0
Exp/Cntr(USF)=0,0
Exp/Cntr=0.3,0.1

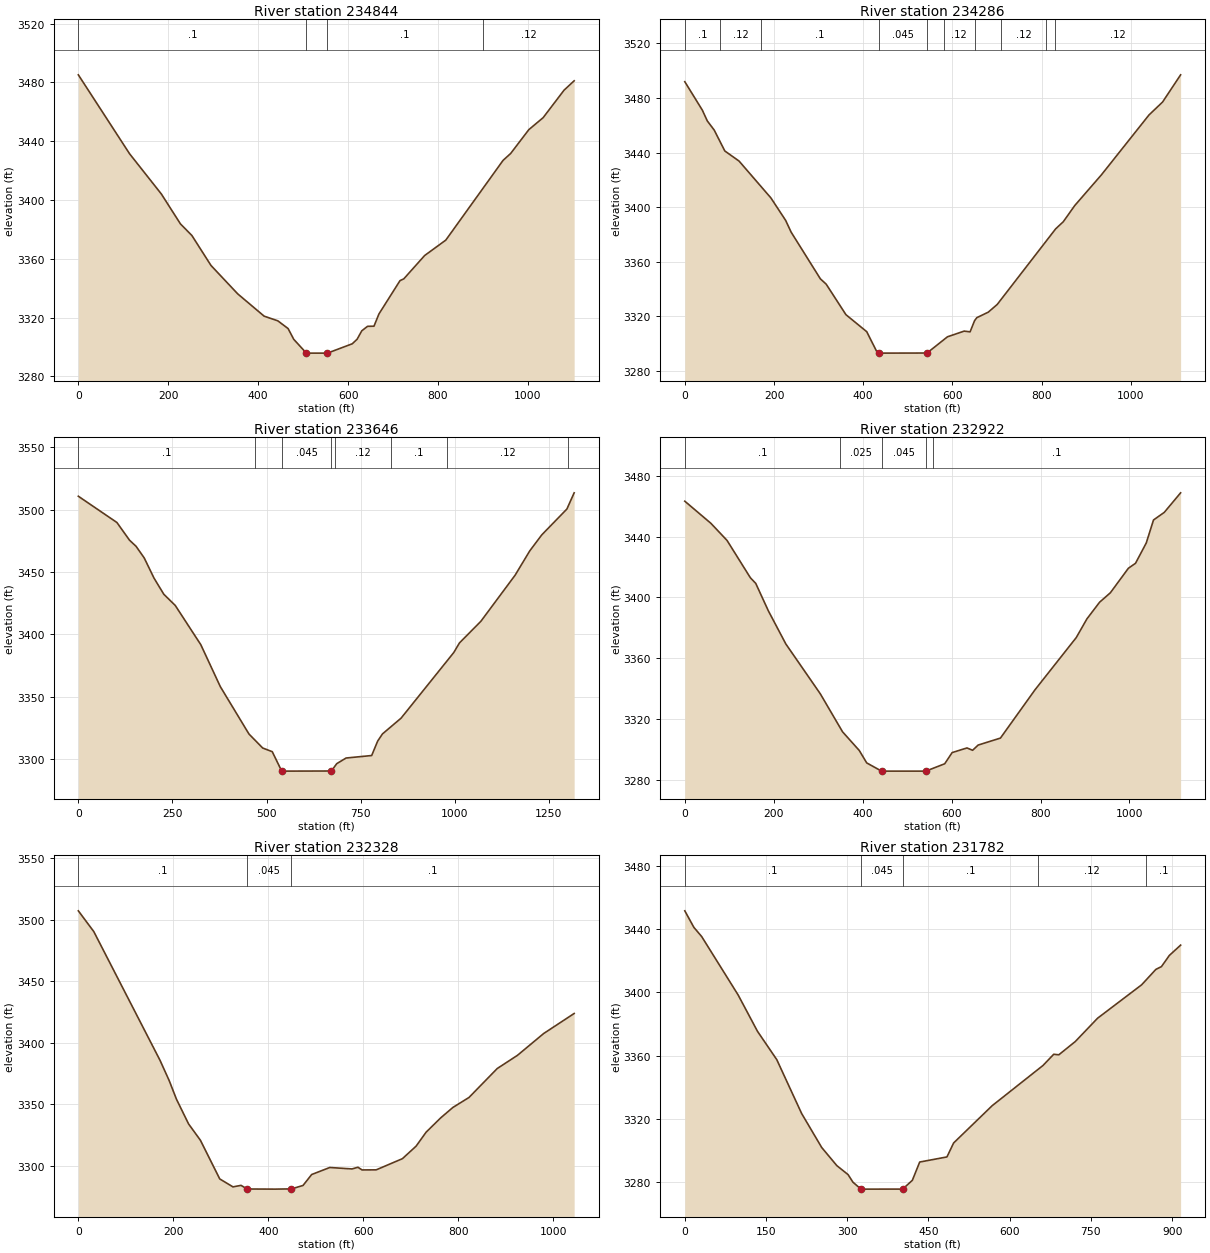
Type RM Length L Ch R = 1 ,234844  ,570.1,558,546
XS GIS Cut Line= 2
2304326.22232985624311.4255934732305365.13670813623941.237711559
#Sta/Elev= 30
       0 3485.17   113.9 3431.51   184.7 3404.09   227.1 3383.78   252.6 3375.86
   295.1 3355.48   354.5 3336.16   413.4 3320.97   443.7 3317.82   466.6 3312.56
   479.2 3305.22   507.3 3295.85   507.4 3295.84   554.1 3295.84   609.3 3302.19
   620.1 3305.29   630.5 3311.02   643.3 3314.07   657.6 3314.16   668.7  3322.5
   715.5 3345.14     724 3346.39   770.3 3362.23   817.4 3372.73   944.8 3426.98
   961.7 3431.67    1002 3447.85  1033.9 3456.03  1080.6 3474.79  1102.9  3481.1
#Mann= 4 ,-1,0
       0      .1       0   507.3    .045       0   554.1      .1       0
     900     .12       0
Bank Sta=507.3,554.1
XS Rating Curve= 0 ,0
Exp/Cntr(USF)=0,0
Exp/Cntr=0.3,0.1

Type RM Length L Ch R = 1 ,234286  ,653.1,639.2,625.9
XS GIS Cut Line= 2
 2304712.3322712624920.4443669432305588.04554024624235.795811146
#Sta/Elev= 30
       0 3491.91    39.3 3471.09    50.6 3463.09    65.8 3456.57    89.7  3441.2
   121.7 3433.77   193.1 3406.77   226.1 3390.35   238.4 3381.74     304 3347.52
     317 3343.64   361.3 3321.28   407.9 3308.84   429.6 3294.73   436.5 3293.14
   543.1 3293.21   588.8 3305.08   626.3 3309.26   639.6 3308.73   649.7 3316.94
   654.7 3319.11   680.4 3323.14   700.4 3328.78   831.4 3384.13   848.5 3389.34
   874.2 3401.19     934 3423.69  1040.7 3467.55  1071.1    3477  1111.6 3496.94
#Mann= 10 ,-1,0
       0      .1       0      80     .12       0     170      .1       0
   436.5    .045       0   543.1    .025       0     580     .12       0
     650      .1       0     710     .12       0     810      .1       0
     830     .12       0
Bank Sta=436.5,543.1
XS Rating Curve= 0 ,0
Exp/Cntr(USF)=0,0
Exp/Cntr=0.3,0.1

Type RM Length L Ch R = 1 ,233646  ,745.5,724.2,700.7
XS GIS Cut Line= 3
2305006.89037079625398.1061500572305412.90288644625226.944011108
2305970.17496674624550.256485029
#Sta/Elev= 30
       0 3510.75   102.5 3489.69     136  3475.5   153.3 3470.62     175 3461.29
   201.1 3445.07   227.1 3432.14   257.5 3423.17   325.4 3391.68   377.3 3358.01
   453.3 3320.08   489.8 3308.84   515.2  3305.9   540.1 3290.45   541.4 3290.31
   672.3 3290.41   686.4 3296.27   711.3 3300.82   779.3 3302.82   795.3 3314.45
   807.9 3320.13   857.4 3332.79   997.4 3385.42  1012.5 3393.12  1069.4 3410.46
  1160.3 3447.41  1199.4 3466.99  1231.3 3479.81  1297.9 3500.48  1317.2 3513.48
#Mann= 8 ,-1,0
       0      .1       0  470.62    .025       0   540.1    .045       0
   672.3      .1       0  680.62     .12       0  830.62      .1       0
  980.62     .12       0 1300.62      .1       0
Bank Sta=540.1,672.3
XS Rating Curve= 0 ,0
Exp/Cntr(USF)=0,0
Exp/Cntr=0.3,0.1

Type RM Length L Ch R = 1 ,232922  ,622.3,594.2,561.5
XS GIS Cut Line= 4
2306117.45401653625943.4366857792306077.64886794625636.937041614
2306201.04482857625226.9440111082306252.79152175624852.775614335
#Sta/Elev= 30
       0 3463.39    58.7 3448.81      95 3437.54   147.5 3412.93   159.6 3409.21
   187.8 3391.21   227.3 3369.28   304.8 3336.44   354.8 3311.42   392.4 3299.12
   409.1 3290.95   442.5 3285.53   542.1 3285.53   584.5 3290.38   601.2 3297.75
   634.6 3300.81   647.2 3299.26   659.7  3302.7   709.8  3307.3   787.5 3339.11
   880.3 3373.53   904.3 3385.85   932.8 3396.82   957.1 3403.08   997.5 3419.19
  1013.6 3422.49  1037.8 3435.91    1054    3451  1078.2 3456.01    1115  3468.9
#Mann= 5 ,-1,0
       0      .1       0  349.07    .025       0   442.5    .045       0
   542.1    .025       0  559.07      .1       0
Bank Sta=442.5,542.1
XS Rating Curve= 0 ,0
Exp/Cntr(USF)=0,0
Exp/Cntr=0.3,0.1

Type RM Length L Ch R = 1 ,232328  ,576.5,546,510.8
XS GIS Cut Line= 2
2306845.88823578625863.8263885932306495.60292816 624880.63921835
#Sta/Elev= 30
       0 3507.15    32.5  3490.3     172 3385.54   191.3 3369.05   206.6 3353.91
   232.1 3333.83     257 3320.56   297.7 3289.11   325.5 3282.65   342.5 3283.88
   355.3 3280.92   413.6 3280.82   448.7 3281.02     473  3283.8   491.1 3292.68
   529.3 3298.41   576.1 3297.25   588.6  3298.6   597.3 3296.43     627  3296.5
   682.2 3305.58     711 3315.77   732.1 3327.14   762.9 3338.81   788.4 3347.24
   822.3 3355.35   881.8 3378.91   924.3 3389.61   979.5 3407.36  1043.7 3423.66
#Mann= 3 ,-1,0
       0      .1       0   355.3    .045       0   448.7      .1       0
Bank Sta=355.3,448.7
XS Rating Curve= 0 ,0
Exp/Cntr(USF)=0,0
Exp/Cntr=0.3,0.1

Type RM Length L Ch R = 1 ,231782  ,481.3,497.6,511.1
XS GIS Cut Line= 4
2307331.51104861625342.3789420272307180.25148396625151.314228781
2306969.28419642625039.8598127212306698.60918598624701.516049682
#Sta/Elev= 30
       0  3451.4    16.8 3440.94    31.2 3435.13    98.5 3398.25   134.2 3375.31
   169.9 3357.37   215.8 3323.34   252.8  3301.9   280.8 3290.43   301.6 3284.73
   310.4 3280.02   325.2 3275.62   325.2 3275.61   334.1 3275.59   402.4 3275.61
   420.2 3281.17   433.8 3292.71   484.1 3295.93   496.4 3304.74   567.5 3328.27
   661.4 3353.69   681.3 3360.79   690.6 3360.44     721  3368.8   762.3 3383.57
   843.6 3404.66   869.9 3414.41   880.2 3416.16   894.8 3423.23   915.6 3429.74
#Mann= 5 ,-1,0
       0      .1       0   325.2    .045       0   402.4      .1       0
  652.29     .12       0  852.29      .1       0
Bank Sta=325.2,402.4
XS Rating Curve= 0 ,0
Exp/Cntr(USF)=0,0
Exp/Cntr=0.3,0.1

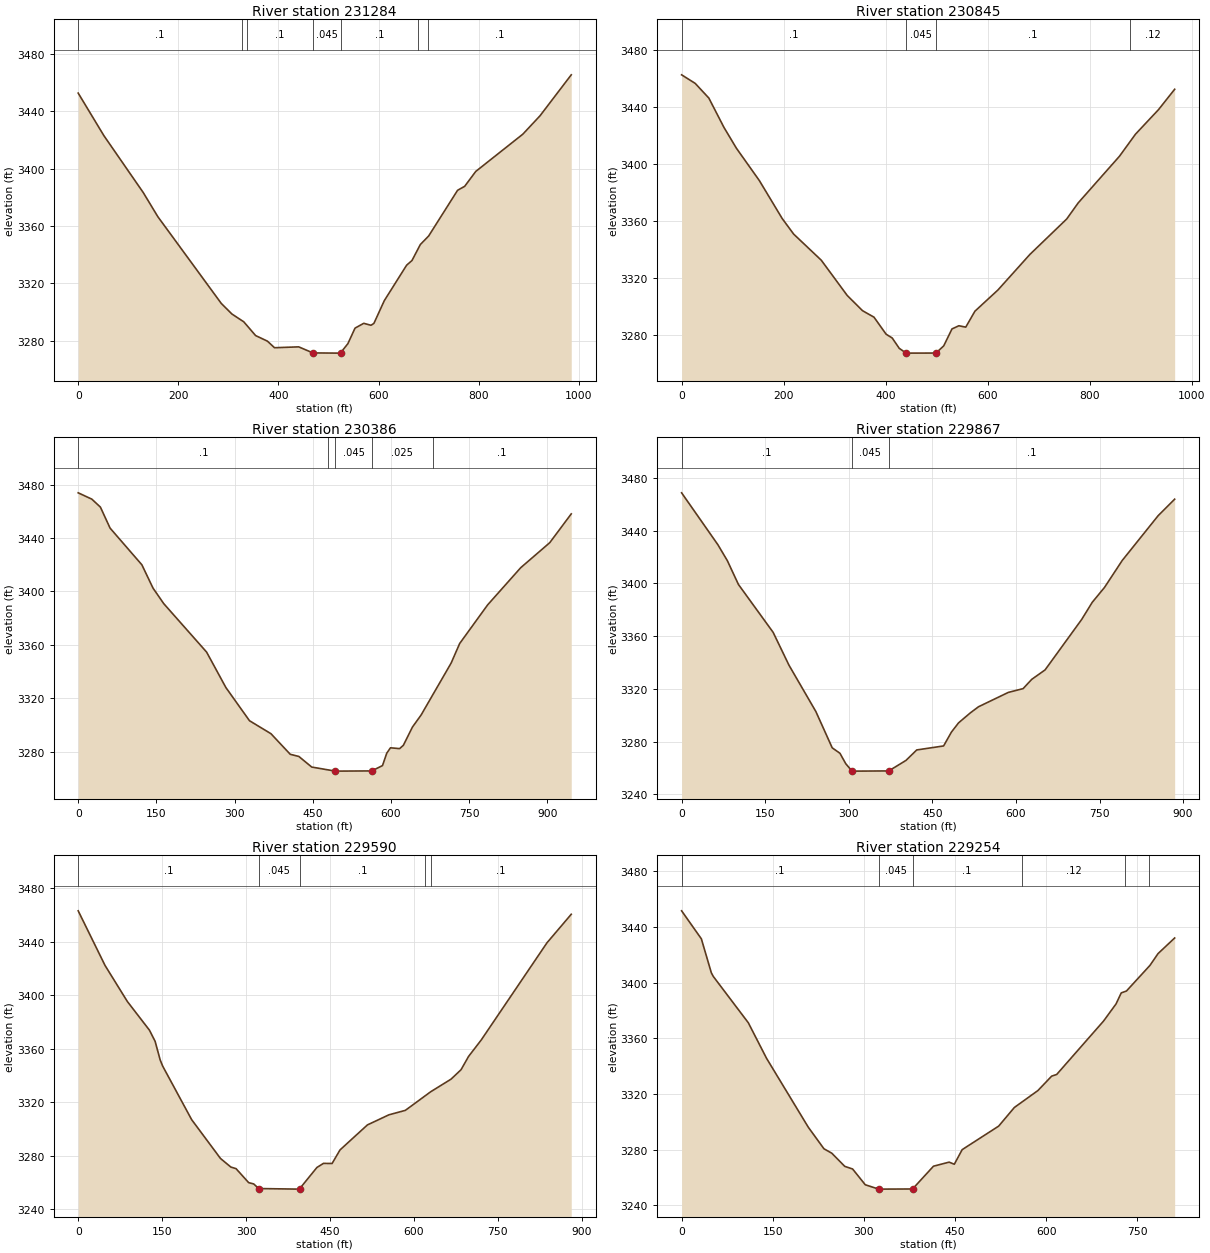
Type RM Length L Ch R = 1 ,231284  ,436.3,439,441.3
XS GIS Cut Line= 4
2307641.99120764625067.7234167362307438.98494981624836.853554898
 2307283.7448703624590.0616336222307017.05037473624311.425593473
#Sta/Elev= 30
       0 3452.65    51.3    3423     130 3383.27     159 3366.52   285.7 3306.04
     307 3298.64   330.7 3293.19   354.3 3283.61   377.9 3279.71   392.1 3275.12
   440.4 3275.73   468.8 3271.51   519.7 3271.36   523.9 3271.51   538.6 3277.96
   552.9 3288.79   570.3 3292.14   584.8 3290.78   590.6 3292.11   611.3 3307.92
   655.9 3332.65   666.7 3335.96   683.3 3347.07   699.9 3353.01   757.7 3384.89
   771.9 3387.67     794 3398.04   888.1 3424.04   922.3 3436.82   984.7 3465.39
#Mann= 7 ,-1,0
       0      .1       0  327.43     .12       0  337.43      .1       0
   468.8    .045       0   523.9      .1       0  678.99     .12       0
  698.99      .1       0
Bank Sta=468.8,523.9
XS Rating Curve= 0 ,0
Exp/Cntr(USF)=0,0
Exp/Cntr=0.3,0.1

Type RM Length L Ch R = 1 ,230845  ,432.8,459.5,479.4
XS GIS Cut Line= 2
 2307928.5882775624868.6976737722307486.75112812624008.906464167
#Sta/Elev= 30
       0  3462.7    26.7 3456.67    53.4 3446.35    83.1 3425.67   107.4  3411.1
   152.4 3388.34   197.3 3361.58   219.8 3350.65   273.8 3332.33   324.7 3307.53
   354.7 3296.82   377.2 3292.25     401 3280.26   412.9 3277.62   426.7 3270.35
   440.2 3266.97   498.7 3267.02   513.9 3272.07   530.1 3283.99   543.6 3286.22
   557.1 3285.25   575.1 3296.47   620.1 3311.34     683 3336.44     755 3361.29
   777.5 3372.59   858.5 3405.45   889.9 3420.96   934.9 3438.16   966.7 3452.54
#Mann= 4 ,-1,0
       0      .1       0   440.2    .045       0   498.7      .1       0
     880     .12       0
Bank Sta=440.2,498.7
XS Rating Curve= 0 ,0
Exp/Cntr(USF)=0,0
Exp/Cntr=0.3,0.1

Type RM Length L Ch R = 1 ,230386  ,496.8,519.2,532.1
XS GIS Cut Line= 2
2308024.12063413624884.6197332092308247.02946625623965.120800715
#Sta/Elev= 30
       0 3473.88    26.1 3469.17    42.6 3463.19    61.2 3447.45   122.2 3419.98
   143.5 3402.59   164.1 3390.92   246.4 3354.61   283.4 3328.07   328.7 3303.22
   369.9 3293.49   406.9 3278.08   423.4 3276.46   448.1 3268.52   493.2 3265.48
   493.3 3265.47   563.3 3265.63   583.9 3269.61   592.1 3278.91   599.2 3282.93
   616.8 3282.33     624 3284.84   641.5 3298.55     658 3307.49   715.6 3346.37
     732 3361.03   785.6 3389.93   849.1 3417.79   904.9 3436.57   946.1 3458.11
#Mann= 5 ,-1,0
       0      .1       0     480    .025       0   493.2    .045       0
   563.3    .025       0     680      .1       0
Bank Sta=493.2,563.3
XS Rating Curve= 0 ,0
Exp/Cntr(USF)=0,0
Exp/Cntr=0.3,0.1

Type RM Length L Ch R = 1 ,229867  ,263.8,276.5,289
XS GIS Cut Line= 2
2308254.99049596624996.074149269   2308848.08721624339.289197488
#Sta/Elev= 30
       0 3468.62    65.2 3429.23    82.2  3417.1     102 3399.15   164.3 3362.84
   192.6 3338.04     241 3302.79   270.3 3275.33   284.2 3271.18   294.6 3263.27
   305.7 3257.81   311.1 3257.66   371.8 3257.82   402.7 3265.79     422 3273.72
   470.2 3276.75   484.3 3287.29   497.1 3294.27   518.3 3301.85   532.9 3306.46
   586.3 3317.32   612.9  3320.2   628.4 3327.23   652.3 3334.37     718 3372.62
   736.9 3385.58   759.1 3396.98   790.8 3417.35   855.3 3451.32   884.9  3463.8
#Mann= 3 ,-1,0
       0      .1       0   305.7    .045       0   371.8      .1       0
Bank Sta=305.7,371.8
XS Rating Curve= 0 ,0
Exp/Cntr(USF)=0,0
Exp/Cntr=0.3,0.1

Type RM Length L Ch R = 1 ,229590  ,332.8,336.4,340.1
XS GIS Cut Line= 2
2308358.48388231625107.5285653292309138.66479473624697.535534823
#Sta/Elev= 30
       0 3463.24      48 3422.39    87.8  3395.5   127.4    3374   137.5 3365.67
   146.5 3351.82     151 3347.18   202.8 3307.13   254.4 3278.09     273 3271.65
   282.1 3270.52   304.7 3260.04   313.7 3259.07   322.7 3255.62     394 3255.19
  395.963255.549   426.7 3271.37   438.4 3274.44   453.8 3274.35     468  3284.5
     517  3303.2   555.4 3310.74   584.8 3314.08     630 3327.96   666.5 3337.42
   684.3 3344.45   697.8  3354.4   720.4 3366.69   837.9 3439.33   881.3 3460.67
#Mann= 5 ,-1,0
       0      .1       0   322.7    .045       0  395.96      .1       0
     620     .12       0     630      .1       0
Bank Sta=322.7,395.96
XS Rating Curve= 0 ,0
Exp/Cntr(USF)=0,0
Exp/Cntr=0.3,0.1

Type RM Length L Ch R = 1 ,229254  ,367.9,375,385.3
XS GIS Cut Line= 2
 2308485.8603578625374.2230609012309242.15818107625079.664961314
#Sta/Elev= 30
       0 3451.65    32.5 3431.52    48.9 3407.14      52 3404.57   109.8 3371.18
   139.8 3345.63   208.5  3296.1   234.3 3280.58   247.2  3277.4   268.6 3267.93
   281.5 3266.04   302.3 3254.72   324.4 3251.57   380.2 3251.68   414.6 3268.05
   440.3 3270.97   448.9 3269.46   461.8 3279.95   521.9 3296.87   547.7 3310.26
   586.5 3322.44   609.1 3332.79   617.4    3334   694.6 3372.43   715.1 3384.72
   723.7 3392.66   732.2 3393.98   770.9  3412.4   784.2 3420.88   811.6 3432.12
#Mann= 6 ,-1,0
       0      .1       0   324.4    .045       0   380.2      .1       0
     560     .12       0     730      .1       0     770     .12       0
Bank Sta=324.4,380.2
XS Rating Curve= 0 ,0
Exp/Cntr(USF)=0,0
Exp/Cntr=0.3,0.1

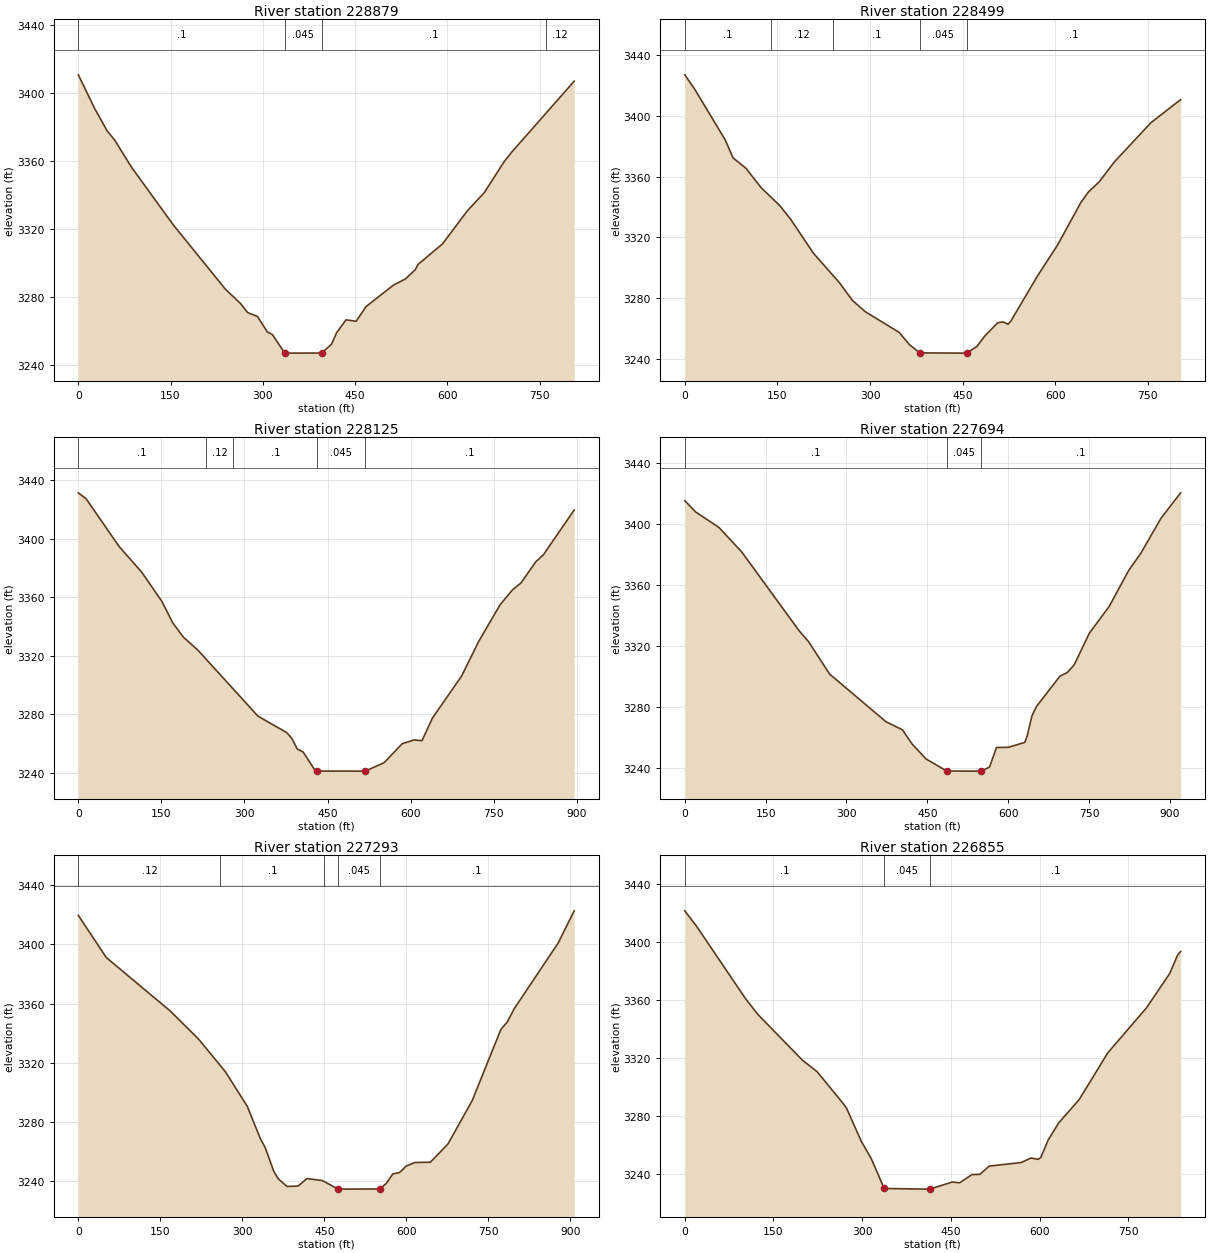
Type RM Length L Ch R = 1 ,228879  ,369.9,379.6,396.8
XS GIS Cut Line= 2
2308545.56808069625636.9370416142309349.63208227625577.229318725
#Sta/Elev= 30
       0 3410.59    26.7 3390.73    46.7 3377.76    58.8 3372.45    86.8 3356.15
     155 3322.21   239.3 3284.66   263.6 3276.37   275.4 3270.96   291.4 3268.67
   307.5 3259.56   315.5  3258.1   335.5 3247.31   339.5 3247.16   395.7 3247.23
   411.7 3252.36   419.8    3259   435.3 3266.71   451.8 3265.88   467.9  3274.5
     512 3286.96   532.1  3290.8   548.1 3296.22   552.1 3299.16   592.2 3311.31
   632.3 3330.59   660.4 3341.53   692.5 3359.62   704.5  3365.1   806.3 3406.84
#Mann= 4 ,-1,0
       0      .1       0   335.5    .045       0   395.7      .1       0
     760     .12       0
Bank Sta=335.5,395.7
XS Rating Curve= 0 ,0
Exp/Cntr(USF)=0,0
Exp/Cntr=0.3,0.1

Type RM Length L Ch R = 1 ,228499  ,362.4,373.7,391.4
XS GIS Cut Line= 2
 2308485.8603578625859.8458737342309250.11921079626106.637795009
#Sta/Elev= 30
       0  3427.2    15.6 3418.01    65.5 3384.32    78.1 3372.51    99.1  3365.6
   123.6 3352.85   153.8 3341.04   171.3 3332.11   208.4 3309.62   250.4 3290.23
   271.4 3278.61     292 3271.18   347.1  3257.5   363.9 3249.36   380.7 3243.95
   456.4  3243.8   473.2 3248.19   485.8 3255.03   506.8  3263.8   515.2  3264.4
   523.7 3262.89   527.9 3264.78   571.6 3294.87   603.7 3314.99   641.3  3342.9
     654 3350.13   670.8  3356.5     696 3369.91   754.8  3395.6   803.1 3410.87
#Mann= 5 ,-1,0
       0      .1       0     140     .12       0     240      .1       0
   380.7    .045       0   456.4      .1       0
Bank Sta=380.7,456.4
XS Rating Curve= 0 ,0
Exp/Cntr(USF)=0,0
Exp/Cntr=0.3,0.1

Type RM Length L Ch R = 1 ,228125  ,408,431.1,444.6
XS GIS Cut Line= 2
2308334.60079315626023.0469829642309035.17140838626580.319063264
#Sta/Elev= 30
       0 3431.22      14 3427.22    73.8 3394.46   114.5 3377.01   150.7 3357.16
   170.7 3342.24   189.8 3332.58   216.1 3323.65   324.3 3278.66   376.1 3267.45
   385.3 3263.57   395.5 3256.11   405.8  3254.2   426.8 3241.95   431.3 3241.12
   517.5 3241.09   517.9  3241.1   552.1 3246.85   584.7 3259.82   606.1 3262.38
   620.5 3261.92   639.5 3277.48     692 3306.05   722.7  3329.6   761.6 3354.83
     784 3364.98   799.4 3369.75   825.9 3384.11   839.6 3388.87   895.2 3419.45
#Mann= 5 ,-1,0
       0      .1       0     230     .12       0     280      .1       0
   431.3    .045       0   517.9      .1       0
Bank Sta=431.3,517.9
XS Rating Curve= 0 ,0
Exp/Cntr(USF)=0,0
Exp/Cntr=0.3,0.1

Type RM Length L Ch R = 1 ,227694  ,386.9,401.5,405.8
XS GIS Cut Line= 2
2308171.39968392626106.6377950092308537.60705097626950.506945177
#Sta/Elev= 30
       0 3415.41    20.2 3407.95    63.3  3397.8   105.9 3381.57   212.3 3329.82
   229.5 3322.84   268.8  3301.4   373.4 3270.11     404 3264.79   421.4 3255.64
   447.5 3245.73     486 3237.75   546.8 3237.69   550.3 3237.72   565.3 3240.36
   578.3 3253.23   600.1 3253.33   630.7 3256.57   635.1 3260.68   644.1 3274.04
   652.5  3280.2   696.1 3300.08   709.2 3302.36   722.2 3307.36   750.6 3328.34
   787.1 3345.75   823.5 3369.51     846 3380.79   883.6 3403.88   919.9 3420.54
#Mann= 3 ,-1,0
       0      .1       0     486    .045       0   550.3      .1       0
Bank Sta=486,550.3
XS Rating Curve= 0 ,0
Exp/Cntr(USF)=0,0
Exp/Cntr=0.3,0.1

Type RM Length L Ch R = 1 ,227293  ,443.3,437.4,431.6
XS GIS Cut Line= 2
2307924.60776264626142.4624287432308040.04269356627042.058786941
#Sta/Elev= 30
       0 3419.51    51.1 3391.07   168.1 3355.02   220.1 3335.99   268.9  3314.1
     309 3290.74   333.4 3268.54   341.6 3263.07   357.6 3246.79   365.7 3241.85
   381.8 3236.65     402  3236.9   418.1 3241.96   446.3 3240.64   474.6 3235.02
   478.6 3234.85   551.2 3234.96   563.3 3238.68   575.4 3245.18   587.5 3246.01
   599.6 3250.35   615.7 3252.82     644 3252.99   676.2 3265.33   720.6 3294.65
     773 3342.56   784.8 3347.68   797.2 3356.45   877.9 3400.93     907 3422.56
#Mann= 5 ,-1,0
       0     .12       0     260      .1       0     450    .025       0
   474.6    .045       0   551.2      .1       0
Bank Sta=474.6,551.2
XS Rating Curve= 0 ,0
Exp/Cntr(USF)=0,0
Exp/Cntr=0.3,0.1

Type RM Length L Ch R = 1 ,226855  ,393.1,381,371.8
XS GIS Cut Line= 3
2307454.90700925626261.8778745212307622.08863334626850.994073695
 2307713.6404751627057.980846378
#Sta/Elev= 30
       0 3421.56    20.1 3410.81   103.2 3360.79     124 3350.01   198.9 3318.69
   223.8 3310.74   269.3 3288.11   273.7 3285.49   298.4 3262.88   315.3 3250.94
   337.3 3230.26   409.3 3229.81   414.9  3229.9   452.5  3234.7     465 3234.16
   485.8 3239.83   499.2 3240.01   514.9 3245.67   568.9 3248.13   585.5 3251.24
     598 3250.34   602.2 3251.65   614.8 3263.77   632.3 3275.36   667.2 3291.57
   715.4 3323.66     781 3354.76   820.3  3378.4   833.5    3391   838.7 3393.54
#Mann= 3 ,-1,0
       0      .1       0   337.3    .045       0   414.9      .1       0
Bank Sta=337.3,414.9
XS Rating Curve= 0 ,0
Exp/Cntr(USF)=0,0
Exp/Cntr=0.3,0.1

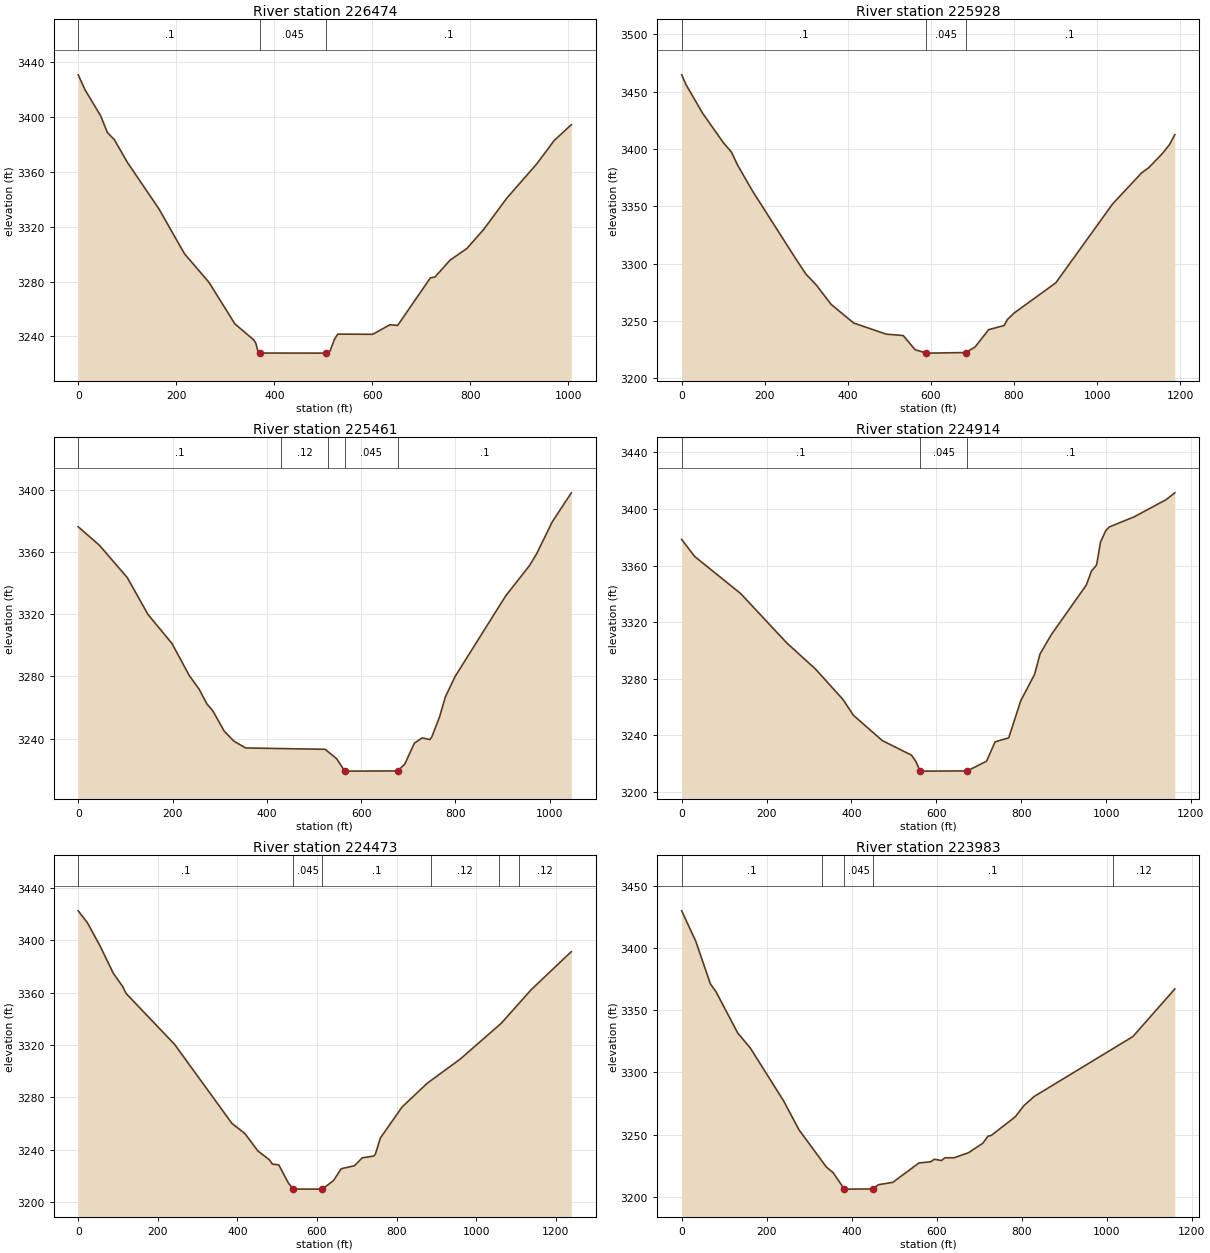
Type RM Length L Ch R = 1 ,226474  ,589.8,546.3,487.6
XS GIS Cut Line= 3
2307001.12831529626409.1569243152307331.51104861626998.273123489
2307614.12760362627169.435262438
#Sta/Elev= 30
       0    3431      14 3420.07    45.9 3400.99    59.6 3388.86    73.4 3383.84
   100.9 3366.76   163.9  3333.6   216.7 3300.43   266.7 3279.55   319.6 3249.18
   357.9 3237.56   362.3 3235.05   366.9 3228.95   371.5  3227.9   505.1 3227.84
   513.5 3229.21   522.8 3238.08   529.6 3241.73   600.8 3241.58   635.9 3248.58
   651.6 3248.05   718.3 3282.76   727.7 3283.42   758.3 3295.65   793.1 3304.33
   827.8 3318.46   874.1 3340.93   935.9 3366.23   970.8 3383.03  1005.8 3394.61
#Mann= 3 ,-1,0
       0      .1       0   371.5    .045       0   505.1      .1       0
Bank Sta=371.5,505.1
XS Rating Curve= 0 ,0
Exp/Cntr(USF)=0,0
Exp/Cntr=0.3,0.1

Type RM Length L Ch R = 1 ,225928  ,467.8,467.1,467.1
XS GIS Cut Line= 4
2306408.03160126626966.4290046142306702.58970084627185.357321875
2307132.48530565627288.8507082162307462.86803897627471.954391743
#Sta/Elev= 30
       0 3464.64    10.6 3455.99      50 3431.37    99.9 3405.71   119.8 3397.26
   134.7 3385.86   170.7 3363.24   272.8 3305.32   299.2 3290.86   324.1 3281.36
   359.4 3264.65   413.9 3248.28   492.1 3238.57   533.2 3237.34     562 3224.95
     587 3222.31   590.3 3222.02   683.2 3222.52     706 3227.29   738.9 3242.49
     776 3246.08   784.2 3251.39   800.6 3257.11   900.4 3283.26  1037.5 3352.24
  1106.9 3379.09  1124.4 3383.76  1156.4 3395.78  1174.1 3403.78  1186.9 3412.48
#Mann= 3 ,-1,0
       0      .1       0     587    .045       0   683.2      .1       0
Bank Sta=587,683.2
XS Rating Curve= 0 ,0
Exp/Cntr(USF)=0,0
Exp/Cntr=0.3,0.1

Type RM Length L Ch R = 1 ,225461  ,558,546.8,543.9
XS GIS Cut Line= 2
2306230.98144007627551.9792904232307247.75473648627796.698204226
#Sta/Elev= 30
       0 3376.19    45.1 3364.25   104.1 3343.53   147.9 3319.89   198.7 3301.26
   235.7 3280.54   256.3 3271.93   272.8 3262.42   285.1 3258.11   309.8 3244.82
   330.4  3238.4   355.1 3234.06   523.7  3233.2   548.4 3227.07   564.9 3219.39
   572.4 3219.18   677.3 3219.32   692.4  3223.6     713 3237.16   729.4 3240.53
   745.9 3239.46     750 3241.21   766.5 3254.13   778.8 3266.94   799.4 3280.02
   906.4 3331.67     957 3351.21   972.2 3358.76  1005.1 3379.17  1045.8 3397.98
#Mann= 5 ,-1,0
       0      .1       0     430     .12       0     530      .1       0
   564.9    .045       0   677.3      .1       0
Bank Sta=564.9,677.3
XS Rating Curve= 0 ,0
Exp/Cntr(USF)=0,0
Exp/Cntr=0.3,0.1

Type RM Length L Ch R = 1 ,224914  ,457.1,441.2,433.2
XS GIS Cut Line= 3
 2306041.8242342628152.6224326812306825.98566148628236.213244726
2307184.31560014628131.226952492
#Sta/Elev= 30
       0 3378.42    30.5 3366.42   139.1 3340.14   247.7 3305.22   315.3 3286.78
   380.5  3265.1   404.6 3254.07     473 3236.12   541.4 3225.88   551.6 3221.56
   561.5 3214.71   569.4 3214.56   672.9 3214.72   718.4 3221.58   738.5 3235.28
   770.7 3238.11   799.1 3264.44   831.5 3282.92   844.4 3297.41   870.5 3310.85
   953.4 3346.16   965.9  3356.2   976.6 3359.92   978.5 3361.62   986.8 3376.41
   999.3 3384.67  1007.6 3387.28    1066 3394.39  1141.1 3406.49    1162 3411.41
#Mann= 3 ,-1,0
       0      .1       0   561.5    .045       0   672.9      .1       0
Bank Sta=561.5,672.9
XS Rating Curve= 0 ,0
Exp/Cntr(USF)=0,0
Exp/Cntr=0.3,0.1

Type RM Length L Ch R = 1 ,224473  ,498.9,490.4,485.3
XS GIS Cut Line= 3
2306101.53195709628741.7386318552306849.86875064628630.284215795
2307243.93972171628351.648175645
#Sta/Elev= 30
       0 3422.46    22.9 3413.46    55.2 3395.53      88 3374.92   111.9 3364.67
     120 3359.51   242.2 3320.58   386.5 3260.17   419.2 3252.42   451.6 3239.19
   479.9 3232.64     488 3229.22   504.1 3228.57   528.4 3214.58   540.5 3210.12
   611.8 3210.07   613.3 3210.08   641.6 3216.58     661 3225.64   694.2 3227.93
   713.8 3233.96   742.7  3235.3   746.8  3236.8   759.4 3249.11   813.9 3272.74
     877 3290.86   960.3 3309.38  1063.1 3336.62  1137.8  3362.1  1239.2 3391.31
#Mann= 6 ,-1,0
       0      .1       0   540.5    .045       0   613.3      .1       0
  886.59     .12       0 1056.59      .1       0 1106.59     .12       0
Bank Sta=540.5,613.3
XS Rating Curve= 0 ,0
Exp/Cntr(USF)=0,0
Exp/Cntr=0.3,0.1

Type RM Length L Ch R = 1 ,223983  ,409.5,403.4,408.7
XS GIS Cut Line= 3
2306435.89520527629259.2055635612307100.64118677629024.355186864
2307554.41988073629060.179820597
#Sta/Elev= 30
       0  3429.7    33.2 3405.26    67.6 3371.03    80.9 3364.63   131.8 3331.66
   161.7 3319.43   240.1 3276.95     276  3253.9   340.4 3224.01   356.6 3219.39
   382.1 3206.54   386.3 3206.27     450  3206.4   462.7 3209.82   496.6  3211.7
   558.4 3227.29   585.7 3228.22   594.3 3230.25   611.2 3229.24   619.7 3231.46
   640.9 3231.45   674.8  3235.5   708.6 3243.15   720.6 3248.76   728.6 3249.43
   784.8 3264.32   804.9 3273.22   828.9 3280.55  1061.7 3328.79  1160.2 3366.95
#Mann= 5 ,-1,0
       0      .1       0     330    .025       0   382.1    .045       0
     450      .1       0 1015.01     .12       0
Bank Sta=382.1,450
XS Rating Curve= 0 ,0
Exp/Cntr(USF)=0,0
Exp/Cntr=0.3,0.1