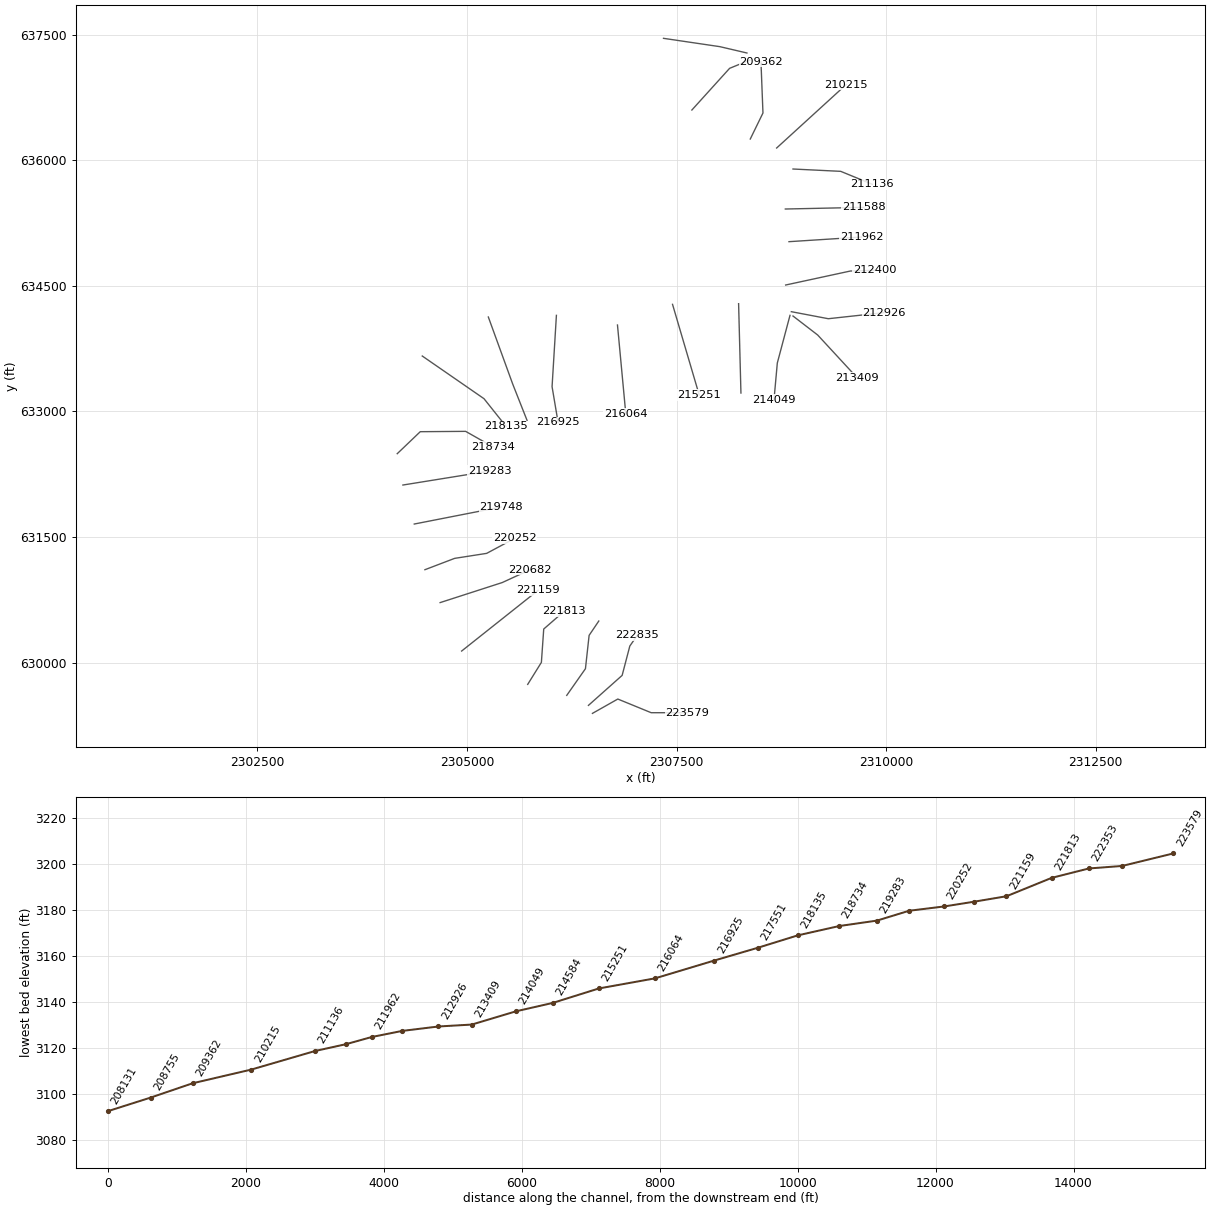
HEC-RAS study SHAVERSFK.prj: SHAVERSFK

--- SHAVERSFK.g01 (geometry) --- (continued)

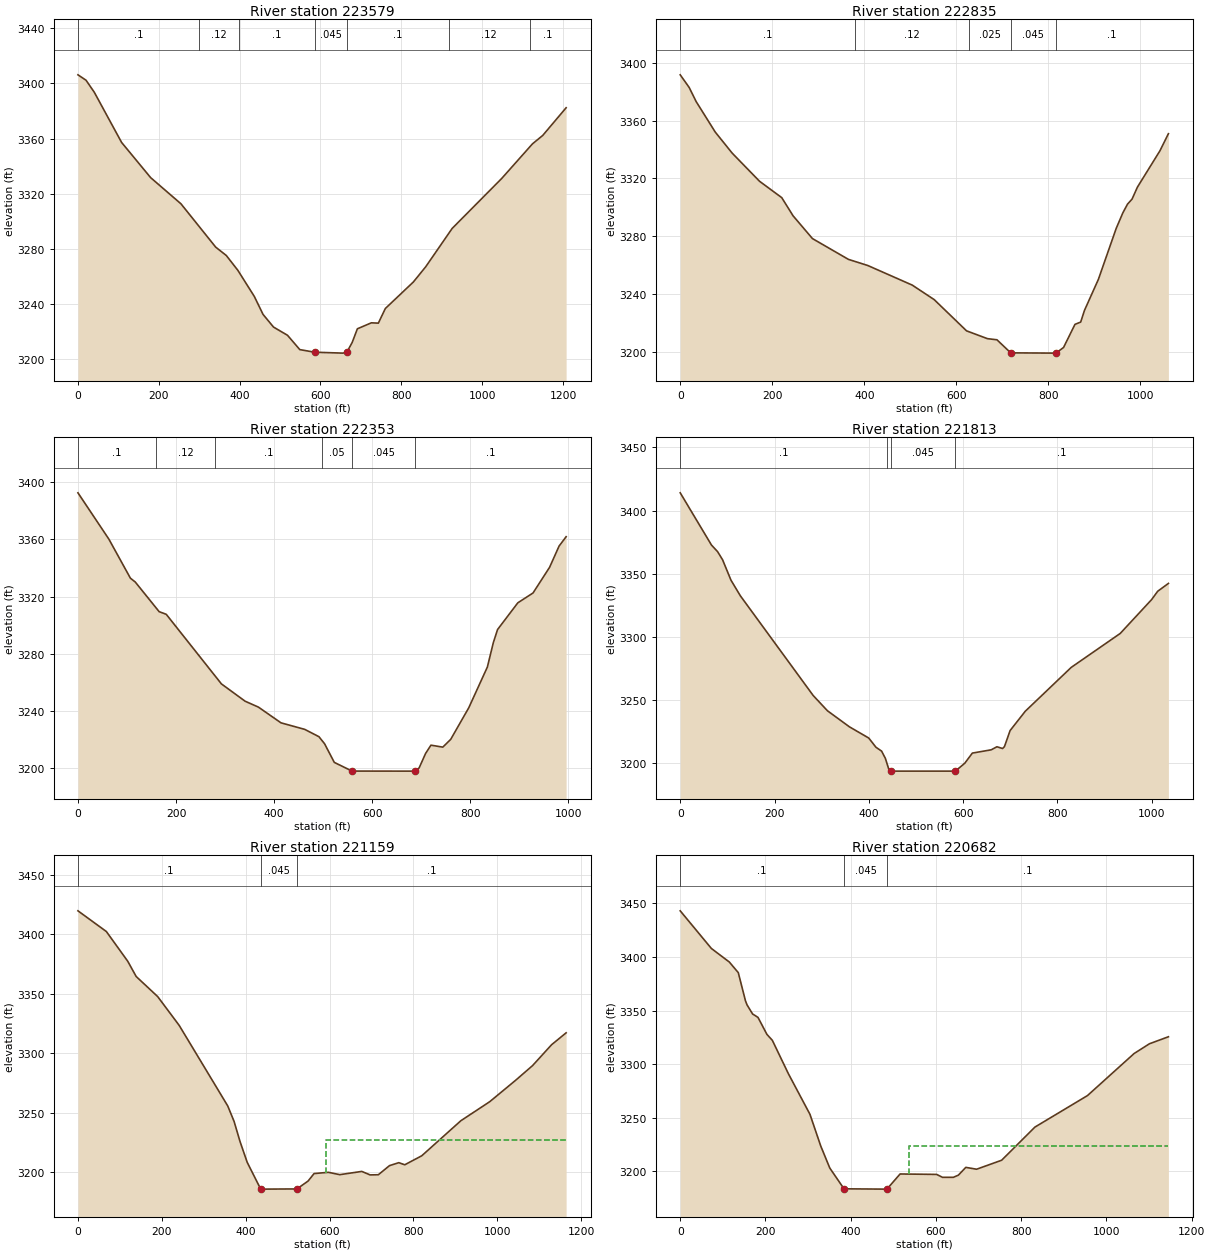
Type RM Length L Ch R = 1 ,223579  ,676.4,744,830
XS GIS Cut Line= 4
2306495.60292816629394.5430687772306798.12205747629565.705207726
 2307196.1735434629402.504098496 2307626.0691482629402.504098496
#Sta/Elev= 30
       0 3406.17      20 3402.26    40.5 3393.52     108 3357.19   179.9 3331.68
   254.8 3312.75   340.8 3281.35   367.1 3275.27   395.6 3264.56   436.3 3245.65
   457.9 3232.62   483.8 3223.45   518.4 3217.51   548.9 3207.11   585.6 3205.23
   656.2 3204.57   665.4 3205.34   665.4 3205.35   678.4 3212.28   691.3  3222.2
   725.9 3226.52   743.2  3226.3   760.4 3236.87   829.8 3256.11   860.5 3267.19
   925.8 3294.91  1048.5 3331.15  1124.5 3356.19  1149.8 3362.25  1207.7 3382.32
#Mann= 7 ,-1,0
       0      .1       0     300     .12       0  397.58      .1       0
   585.6    .045       0   665.4      .1       0  917.79     .12       0
 1117.79      .1       0
Bank Sta=585.6,665.4
XS Rating Curve= 0 ,0
Exp/Cntr(USF)=0,0
Exp/Cntr=0.3,0.1

Type RM Length L Ch R = 1 ,222835  ,471.9,481.9,488.4
XS GIS Cut Line= 4
2306447.83674985  629490.07542542306849.86875064629848.321762735
 2306941.4205924630198.6070703522307032.97243416630329.964060709
#Sta/Elev= 30
       0  3391.6    19.4 3382.88    34.7 3373.05    76.1 3352.01   112.9 3337.44
   172.4 3317.97   220.6 3306.65   245.2 3294.09   287.3 3278.34   365.4 3263.97
   407.6 3259.71   504.1 3246.17   551.8 3236.13   622.1 3214.53   667.5 3209.13
   688.2 3208.34   718.1  3199.3   816.4 3199.12   832.9 3203.04   857.7 3219.03
   870.1  3220.6   878.4 3228.73   908.6 3250.16   947.3 3285.41   961.8  3296.2
   971.9 3302.19   981.7 3305.62   993.4 3313.94  1042.3 3339.07  1060.7 3350.88
#Mann= 5 ,-1,0
       0      .1       0     380     .12       0  628.49    .025       0
   718.1    .045       0   816.4      .1       0
Bank Sta=718.1,816.4
XS Rating Curve= 0 ,0
Exp/Cntr(USF)=0,0
Exp/Cntr=0.3,0.1

Type RM Length L Ch R = 1 ,222353  ,536.4,540,541.6
XS GIS Cut Line= 4
  2306189.103284629609.4908711782306412.01211612629927.932059921
2306455.79777957630325.9835458492306571.23271049630497.145684798
#Sta/Elev= 30
       0 3392.42    63.1 3360.06     107  3332.8   116.9 3330.11   165.6 3309.42
   180.1 3307.56   292.6 3258.96   340.9 3246.87   368.1 3242.73   414.1 3231.76
   462.4 3227.21   491.5 3222.08     503 3217.14   522.8 3204.13     559 3198.06
   687.3 3198.03   695.8 3200.27     709 3210.37   719.9 3216.16   744.1 3214.79
   760.2 3220.21     797 3242.25     835 3270.75   847.1 3287.73   855.7 3296.89
   897.1  3315.6   928.1 3322.46   961.9 3340.42   981.2  3355.2   995.6 3361.76
#Mann= 6 ,-1,0
       0      .1       0     160     .12       0     280      .1       0
  498.71     .05       0     559    .045       0   687.3      .1       0
Bank Sta=559,687.3
XS Rating Curve= 0 ,0
Exp/Cntr(USF)=0,0
Exp/Cntr=0.3,0.1

Type RM Length L Ch R = 1 ,221813  ,691.9,653.9,605.6
XS GIS Cut Line= 4
2305723.38304546629740.8478615352305886.58415469630003.561842247
2305914.44775871630401.6133281762306161.23967998630616.561130577
#Sta/Elev= 30
       0    3414    66.3  3372.7    79.2 3367.52    89.9 3361.04   107.6 3344.96
   127.5  3332.6     282 3253.76   312.3 3241.67     359 3228.95   399.9 3220.11
   415.2 3212.82   427.2 3209.75   435.2 3204.01   443.2 3194.54   446.6 3194.02
   447.2 3193.94   583.6 3193.94   603.6 3200.18   619.7  3208.2   659.8  3210.8
   671.8 3213.21   683.8 3211.82   687.8 3213.33   699.8 3226.03     732  3241.3
   829.4 3275.95   933.4 3302.81    1000 3329.59  1012.9 3336.17  1035.6 3342.36
#Mann= 4 ,-1,0
       0      .1       0  439.28    .025       0   446.6    .045       0
   583.6      .1       0
Bank Sta=446.6,583.6
XS Rating Curve= 0 ,0
Exp/Cntr(USF)=0,0
Exp/Cntr=0.3,0.1

Type RM Length L Ch R = 1 ,221159  ,492.2,477.9,458.8
XS GIS Cut Line= 2
2304935.24110332630138.899347463 2305846.7790061630863.353051852
#Sta/Elev= 30
       0 3419.81    67.8 3402.41   118.7 3377.49   138.9 3364.63   190.2 3347.75
   241.5 3323.54   357.3 3255.87   372.4 3242.88   386.6 3225.95   403.7 3208.51
   435.5 3186.25   440.6 3185.97   522.4 3186.14   548.9 3192.75   563.2 3199.05
   597.3 3200.09   624.5 3198.13     677 3200.85   696.9 3197.92   716.5 3198.05
     743 3205.69   765.2  3208.2   779.5 3206.43   820.1    3214   913.3 3243.44
   982.2 3259.44  1043.5 3277.29  1084.4 3289.78  1129.6 3307.26  1164.4  3317.3
#Mann= 3 ,-1,0
       0      .1       0   435.5    .045       0   522.4      .1       0
#XS Ineff= 2 , 0
                          591.77         3227.07
Permanent Ineff=
       F       F
Bank Sta=435.5,522.4
XS Rating Curve= 0 ,0
Exp/Cntr(USF)=0,0
Exp/Cntr=0.3,0.1

Type RM Length L Ch R = 1 ,220682  ,436,429,422.6
XS GIS Cut Line= 3
2304678.58064495630717.3178065432305420.61481475630957.061502412
2305752.49045396631110.144973128
#Sta/Elev= 30
       0 3442.98    73.1 3407.89   115.2 3395.25   136.2 3385.36     153 3359.18
   156.8 3355.27   169.8 3346.82   182.4 3343.67   203.4  3327.8   216.1 3322.27
   253.9 3291.03   304.3 3253.35   329.6 3223.83   350.8 3203.28   384.2 3183.85
   480.9 3183.56   485.1 3183.64   515.8 3197.68   601.6 3197.28   615.4 3194.55
   640.6 3194.55   652.5 3196.58     670 3203.84   695.3 3202.12   754.1  3210.5
   832.2  3241.4   955.5 3270.78  1064.8 3309.95  1100.9 3319.08  1145.3 3325.58
#Mann= 3 ,-1,0
       0      .1       0   384.2    .045       0   485.1      .1       0
#XS Ineff= 2 , 0
                          537.18         3223.45
Permanent Ineff=
       F       F
Bank Sta=384.2,485.1
XS Rating Curve= 0 ,0
Exp/Cntr(USF)=0,0
Exp/Cntr=0.3,0.1

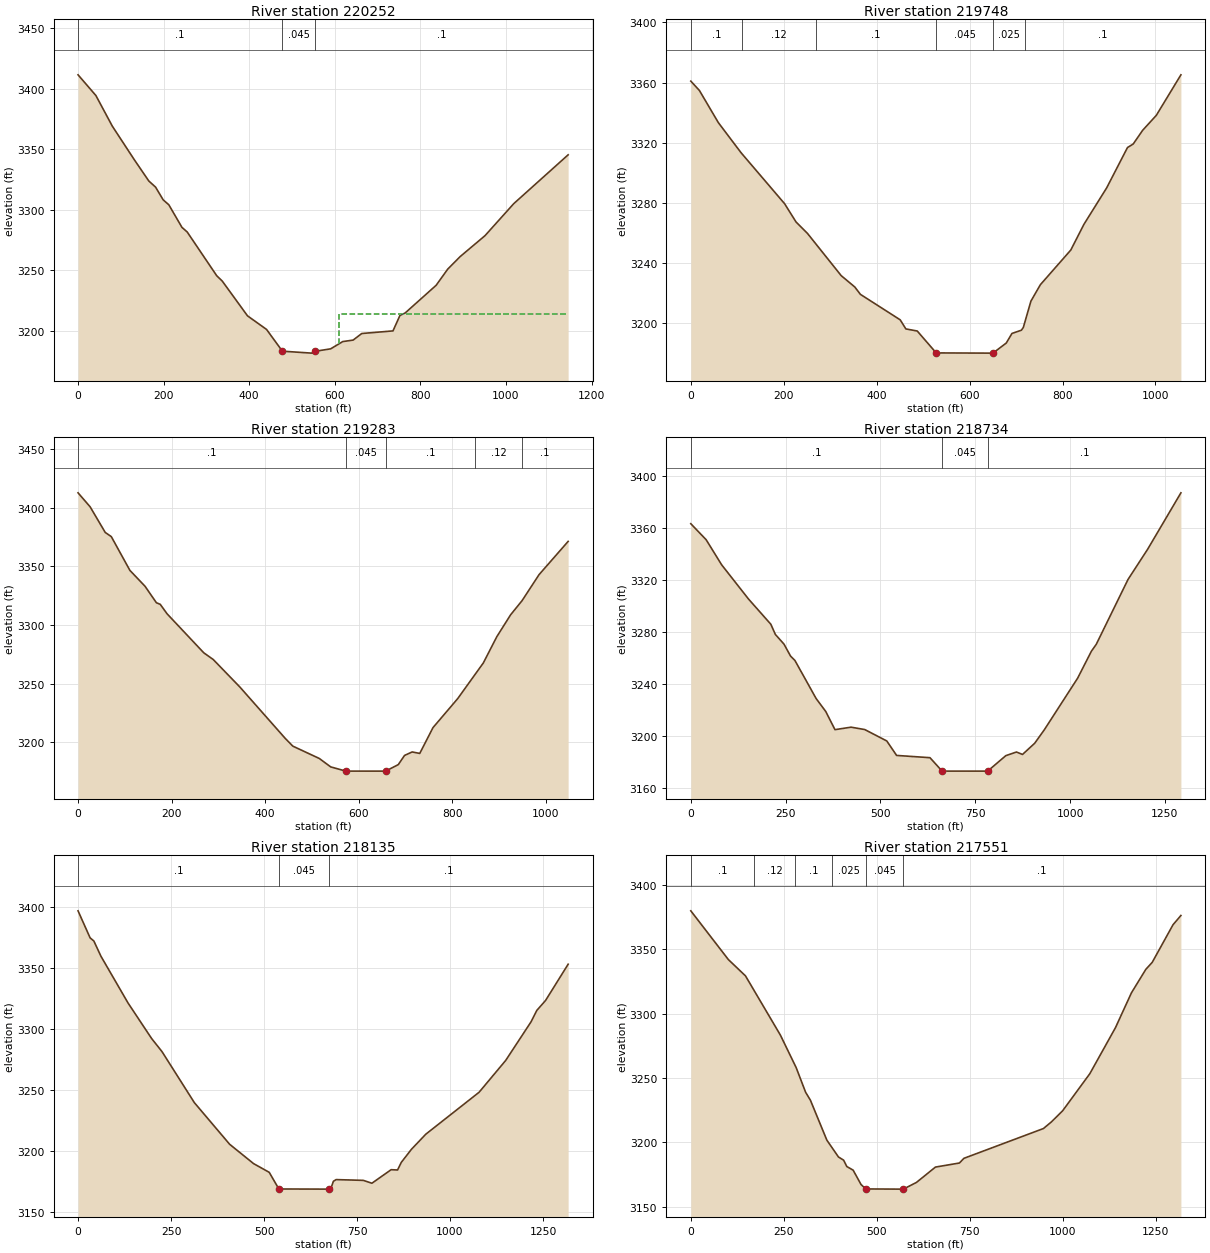
Type RM Length L Ch R = 1 ,220252  ,500.4,504.7,509
XS GIS Cut Line= 4
 2304497.3844688631110.1449731282304851.65029128631245.482478344
2305233.77971777631305.1902012332305568.14296595631484.313369901
#Sta/Elev= 30
       0 3411.54    41.7 3394.45    80.1 3369.11   131.5 3341.36   165.4 3323.78
   181.1 3318.77     199 3308.19   212.1 3304.15   242.8 3285.48   255.1 3281.64
   324.1 3245.48     337 3241.08     396 3212.34   440.5 3201.11   477.5 3183.13
   545.8 3181.52   553.9 3183.03   590.3 3185.06   618.6 3191.07   642.9  3192.3
     663 3197.73     736 3199.89   752.2 3212.65   764.4  3214.7   836.8 3237.58
     864 3250.99     893 3261.32     951  3278.6  1018.3 3305.11  1145.3 3345.43
#Mann= 3 ,-1,0
       0      .1       0   477.5    .045       0   553.9      .1       0
#XS Ineff= 2 , 0
                          610.83         3213.62
Permanent Ineff=
       F       F
Bank Sta=477.5,553.9
XS Rating Curve= 0 ,0
Exp/Cntr(USF)=0,0
Exp/Cntr=0.3,0.1

Type RM Length L Ch R = 1 ,219748  ,465.9,465.2,465
XS GIS Cut Line= 2
 2304370.0079933 631655.475508852305404.94185672631858.481766673
#Sta/Elev= 30
       0 3360.91    18.5  3354.7    59.3 3333.26   108.2  3313.2   201.9 3279.22
   226.4  3267.1   250.9 3259.51   323.6 3231.32   352.8 3223.77     365 3218.83
   450.6 3201.86   462.8  3195.8   487.3 3194.41   528.1 3179.81   646.3 3179.67
   650.3  3179.7   678.9  3186.4   691.1 3192.78   711.5 3194.96   715.6 3196.79
   731.9 3214.31   752.2 3225.24   817.8 3248.39     846  3265.5   894.9 3289.76
   939.7 3316.65     952 3319.01   972.4 3328.16  1001.8 3338.13  1054.7 3365.12
#Mann= 6 ,-1,0
       0      .1       0     110     .12       0     270      .1       0
   528.1    .045       0   650.3    .025       0     720      .1       0
Bank Sta=528.1,650.3
XS Rating Curve= 0 ,0
Exp/Cntr(USF)=0,0
Exp/Cntr=0.3,0.1

Type RM Length L Ch R = 1 ,219283  ,556.1,548.4,539.9
XS GIS Cut Line= 2
2304234.67048809632121.195747386 2305269.6043515632288.377371476
#Sta/Elev= 30
       0 3412.67    25.8 3400.77    58.2 3378.87    71.1 3375.35   110.9 3346.56
   143.3 3333.01   167.6 3318.96   175.8 3317.62   190.3 3309.59   268.9 3276.29
   289.2 3270.54   345.9 3247.21   443.2  3203.3   459.4 3196.71   516.1 3186.18
   540.4 3179.01   572.8 3175.42   657.9  3175.4     685 3180.96   698.4  3188.8
   714.7 3191.75   730.9  3190.5   759.2 3212.49   811.9 3237.14   866.9 3267.65
   895.8 3290.07   925.3 3308.71   949.7 3320.72   986.1 3342.93  1048.3 3371.26
#Mann= 5 ,-1,0
       0      .1       0   572.8    .045       0   657.9      .1       0
     850     .12       0     950      .1       0
Bank Sta=572.8,657.9
XS Rating Curve= 0 ,0
Exp/Cntr(USF)=0,0
Exp/Cntr=0.3,0.1

Type RM Length L Ch R = 1 ,218734  ,638.6,599.1,560.9
XS GIS Cut Line= 4
2304167.00173548632495.3641441582304441.65726077632758.078124871
2304983.00728163 632762.058639732305305.42898524632578.954956203
#Sta/Elev= 30
       0 3363.22    40.4 3350.93    81.3 3331.64   152.1 3305.34     211 3285.94
     223 3278.08   245.7 3270.66     263 3261.46   274.6 3258.06   330.3 3228.88
   355.8 3218.88   380.1 3204.91   422.6 3206.82   458.6 3204.99   516.7 3196.22
   542.6  3185.1   630.6 3183.36   662.6 3173.05   782.6 3173.03   830.6 3184.93
   858.6 3187.72   874.6 3185.85   906.6 3194.44     932 3204.78  1019.8 3244.42
  1056.2  3265.2    1069 3270.49  1152.8 3320.39  1204.6 3343.64  1292.2 3386.96
#Mann= 3 ,-1,0
       0      .1       0   662.6    .045       0   782.6      .1       0
Bank Sta=662.6,782.6
XS Rating Curve= 0 ,0
Exp/Cntr(USF)=0,0
Exp/Cntr=0.3,0.1

Type RM Length L Ch R = 1 ,218135  ,624.3,584.2,549.3
XS GIS Cut Line= 3
2304465.54034993633661.6549979282305201.93559889 633152.14909594
2305464.64957961 632821.76636262
#Sta/Elev= 30
       0 3396.54    32.4 3374.46    42.5 3371.88    61.6 3359.39   134.4 3321.19
   197.7 3292.18   225.8 3281.39   312.7 3239.71   407.6 3205.65   471.9 3189.86
     514 3182.71   539.9 3169.11   674.4 3168.99     675    3169   679.3 3169.16
   686.5  3175.4   693.9 3176.78     767 3176.15     790 3173.81   841.7 3184.88
     859 3184.63     869 3190.85   896.3 3201.56     935 3213.92  1078.1 3248.17
  1149.7 3274.21    1218 3305.85  1233.3 3315.09    1257  3323.3  1317.6 3352.88
#Mann= 3 ,-1,0
       0      .1       0   539.9    .045       0     675      .1       0
Bank Sta=539.9,675
XS Rating Curve= 0 ,0
Exp/Cntr(USF)=0,0
Exp/Cntr=0.3,0.1

Type RM Length L Ch R = 1 ,217551  ,641.1,626,609
XS GIS Cut Line= 3
2305253.68229206634127.3752364642305544.25987679633327.291749749
2305715.42201574632893.415630087
#Sta/Elev= 30
       0 3379.92     101 3342.02     147 3329.35   240.7 3283.38   283.2 3258.08
   308.7 3238.83   321.5 3232.73   365.8 3201.62     397 3188.55   410.9 3186.05
   419.4 3181.14   436.4 3178.32   457.7 3167.14   470.5  3163.7   565.6 3163.56
   571.8 3163.63   606.6 3168.76   657.7  3180.7   722.1 3183.86   734.3 3187.51
   948.1 3210.68   969.6 3215.87   999.7 3224.48  1072.8 3253.33  1141.6 3289.05
  1184.6 3316.16  1223.3 3334.43  1240.5 3339.88  1296.4  3369.1  1317.6  3376.3
#Mann= 6 ,-1,0
       0      .1       0     170     .12       0     280      .1       0
     380    .025       0   470.5    .045       0   571.8      .1       0
Bank Sta=470.5,571.8
XS Rating Curve= 0 ,0
Exp/Cntr(USF)=0,0
Exp/Cntr=0.3,0.1

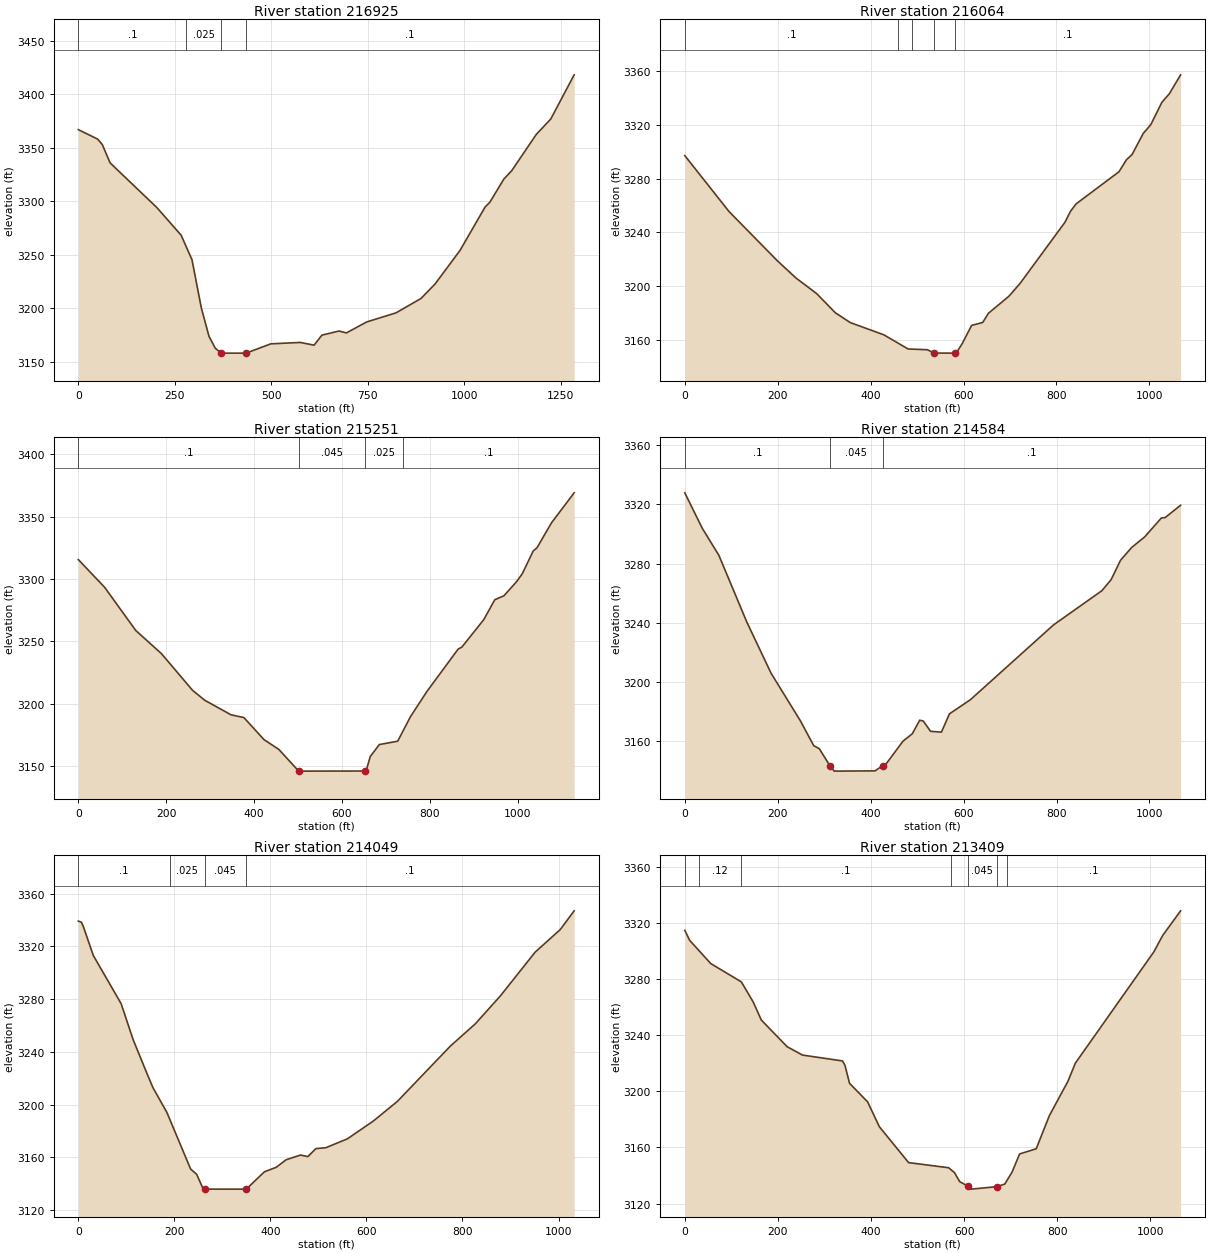
Type RM Length L Ch R = 1 ,216925  ,864.4,860.8,864.1
XS GIS Cut Line= 3
2306065.70732336634147.2778107612306013.96063019633295.447630874
2306085.60989765632869.532540931
#Sta/Elev= 30
       0 3366.92    50.2 3358.07    62.2 3352.95    82.3 3335.88   203.7 3294.07
   266.6 3268.22   294.6  3245.4   318.7 3200.52   338.7 3173.76   355.1 3162.59
   370.8 3158.07   434.9 3158.06     499 3166.74   575.2 3168.04   611.2 3165.51
   631.3 3174.85   675.9 3178.73   694.8 3176.93   747.7 3187.22   823.6 3195.71
   888.2 3209.12   924.7 3222.63   989.6 3254.15  1054.5 3294.64  1066.6 3298.97
  1103.1 3320.76  1123.4 3328.53  1187.1 3362.45  1224.8 3376.92  1285.3 3418.15
#Mann= 4 ,-1,0
       0      .1       0     280    .025       0   370.8    .045       0
   434.9      .1       0
Bank Sta=370.8,434.9
XS Rating Curve= 0 ,0
Exp/Cntr(USF)=0,0
Exp/Cntr=0.3,0.1

Type RM Length L Ch R = 1 ,216064  ,813.9,813.1,815.4
XS GIS Cut Line= 2
2306794.14154261634031.8428798422306893.65441409632969.045412413
#Sta/Elev= 30
       0 3297.14    95.1  3255.6   199.5 3218.89   239.7 3206.04   283.9 3194.55
   323.9 3180.36   356.2 3173.02   428.5 3163.92   480.8 3153.39   522.3 3152.83
     537 3150.34   581.2 3150.31   585.2 3150.81   597.3 3157.43   617.4 3170.89
   641.5 3173.14   653.5 3179.88   697.7 3192.58   721.8 3202.14   818.2 3247.46
   830.3 3255.71   842.3 3261.22   934.7 3285.12   950.8 3294.07   962.9 3297.94
     987 3313.65    1003 3320.02  1027.1 3336.74  1043.2 3343.14  1067.4 3357.17
#Mann= 5 ,-1,0
       0      .1       0     460    .025       0     490      .1       0
     537    .045       0   581.2      .1       0
Bank Sta=537,581.2
XS Rating Curve= 0 ,0
Exp/Cntr(USF)=0,0
Exp/Cntr=0.3,0.1

Type RM Length L Ch R = 1 ,215251  ,680.5,667.6,651.6
XS GIS Cut Line= 2
2307450.92649439634278.6348011172307769.36768313633195.934759392
#Sta/Elev= 30
       0 3315.65    59.9 3293.42   130.8 3258.76   189.1 3240.23   259.9  3210.8
   287.9 3202.76   347.6 3191.11   376.8 3188.93   422.6 3171.22   456.5 3163.32
   501.6 3145.95   501.8 3145.93   651.9 3146.01   656.1 3147.37   664.5 3157.67
   685.2 3167.25     727 3169.96   756.1 3189.68   793.7 3209.95   864.6  3243.9
   872.9 3245.39     923 3267.57     948 3283.47   968.7 3286.59     998 3298.14
  1010.6 3304.34  1035.5 3322.65  1043.9 3325.09  1077.2 3345.27  1128.6 3369.24
#Mann= 4 ,-1,0
       0      .1       0   501.6    .045       0   651.9    .025       0
     740      .1       0
Bank Sta=501.6,651.9
XS Rating Curve= 0 ,0
Exp/Cntr(USF)=0,0
Exp/Cntr=0.3,0.1

Type RM Length L Ch R = 1 ,214584  ,546.9,534.2,517.9
XS GIS Cut Line= 2
2308239.06843653634286.5958308362308266.93204054633219.817848548
#Sta/Elev= 30
       0 3327.87    37.6 3303.91    73.4 3285.58   133.5 3240.45   185.7 3205.87
   249.5  3173.3   277.5 3156.88   289.5 3154.82   312.6 3143.16   321.5 3139.66
   409.6 3139.84   425.6 3143.31   433.6 3144.66   469.6 3159.93   489.6 3164.92
   505.6 3174.09   513.3 3173.53   528.9 3166.59   552.3 3166.04   569.6  3178.4
   614.7 3187.97   793.7 3238.57   897.7  3261.7   917.7 3269.25   937.7 3282.23
   961.7 3290.91   989.8 3298.09  1025.8  3310.9  1033.8 3311.13  1067.1 3319.47
#Mann= 3 ,-1,0
       0      .1       0   312.6    .045       0   425.6      .1       0
Bank Sta=312.6,425.6
XS Rating Curve= 0 ,0
Exp/Cntr(USF)=0,0
Exp/Cntr=0.3,0.1

Type RM Length L Ch R = 1 ,214049  ,605.2,640.2,666.2
XS GIS Cut Line= 3
2308852.06772486634147.277810761 2308700.8081602633578.064185883
2308661.00301161633136.227036503
#Sta/Elev= 30
       0 3339.26     6.3 3338.45    10.4 3335.16    31.1 3313.25    89.1 3276.66
   113.9 3249.58   142.2 3224.34   155.3 3213.03   184.3 3194.28   233.9 3151.21
   246.4 3147.27   258.8 3137.13   262.9    3136   349.8    3136   387.5 3149.14
   411.9 3152.51   432.6 3158.24   462.7 3161.84   478.1 3160.69   494.7 3166.72
   515.4  3167.4   560.3 3174.12     614 3187.53   664.3 3202.48   774.6 3244.41
   826.8 3261.37     879 3282.56   951.4 3315.73  1003.5 3332.78  1032.6 3347.05
#Mann= 4 ,-1,0
       0      .1       0     190    .025       0   262.9    .045       0
   349.8      .1       0
Bank Sta=262.9,349.8
XS Rating Curve= 0 ,0
Exp/Cntr(USF)=0,0
Exp/Cntr=0.3,0.1

Type RM Length L Ch R = 1 ,213409  ,458.1,483,512.6
XS GIS Cut Line= 3
2308887.89235859634139.3167810422309182.45045818633912.427434063
2309652.15121157633402.921532075
#Sta/Elev= 30
       0 3314.62    10.5 3307.47    55.9  3290.9   121.5 3277.88   146.8 3263.63
   164.3 3250.72   219.8  3231.7   252.7 3225.75   338.6 3221.58     344  3218.4
   353.8 3205.62   392.6 3192.43   417.8 3174.72   480.6 3149.15   566.6 3145.49
   579.1 3142.01   590.5 3135.54   607.5 3132.51   615.6 3130.25   669.7    3132
   687.1 3133.84   702.7 3142.28     719  3155.3   754.7 3159.01     783 3182.65
   822.9 3207.12   838.7 3219.98  1007.3 3299.26  1026.4 3311.02  1064.8 3328.51
#Mann= 7 ,-1,0
       0      .1       0      30     .12       0     120      .1       0
  571.81    .025       0   607.5    .045       0   669.7    .025       0
  691.81      .1       0
Bank Sta=607.5,669.7
XS Rating Curve= 0 ,0
Exp/Cntr(USF)=0,0
Exp/Cntr=0.3,0.1

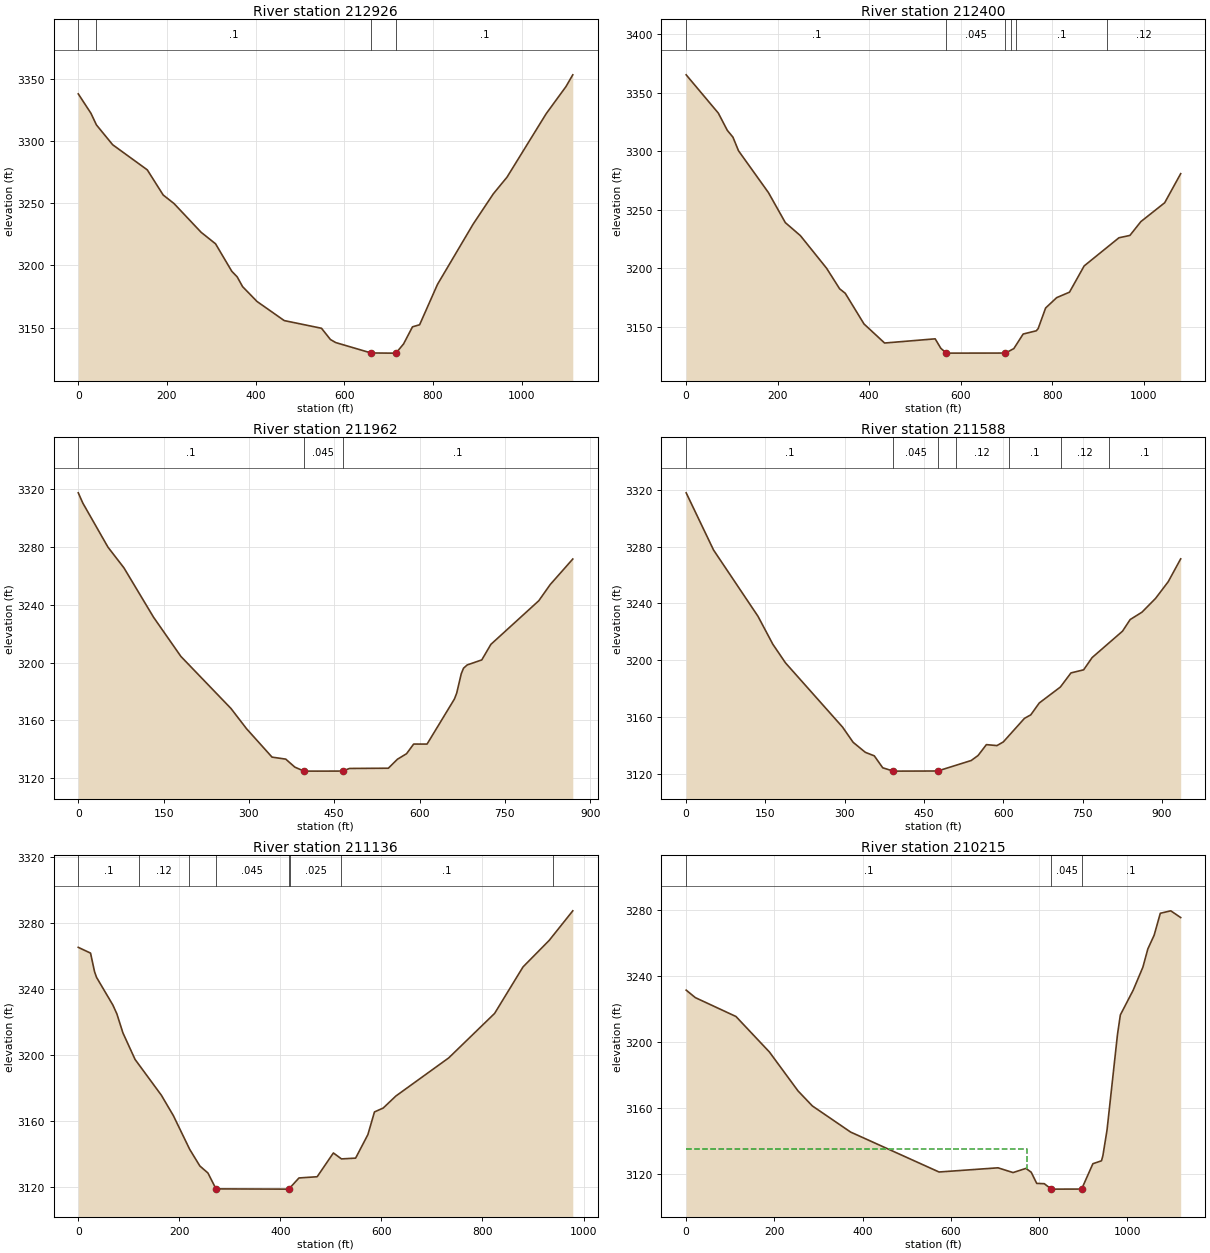
Type RM Length L Ch R = 1 ,212926  ,527.4,526.1,530.3
XS GIS Cut Line= 3
2308867.98978429634191.0634742132309309.11798289634107.075464252
2309971.58710339634179.538233691
#Sta/Elev= 30
       0 3337.83    28.7 3322.15    40.9  3312.9    77.6 3296.93   155.7 3276.74
   191.6 3256.51     216 3249.66   277.1 3226.56   309.7 3217.29   346.3 3195.23
   358.5 3190.73   370.7 3182.85   403.3 3170.92   464.6 3155.58   548.7  3149.4
   568.8 3140.37   580.7 3137.91   660.5 3129.55     704 3129.42   716.7 3129.46
   733.8 3136.81   753.9 3150.55     770 3152.22   810.3 3184.67   890.7  3233.1
   936.1 3257.39   967.2  3270.9  1055.5 3321.88    1100 3343.61  1115.5 3353.13
#Mann= 4 ,-1,0
       0     .12       0      40      .1       0   660.5    .045       0
   716.7      .1       0
Bank Sta=660.5,716.7
XS Rating Curve= 0 ,0
Exp/Cntr(USF)=0,0
Exp/Cntr=0.3,0.1

Type RM Length L Ch R = 1 ,212400  ,440.9,438.4,439.8
XS GIS Cut Line= 3
2308800.32103169634509.5046629552309572.54091439634676.686287045
2309863.11849911634684.647316764
#Sta/Elev= 30
       0 3365.32    70.3 3332.59    89.9 3317.88   102.2 3312.06   114.4 3300.42
   179.9 3264.62   216.8 3238.97   249.5 3227.96   306.8 3200.08   335.4 3182.46
   347.7 3178.62   388.7  3152.4   433.7 3136.12   544.2 3139.71   556.5 3131.63
   568.7 3127.49   697.9 3127.55   716.1 3131.35   736.5 3143.81   765.2 3146.57
   769.3 3148.47   785.6 3166.06   809.8 3174.92   837.8 3179.59   869.8    3202
   945.8 3226.06   969.8 3228.07   993.8 3239.89  1045.8 3255.99  1080.8 3280.85
#Mann= 6 ,-1,0
       0      .1       0   568.7    .045       0   697.9      .1       0
     710    .025       0     720      .1       0  920.11     .12       0
Bank Sta=568.7,697.9
XS Rating Curve= 0 ,0
Exp/Cntr(USF)=0,0
Exp/Cntr=0.3,0.1

Type RM Length L Ch R = 1 ,211962  ,376.1,374,371.8
XS GIS Cut Line= 2
2308840.12618028635026.971594662 2309707.8784196635082.698802692
#Sta/Elev= 30
       0 3317.46     8.1  3310.3    52.2 3279.88    80.2  3265.6   132.3 3231.41
   180.4 3204.27   268.6 3168.18   295.9 3154.21   340.7 3134.56   364.8 3133.17
   380.8 3127.64   396.9 3124.88   420.9 3124.87   464.6 3124.91     477 3126.72
   545.2 3126.88   561.2  3133.1   577.2 3136.92   589.7  3143.6   613.3 3143.59
   661.4 3174.77   665.4 3178.86   673.4 3192.25   677.4  3196.1   683.8 3198.34
   709.5 3201.84   725.5 3212.59   809.7 3242.77   829.8 3253.97   869.5 3271.65
#Mann= 3 ,-1,0
       0      .1       0   396.9    .045       0   464.6      .1       0
Bank Sta=396.9,464.6
XS Rating Curve= 0 ,0
Exp/Cntr(USF)=0,0
Exp/Cntr=0.3,0.1

Type RM Length L Ch R = 1 ,211588  ,457.2,451.7,449.1
XS GIS Cut Line= 2
2308796.34051683635417.0620508722309731.76150876635436.964625168
#Sta/Elev= 30
       0 3317.98    51.8 3277.66   135.9 3230.91   163.9 3211.26   187.9 3198.08
   295.9 3152.78   315.9 3142.06     339    3135   355.9 3132.53   371.9  3124.1
   391.9 3121.75   475.9 3121.84   539.3 3129.24   552.3 3132.78     568 3140.44
     588 3139.76     600 3142.33     640 3158.95     652 3161.44     668 3169.79
     708 3181.05     728 3190.99     752 3193.19     768  3201.8   825.5 3220.42
     840 3228.63   862.3 3233.81     888 3243.51     912  3255.3   935.6 3271.43
#Mann= 7 ,-1,0
       0      .1       0   391.9    .045       0   475.9      .1       0
     510     .12       0     610      .1       0     710     .12       0
     800      .1       0
Bank Sta=391.9,475.9
XS Rating Curve= 0 ,0
Exp/Cntr(USF)=0,0
Exp/Cntr=0.3,0.1

Type RM Length L Ch R = 1 ,211136  ,903.3,921.3,946.2
XS GIS Cut Line= 3
2308887.89235859635894.7238339862309457.10598347635866.860229971
 2309835.2548951635711.620150459
#Sta/Elev= 30
       0 3265.15    24.3 3261.66    32.3 3250.31    36.3 3246.91    68.4 3230.28
    76.4 3224.88    88.4 3213.35   112.4  3197.3   164.5  3175.6   188.2 3163.27
   220.5 3142.87   240.6 3132.79   256.6 3128.54   272.6 3118.91   414.1 3118.76
   416.8 3118.83   436.8 3125.52   472.8 3126.26   504.9 3140.66   520.9 3137.06
   548.9 3137.53   573.2 3151.77   586.2 3165.49   603.5 3167.86   628.7 3175.16
   733.2 3198.22     824 3225.15   880.2 3253.29   932.1 3269.39   978.7 3287.26
#Mann= 8 ,-1,0
       0      .1       0     120     .12       0     220      .1       0
   272.6    .045       0   416.8      .1       0     420    .025       0
     520      .1       0   939.9     .12       0
Bank Sta=272.6,416.8
XS Rating Curve= 0 ,0
Exp/Cntr(USF)=0,0
Exp/Cntr=0.3,0.1

Type RM Length L Ch R = 1 ,210215  ,819.3,853,889.3
XS GIS Cut Line= 2
2308692.84713049636145.4962701212309520.79422122636901.794093384
#Sta/Elev= 30
       0 3231.19    20.8 3226.65   112.9 3215.23   188.7 3193.76   253.7 3170.16
   286.2 3161.07     373 3145.25   573.4 3121.09   707.1 3123.62   741.3 3120.75
   770.5 3123.27   782.4 3120.96   794.9  3114.2   812.1 3114.01     828 3110.73
   831.7 3110.72   896.8 3110.76   922.3  3126.1   941.8 3127.87     945 3131.01
   954.4 3146.54   978.1  3204.4   984.6 3216.18  1013.7 3231.18  1035.6 3245.04
  1046.9 3256.13  1061.2 3264.43  1075.2 3277.72  1098.9  3279.2  1121.4 3275.14
#Mann= 3 ,-1,0
       0      .1       0     828    .045       0   896.8      .1       0
#XS Ineff= 2 , 0
          771.99 3134.76
Permanent Ineff=
       F       F
Bank Sta=828,896.8
XS Rating Curve= 0 ,0
Exp/Cntr(USF)=0,0
Exp/Cntr=0.3,0.1

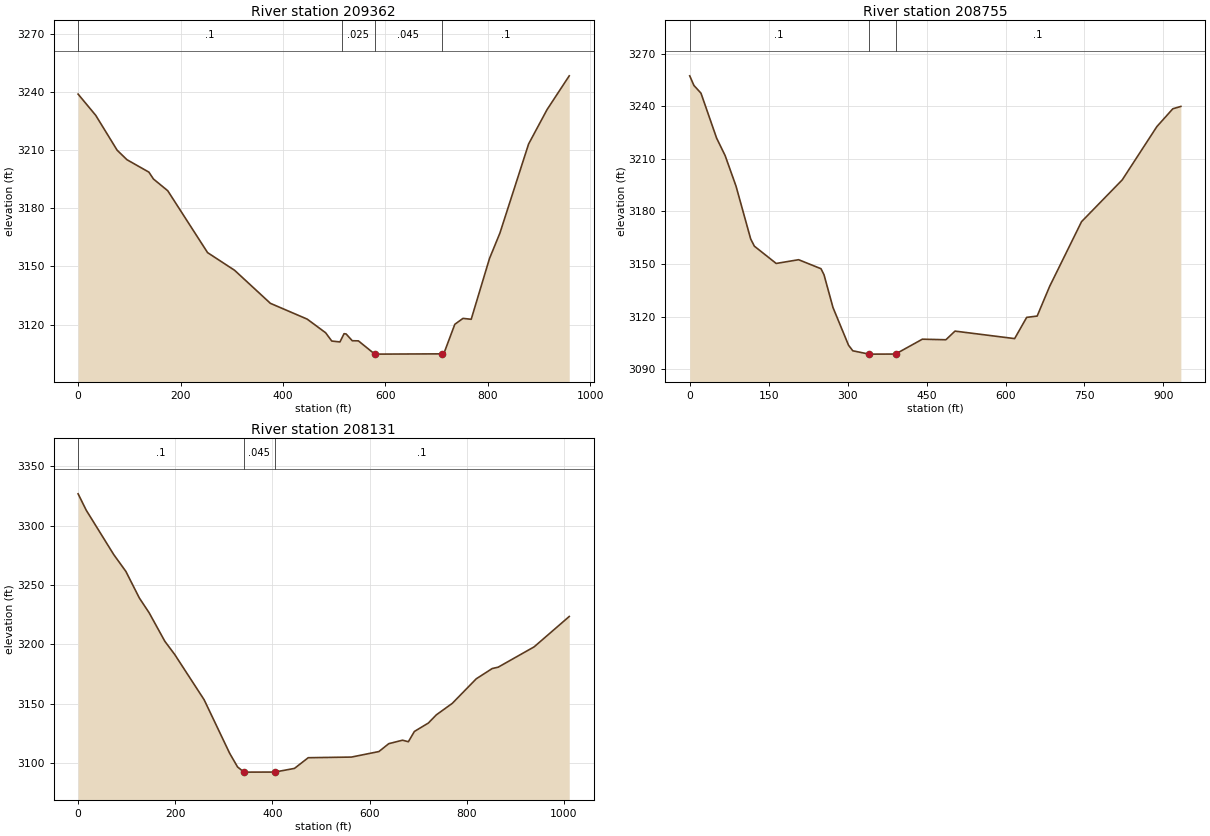
Type RM Length L Ch R = 1 ,209362  ,621.3,607,580.8
XS GIS Cut Line= 3
 2308378.3864566636252.9701713212308529.64602125636563.450330345
 2308505.7629321637176.449618675
#Sta/Elev= 30
       0 3238.87    34.4 3227.93    76.3 3209.91    95.4 3205.03   138.2 3198.62
   147.1 3195.08     175 3189.03   252.8  3157.1   305.5    3148   375.4 3130.95
   447.2 3122.81   483.2 3115.78   495.2  3111.5   511.2 3111.04   519.2 3115.29
   523.2 3115.15   535.2 3111.66   547.2 3111.59   578.9 3104.81   579.3 3104.75
   710.6 3104.89   715.4    3106   735.4 3120.13   751.4 3123.19   767.4 3122.72
   803.1 3154.05   823.5 3167.22   879.5 3213.16   915.5 3230.88   958.8  3248.3
#Mann= 4 ,-1,0
       0      .1       0  515.37    .025       0   578.9    .045       0
   710.6      .1       0
Bank Sta=578.9,710.6
XS Rating Curve= 0 ,0
Exp/Cntr(USF)=0,0
Exp/Cntr=0.3,0.1

Type RM Length L Ch R = 1 ,208755  ,648,623.6,591.3
XS GIS Cut Line= 3
2307681.79635623636599.2749640792308131.59453533637096.839321489
2308374.40594174637196.352192971
#Sta/Elev= 30
       0 3257.29       8  3251.8    21.4 3247.39    51.1 3221.77    67.3 3211.79
      88 3194.36   115.8 3164.27   122.8 3160.14   164.3 3150.27   206.9  3152.4
   249.4 3147.27   255.1 3143.86   272.2 3125.14   301.8 3103.59   309.9 3100.45
     340 3098.59   345.7 3098.55     391 3098.59     442 3107.07   486.7 3106.75
     504 3111.68   617.3  3107.4   640.2 3119.52   660.1 3120.26   683.7 3137.12
   744.4  3174.1   821.7 3197.93   887.5 3228.32   917.8 3238.49   933.1 3239.84
#Mann= 3 ,-1,0
       0      .1       0     340    .045       0     391      .1       0
Bank Sta=340,391
XS Rating Curve= 0 ,0
Exp/Cntr(USF)=0,0
Exp/Cntr=0.3,0.1

Type RM Length L Ch R = 1 ,208131  ,414.3,401.4,389.8
XS GIS Cut Line= 3
2307343.45259319637455.0856588252308016.15960441637355.572787343
2308338.58130801637279.943005016
#Sta/Elev= 30
       0 3326.68    16.9  3312.8    73.5 3275.51    98.3 3261.48   126.1 3239.07
   146.3 3226.62   178.6 3202.66   198.9 3191.57   259.5 3153.49   312.1 3108.43
   328.3 3096.99     341 3092.78   344.4 3092.62   405.1 3092.68   445.5 3095.75
   473.8 3104.74   562.8 3105.28   619.4 3109.94   639.6 3116.54   667.9 3119.47
     680 3118.18   692.4 3126.83   721.1 3133.89   737.6 3140.81   770.4 3150.45
   819.7 3171.09   852.6 3179.74   864.9 3180.89   938.9 3197.97  1011.2 3223.52
#Mann= 3 ,-1,0
       0      .1       0     341    .045       0   405.1      .1       0
Bank Sta=341,405.1
XS Rating Curve= 0 ,0
Exp/Cntr(USF)=0,0
Exp/Cntr=0.3,0.1