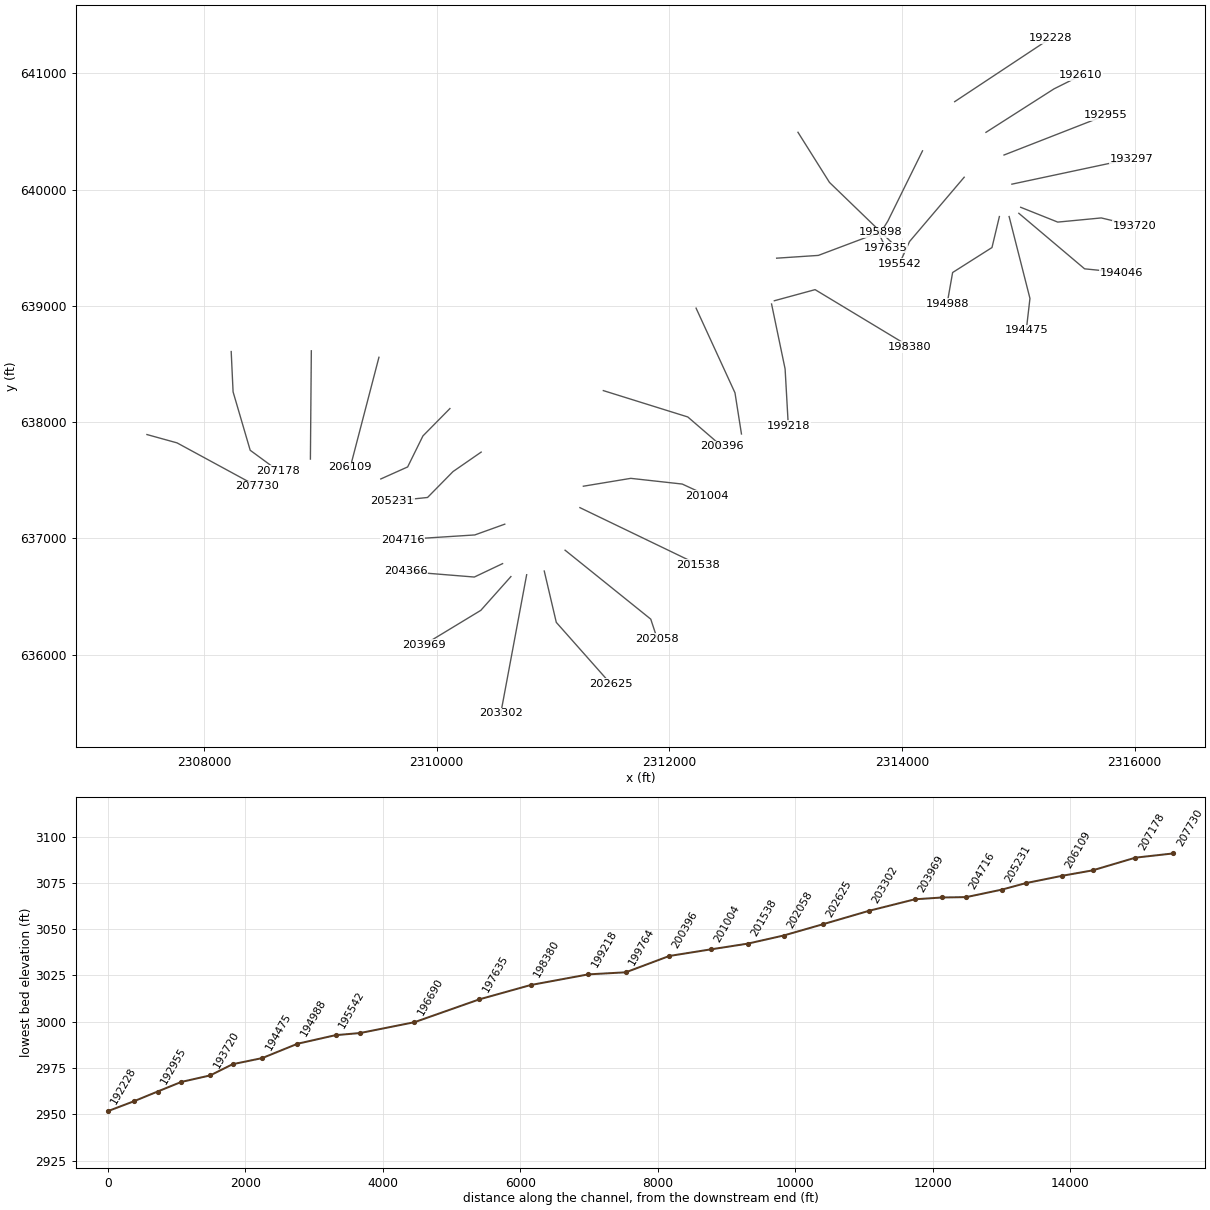
HEC-RAS study SHAVERSFK.prj: SHAVERSFK

--- SHAVERSFK.g01 (geometry) --- (continued)

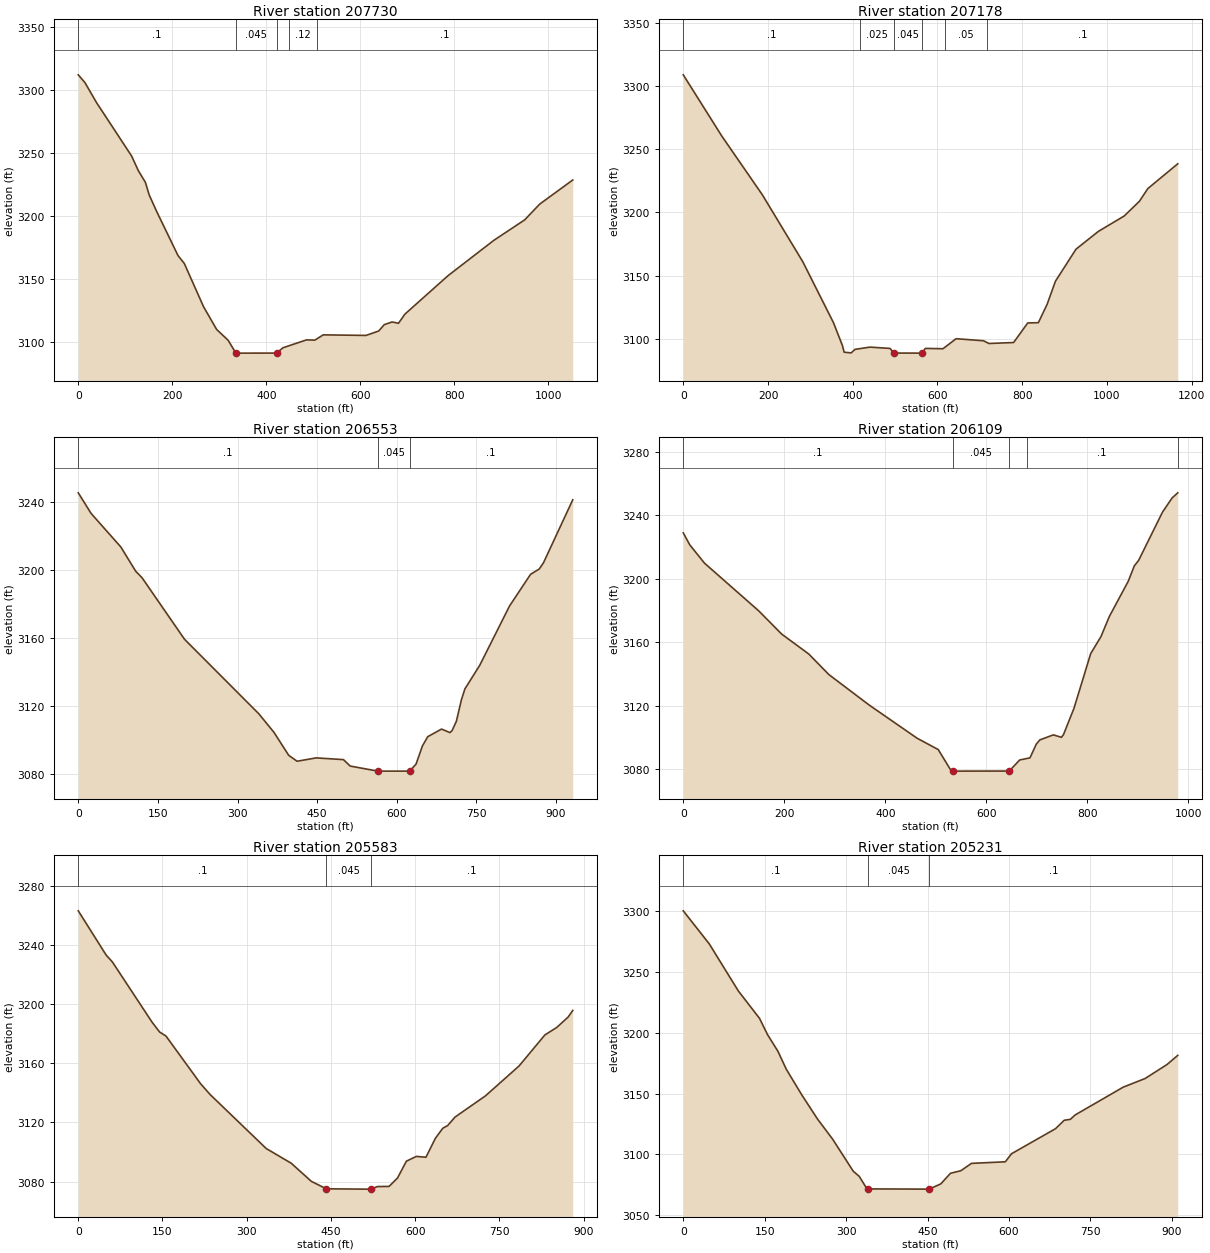
Type RM Length L Ch R = 1 ,207730  ,581.8,552.1,520.7
XS GIS Cut Line= 3
2307510.63421728637892.9422933462307769.36768313637821.293025879
2308457.99675379637447.124629106
#Sta/Elev= 30
       0 3312.31    14.1 3306.19      39 3290.14   113.7 3247.61   127.8 3236.07
   142.7 3226.89     151 3216.68   166.8 3203.61   212.3 3168.48   225.7 3162.18
   266.6 3127.79   294.4 3109.74     319 3101.09   335.4 3090.88   421.9 3090.91
   435.5 3095.13   485.6 3101.41   503.3 3101.21   521.3 3105.42   612.2 3104.96
   639.3 3108.48   651.1 3113.54   667.7 3115.66   681.4 3114.63     695 3121.89
   786.8  3152.5   884.1 3180.57     950 3196.93   981.8 3209.43  1052.2 3228.64
#Mann= 5 ,-1,0
       0      .1       0   335.4    .045       0   421.9      .1       0
  448.47     .12       0  508.47      .1       0
Bank Sta=335.4,421.9
XS Rating Curve= 0 ,0
Exp/Cntr(USF)=0,0
Exp/Cntr=0.3,0.1

Type RM Length L Ch R = 1 ,207178  ,632.9,624.2,612.5
XS GIS Cut Line= 4
2308234.88401989638607.0875660352308251.14562549638260.321990789
 2308398.2890309 637757.604788132308637.11992245637582.462134322
#Sta/Elev= 30
       0 3308.97      91 3260.45   186.7 3213.94   282.3 3160.86   354.6 3112.63
   375.4 3094.82   379.7 3089.32   396.3 3088.78   405.3 3091.57   440.8 3093.35
     488 3092.32497.08283088.659     563 3088.59563.5812 3088.75   571.3 3092.32
     613 3092.08   643.9 3100.01   708.9 3098.37   721.4 3096.22   779.7 3096.99
     813  3112.5   838.1  3112.7   858.9 3127.34   878.4 3145.54     927 3170.93
   979.9 3185.03  1040.8 3197.21  1076.7 3208.88  1096.5  3218.9  1167.1 3238.52
#Mann= 6 ,-1,0
       0      .1       0  417.15    .025       0497.0828    .045       0
563.5812    .025       0  617.15     .05       0  717.15      .1       0
Bank Sta=497.0828,563.5812
XS Rating Curve= 0 ,0
Exp/Cntr(USF)=0,0
Exp/Cntr=0.3,0.1

Type RM Length L Ch R = 1 ,206553  ,454.3,444.3,429.6
XS GIS Cut Line= 2
2308923.71699232638613.4154828762308915.75596261637681.975005804
#Sta/Elev= 30
       0 3245.37    24.2 3233.26    80.2 3213.53   108.2 3199.27   120.2 3195.41
   200.2 3159.24   340.2 3115.41   368.6 3104.55   396.4 3091.04   412.2 3087.53
     448  3089.5   499.5 3088.49   512.3 3084.69   564.3 3081.73   624.3 3081.72
   636.3 3085.85   648.3 3096.52   658.3 3101.97   684.3 3106.45   700.3 3104.36
   704.3  3105.6   712.3 3111.07   721.6  3123.5   728.3 3130.06   756.3 3143.97
   812.3 3178.76     852 3197.45   868.3 3200.56   876.3 3204.19   931.5 3241.27
#Mann= 3 ,-1,0
       0      .1       0   564.3    .045       0   624.3      .1       0
Bank Sta=564.3,624.3
XS Rating Curve= 0 ,0
Exp/Cntr(USF)=0,0
Exp/Cntr=0.3,0.1

Type RM Length L Ch R = 1 ,206109  ,534.2,525.9,510.3
XS GIS Cut Line= 2
2309504.87216178638557.688274846 2309258.0802405637610.325738337
#Sta/Elev= 30
       0 3229.01    12.9 3221.45    41.9 3209.96   149.3 3179.87   194.8  3165.2
   248.5 3152.62   288.4 3139.63   368.4 3120.37   462.9 3099.54   504.8 3092.38
   529.6  3079.4   533.7 3078.78   645.4 3078.83     666  3085.8   686.4 3087.15
   699.1 3095.92     706 3098.47   732.7 3101.64   748.7  3100.1   752.8 3101.83
   773.5 3118.37   806.6 3152.86     827 3163.63   843.7 3176.39     881 3198.51
   892.9 3208.13   901.6 3211.71   948.7 3242.05   967.8 3251.04     979 3254.26
#Mann= 5 ,-1,0
       0      .1       0   533.7    .045       0   645.4    .025       0
     680      .1       0  978.98     .12       0
Bank Sta=533.7,645.4
XS Rating Curve= 0 ,0
Exp/Cntr(USF)=0,0
Exp/Cntr=0.3,0.1

Type RM Length L Ch R = 1 ,205583  ,366.2,352.6,340.8
XS GIS Cut Line= 4
2310114.96923964 638116.514828372309883.02107341637881.000748768
2309751.66408305637614.3062531962309520.79422122637510.812866855
#Sta/Elev= 30
       0 3263.31    49.6  3233.4      61 3228.57   131.6 3187.82     145  3181.2
   156.3  3178.5     218 3146.16   234.9 3138.89   334.8 3102.34   379.4 3092.36
   415.1 3080.12   441.8 3075.05   508.7 3074.84   522.1 3074.85   532.7 3076.58
   553.6 3076.67   568.6 3082.34   584.5 3093.78   602.3    3097   619.3 3096.42
   636.1 3109.25   649.2 3116.03     658 3117.92   671.1 3123.64   725.2 3137.97
   785.1 3158.22   831.1 3179.24   852.3 3184.33   872.8 3191.47   880.8 3195.85
#Mann= 3 ,-1,0
       0      .1       0   441.8    .045       0   522.1      .1       0
Bank Sta=441.8,522.1
XS Rating Curve= 0 ,0
Exp/Cntr(USF)=0,0
Exp/Cntr=0.3,0.1

Type RM Length L Ch R = 1 ,205231  ,551.2,514.3,480.6
XS GIS Cut Line= 4
2310383.57124261637741.9318301022310141.75453926637574.501104603
  2309922.826222637351.592272483 2309620.3070927637319.748153609
#Sta/Elev= 30
       0 3300.51    47.9 3273.28   101.4 3234.55   140.4 3211.98   155.3 3198.48
   174.4 3184.79   189.8 3170.02   218.2 3148.99   247.3 3129.01   275.4 3112.27
   313.1 3086.05     324 3081.89   336.3 3073.03   340.8 3071.48   451.7  3071.3
     453 3071.31   474.4 3075.64   492.2 3084.36   511.1 3086.43   530.9 3092.51
   593.2 3093.81   604.6 3100.44   685.6 3121.06   701.7 3128.02   713.1  3128.8
   721.8 3132.39   810.3 3155.28   850.6 3162.39   890.8 3173.86   910.8 3181.46
#Mann= 3 ,-1,0
       0      .1       0   340.8    .045       0     453      .1       0
Bank Sta=340.8,453
XS Rating Curve= 0 ,0
Exp/Cntr(USF)=0,0
Exp/Cntr=0.3,0.1

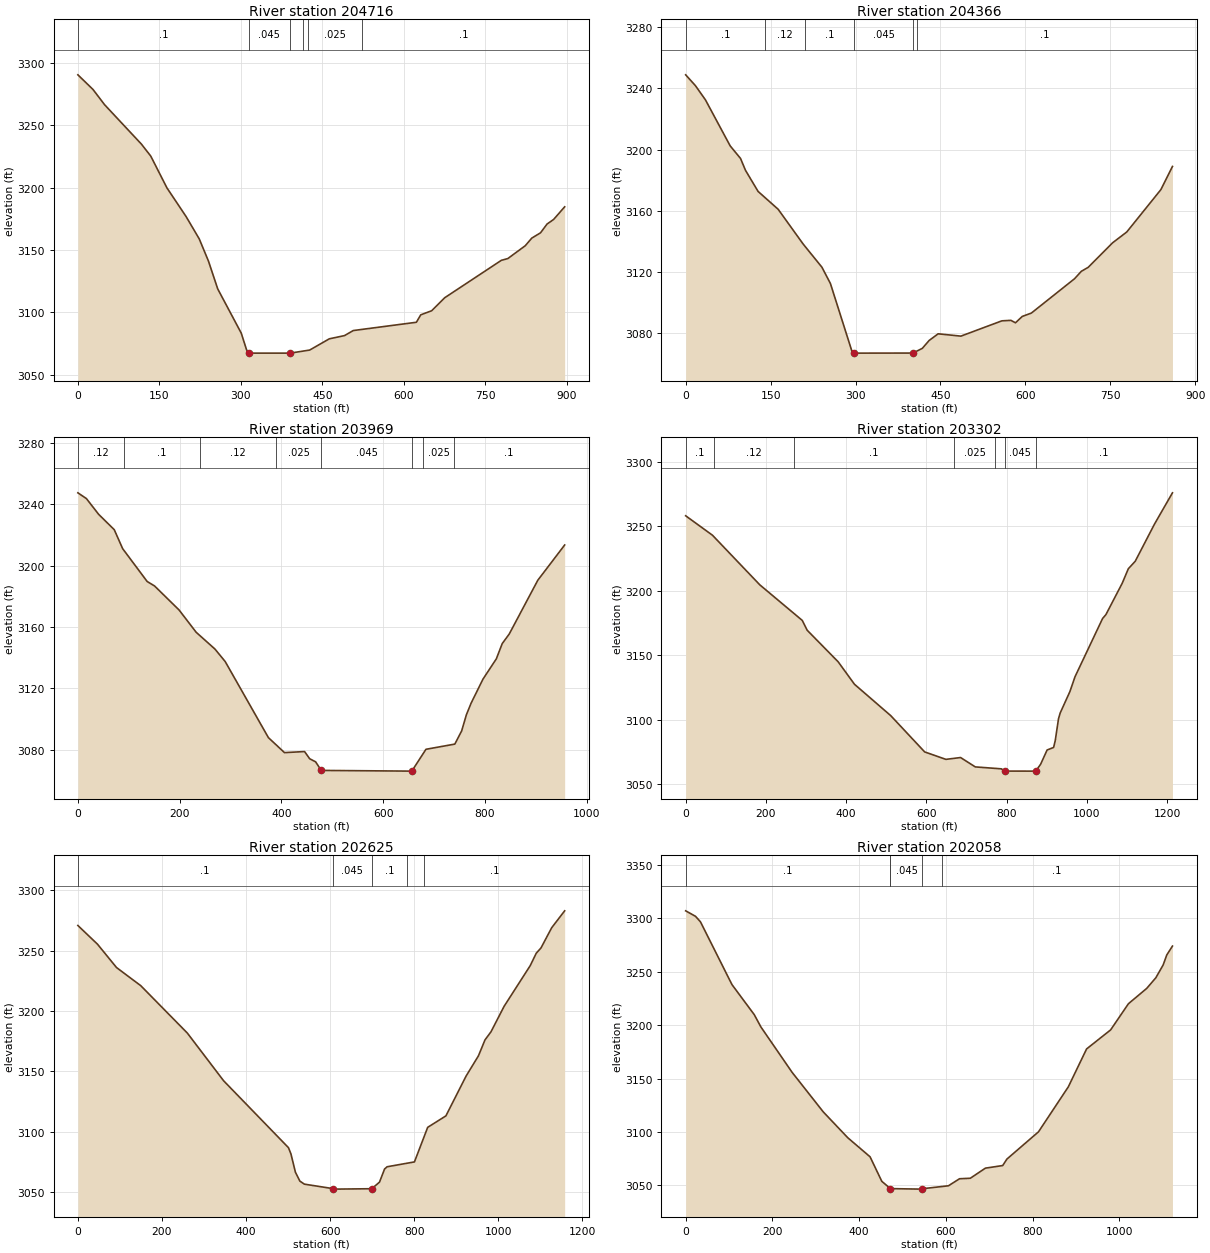
Type RM Length L Ch R = 1 ,204716  ,357.6,350.4,345.1
XS GIS Cut Line= 3
2310586.41200035637121.8007150432310328.83873765637029.170568881
 2309707.8784196636989.365420289
#Sta/Elev= 30
       0 3290.36    27.9 3278.59    49.1 3266.44   117.1 3234.74   134.2 3225.18
   163.9 3199.75   199.2 3176.74   223.4 3158.85   240.4 3141.02   257.4 3118.78
   300.7 3083.32   310.5 3069.92   314.5 3067.28   390.6 3067.28   426.7 3069.74
   462.8 3078.75   490.8 3081.33   506.9 3085.38   623.1 3092.02   631.1 3097.98
   651.2 3101.26   675.2 3111.67   779.4 3141.65   791.4 3143.08   823.5 3153.38
   835.5 3159.47   851.6 3163.74   863.6 3170.75   875.6 3174.39     896 3184.56
#Mann= 6 ,-1,0
       0      .1       0   314.5    .045       0   390.6    .025       0
  413.72      .1       0  423.72    .025       0  523.72      .1       0
Bank Sta=314.5,390.6
XS Rating Curve= 0 ,0
Exp/Cntr(USF)=0,0
Exp/Cntr=0.3,0.1

Type RM Length L Ch R = 1 ,204366  ,335.4,397.3,438.1
XS GIS Cut Line= 3
2310567.66962921636782.3786476062310324.85822279636666.943716687
2309735.74202362636714.709894998
#Sta/Elev= 30
       0 3248.85    17.2 3241.78    34.9 3232.51    78.6 3202.45    96.9 3194.23
   105.7 3186.45   127.9  3172.7   163.3 3161.07   207.6  3138.3   240.7 3123.19
   255.7 3112.54   293.6  3068.4   297.6 3067.09   401.5 3067.13     418  3070.2
   430.1 3075.36     446  3079.7   486.2 3078.19   558.5 3088.17   574.5  3088.5
   582.6  3086.9   594.6 3091.07   610.7 3093.26   686.9 3115.67   698.9 3120.52
     711 3123.11   754.1 3139.13   779.2 3146.22   839.4 3173.86   859.9 3189.02
#Mann= 6 ,-1,0
       0      .1       0     140     .12       0     210      .1       0
   297.6    .045       0   401.5     .12       0  408.85      .1       0
Bank Sta=297.6,401.5
XS Rating Curve= 0 ,0
Exp/Cntr(USF)=0,0
Exp/Cntr=0.3,0.1

Type RM Length L Ch R = 1 ,203969  ,625,666.1,696.8
XS GIS Cut Line= 3
2310639.31889667636670.9242315462310380.58543082636380.346646818
2309894.96261799636085.788547231
#Sta/Elev= 30
       0  3247.6    16.8 3243.84    40.8 3233.59    71.5 3223.57      88 3211.21
   136.2 3189.78   150.8 3186.85     199 3171.18   232.6 3156.64   269.4 3145.74
   289.6 3137.57   374.6 3087.93   406.2 3078.17   445.7 3078.86   455.7 3074.17
   467.4 3072.17   478.4 3066.56   656.2  3066.1   656.7 3066.19   684.3 3080.33
   741.1 3083.73   754.5 3092.34   763.8 3102.85   773.1 3110.43   796.4 3126.09
   822.7 3139.35   834.3  3149.3     848 3155.49   904.2 3190.59     957 3213.57
#Mann= 8 ,-1,0
       0     .12       0      90      .1       0     240     .12       0
  389.07    .025       0   478.4    .045       0   656.7      .1       0
  679.07    .025       0  739.07      .1       0
Bank Sta=478.4,656.7
XS Rating Curve= 0 ,0
Exp/Cntr(USF)=0,0
Exp/Cntr=0.3,0.1

Type RM Length L Ch R = 1 ,203302  ,637.9,677.1,710.8
XS GIS Cut Line= 2
2310774.65640189636686.8462909832310551.99667118635493.937340244
#Sta/Elev= 30
       0 3258.29    66.8 3243.18   184.8 3204.64   290.6 3177.01   302.8  3169.4
   380.1 3144.85   420.8 3127.38   511.1 3103.04   595.8 3074.82   648.7 3069.04
   685.3 3070.46   721.9 3063.19     787 3061.67   795.2 3059.93   872.5  3059.9
   884.7 3065.16     901 3076.31   917.2 3078.31   921.3 3083.62   929.4 3100.55
   933.5 3104.97   957.9 3121.77   970.5 3133.19  1039.3 3178.47  1047.5 3181.46
  1088.1 3205.77  1103.5 3217.15  1120.7 3222.97  1168.9 3251.95  1213.5 3276.13
#Mann= 7 ,-1,0
       0      .1       0      70     .12       0     270      .1       0
     670    .025       0     770      .1       0   795.2    .045       0
   872.5      .1       0
Bank Sta=795.2,872.5
XS Rating Curve= 0 ,0
Exp/Cntr(USF)=0,0
Exp/Cntr=0.3,0.1

Type RM Length L Ch R = 1 ,202625  ,558.4,567.3,575
XS GIS Cut Line= 3
2310925.91596654636718.6904098572311029.40935288636276.853260477
2311496.12429449635749.601392989
#Sta/Elev= 30
       0 3270.72    46.7 3255.23    91.9 3235.93   149.6 3220.91   260.4 3181.69
   346.6 3142.26   500.9 3086.88   506.8 3081.75   517.5 3066.52   528.1 3059.19
   538.8 3056.69   605.7 3053.05   608.8 3052.57   699.1  3052.9   717.5 3058.38
   729.5  3069.2   735.6 3071.07   800.6 3075.09   832.1  3103.7   875.4 3113.17
   923.5 3146.16   952.8 3162.86   968.4 3176.03   982.6 3182.72  1013.8 3203.79
  1076.1 3237.56  1090.3 3247.76  1101.6 3252.14  1127.1 3268.89  1157.9 3282.85
#Mann= 5 ,-1,0
       0      .1       0   605.7    .045       0   699.1      .1       0
   783.8    .025       0   823.8      .1       0
Bank Sta=605.7,699.1
XS Rating Curve= 0 ,0
Exp/Cntr(USF)=0,0
Exp/Cntr=0.3,0.1

Type RM Length L Ch R = 1 ,202058  ,511.1,520.5,525.6
XS GIS Cut Line= 3
2311105.03913521636897.8135785252311841.43438418636304.716864492
 2311896.9124908636136.789638737
#Sta/Elev= 30
       0 3306.83    22.6 3301.72      34  3296.6   106.7 3237.86   158.1 3209.73
   173.5 3198.17   245.4 3155.77   317.3 3118.74   373.8 3094.58   425.2 3076.74
   452.2 3053.84   472.1 3047.01   543.1 3046.53     546 3046.91   605.8 3049.65
   631.4 3056.23   656.3 3056.71   691.1 3066.15     731 3068.59   740.7 3074.65
   813.5 3100.12   882.3 3142.21   924.4 3177.65   979.8 3195.45  1020.9 3219.94
    1063 3234.27  1084.1 3244.24  1100.9 3256.19  1109.3 3265.56  1122.4 3273.85
#Mann= 5 ,-1,0
       0      .1       0     470    .025       0   472.1    .045       0
     546    .025       0     590      .1       0
Bank Sta=472.1,546
XS Rating Curve= 0 ,0
Exp/Cntr(USF)=0,0
Exp/Cntr=0.3,0.1

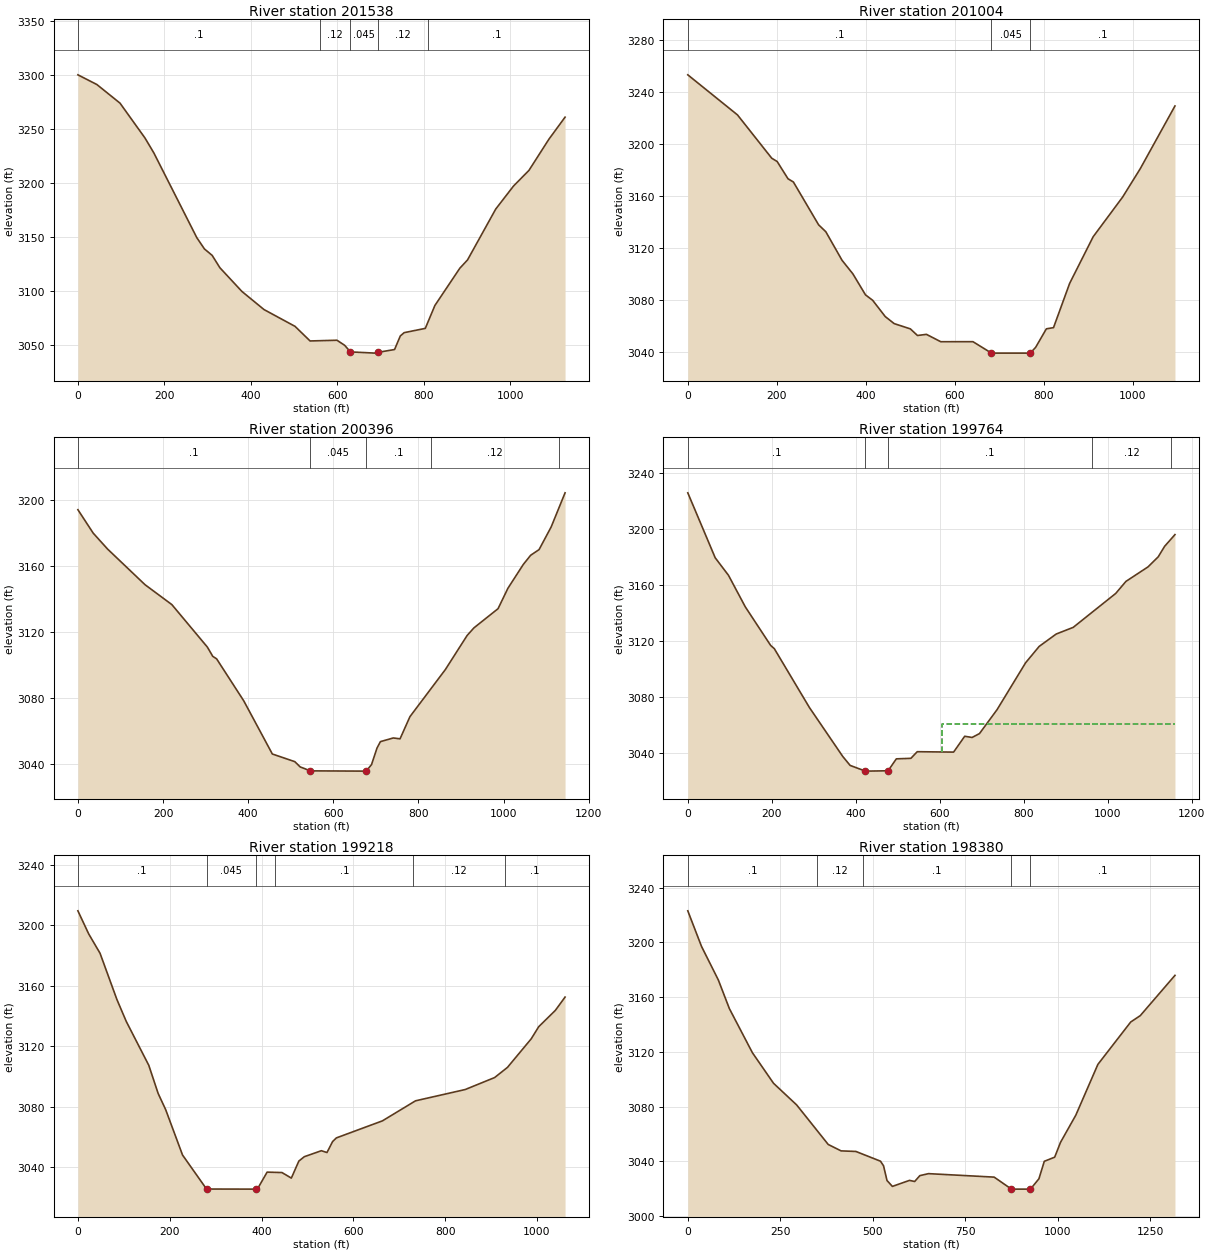
Type RM Length L Ch R = 1 ,201538  ,518.5,533.7,544.2
XS GIS Cut Line= 2
2311232.41561071637264.0209455792312247.44689982636774.417617887
#Sta/Elev= 30
       0 3300.27    43.9 3291.27    97.4 3274.01   155.2 3241.67   175.7 3227.83
   275.1 3149.21   292.8 3138.76   310.6 3132.81   328.5 3121.33   379.4 3099.37
   430.5 3082.56   502.3 3066.98   537.1 3053.44   599.3 3054.12     617 3049.44
   630.4  3043.3   688.1 3042.16     694 3042.88   732.5 3045.49   745.8 3058.08
   754.7 3061.15   803.6 3065.11   825.8 3086.36   883.5 3120.92   901.3  3128.6
   966.6 3175.83  1007.8 3197.19  1043.4 3211.66  1089.5 3240.54  1126.9 3261.01
#Mann= 5 ,-1,0
       0      .1       0     560     .12       0   630.4    .045       0
     694     .12       0     810      .1       0
Bank Sta=630.4,694
XS Rating Curve= 0 ,0
Exp/Cntr(USF)=0,0
Exp/Cntr=0.3,0.1

Type RM Length L Ch R = 1 ,201004  ,624.1,607.4,596.2
XS GIS Cut Line= 4
2311262.02122202637448.450332351 2311669.7526304637516.088641019
2312112.10939461637467.0272034032312327.05719701637367.514331921
#Sta/Elev= 30
       0 3253.15   111.7 3222.32   188.7 3189.01   200.9 3186.48   225.3 3173.19
   237.4 3170.72   294.1 3137.78   310.3 3132.46   346.8 3110.48   371.2 3100.03
   399.5 3083.91   415.7 3079.69   443.9  3067.2     464 3061.79   500.3 3057.75
   516.4 3052.64   536.5 3053.53   568.7 3047.87   641.1 3047.89   682.6 3039.13
   685.4 3039.09   769.9 3039.09     782 3043.54   806.1 3057.77   822.2  3058.7
   858.4  3092.7   911.3  3128.6   977.5  3159.1  1017.1  3180.9  1095.2  3229.2
#Mann= 3 ,-1,0
       0      .1       0   682.6    .045       0   769.9      .1       0
Bank Sta=682.6,769.9
XS Rating Curve= 0 ,0
Exp/Cntr(USF)=0,0
Exp/Cntr=0.3,0.1

Type RM Length L Ch R = 1 ,200396  ,676.3,632.4,601.5
XS GIS Cut Line= 3
2311433.76516512638271.0076036542312159.87557292638044.201857999
2312450.45315765637793.429421864
#Sta/Elev= 30
       0 3194.25      36 3180.01    69.6 3170.39   157.6 3148.73   220.8 3136.61
   304.2 3110.81   316.8 3105.22   325.9 3103.69   389.8 3078.12   456.8  3045.9
   509.6 3041.25   522.2 3038.06   546.2 3035.66   677.1  3035.5   689.8 3039.44
   702.7 3049.51   710.7 3053.41     741 3055.64   756.8  3055.1   780.1 3068.59
   863.3 3097.18   914.3 3117.83   930.4 3122.49   987.1 3134.15  1010.2 3146.52
  1046.4 3161.01  1063.7 3166.59  1083.4 3170.01  1111.9 3183.81  1144.5  3204.5
#Mann= 5 ,-1,0
       0      .1       0   546.2    .045       0   677.1      .1       0
  830.71     .12       0 1130.71      .1       0
Bank Sta=546.2,677.1
XS Rating Curve= 0 ,0
Exp/Cntr(USF)=0,0
Exp/Cntr=0.3,0.1

Type RM Length L Ch R = 1 ,199764  ,552.6,545.6,541
XS GIS Cut Line= 3
2312231.01522901638980.4937015482312565.37847719  638252.0594823
2312621.10568522637897.793659824
#Sta/Elev= 30
       0 3225.79    65.3  3179.3    96.9 3166.79     137 3144.18   197.3 3116.64
   206.1 3114.28   289.7 3072.16     369  3037.2   386.5 3030.79   421.8 3026.83
   424.7 3026.69     477 3026.94   496.6 3035.47   531.3 3035.85   546.4 3040.59
     633  3040.3   659.4 3051.62     677 3050.78   694.6 3053.54   736.6 3070.73
   804.4 3104.19   836.8 3115.93   877.3 3124.77   917.8 3129.54    1019  3153.8
  1043.3 3162.41    1096 3172.82  1120.3 3180.02  1135.4 3187.49  1160.1 3195.89
#Mann= 5 ,-1,0
       0      .1       0   421.8    .045       0     477      .1       0
  961.51     .12       0 1151.51      .1       0
#XS Ineff= 2 , 0
                          604.77         3060.34
Permanent Ineff=
       F       F
Bank Sta=421.8,477
XS Rating Curve= 0 ,0
Exp/Cntr(USF)=0,0
Exp/Cntr=0.3,0.1

Type RM Length L Ch R = 1 ,199218  ,814.8,838.3,854.2
XS GIS Cut Line= 3
2312879.83915108639016.3183352822312996.27240211638457.489769332
2313023.88328768637968.033622722
#Sta/Elev= 30
       0 3209.58    23.6 3194.27    48.2 3181.55    84.9    3151   105.4 3136.41
   154.4 3107.44   174.8 3088.83   191.2 3078.12   227.9 3048.13   280.2 3025.63
   387.3 3025.57   391.4 3025.84   412.1  3036.8   444.5 3036.53   464.9 3032.86
   481.3 3044.14   493.2 3047.01   530.3 3050.97   542.5 3049.77   554.8 3057.03
     563 3059.44   663.3 3070.71   735.4 3083.96   843.6 3091.42   907.7 3099.34
   935.7 3106.08   987.4 3124.96  1003.8 3132.99  1039.9 3143.74  1061.1 3152.55
#Mann= 6 ,-1,0
       0      .1       0   280.2    .045       0   387.3    .025       0
     430      .1       0  730.83     .12       0  930.83      .1       0
Bank Sta=280.2,387.3
XS Rating Curve= 0 ,0
Exp/Cntr(USF)=0,0
Exp/Cntr=0.3,0.1

Type RM Length L Ch R = 1 ,198380  ,711.1,745.4,768.1
XS GIS Cut Line= 3
2312903.72224023639044.1819392972313254.00754785 639139.71429592
2314070.50959426638646.628656187
#Sta/Elev= 30
       0 3223.12      37 3197.18    82.6 3172.59   112.4 3151.69   174.6  3119.5
   231.8 3097.12   294.4 3081.29   379.6 3052.44   414.4 3047.75   454.4 3047.33
   520.9 3040.22   529.2 3036.83   538.5 3026.11     553  3021.8   599.3  3026.2
   613.3 3025.39   627.3 3029.67   650.7 3031.12   828.2 3028.58   874.9 3019.81
   926.3 3019.81   949.2 3027.38   963.7 3040.14   991.8 3043.16  1007.5 3053.97
  1048.9 3073.84  1108.6 3110.95  1197.4 3141.93  1223.2 3146.57  1316.9 3175.97
#Mann= 5 ,-1,0
       0      .1       0     350     .12       0  473.08      .1       0
   874.9    .045       0   926.3      .1       0
Bank Sta=874.9,926.3
XS Rating Curve= 0 ,0
Exp/Cntr(USF)=0,0
Exp/Cntr=0.3,0.1

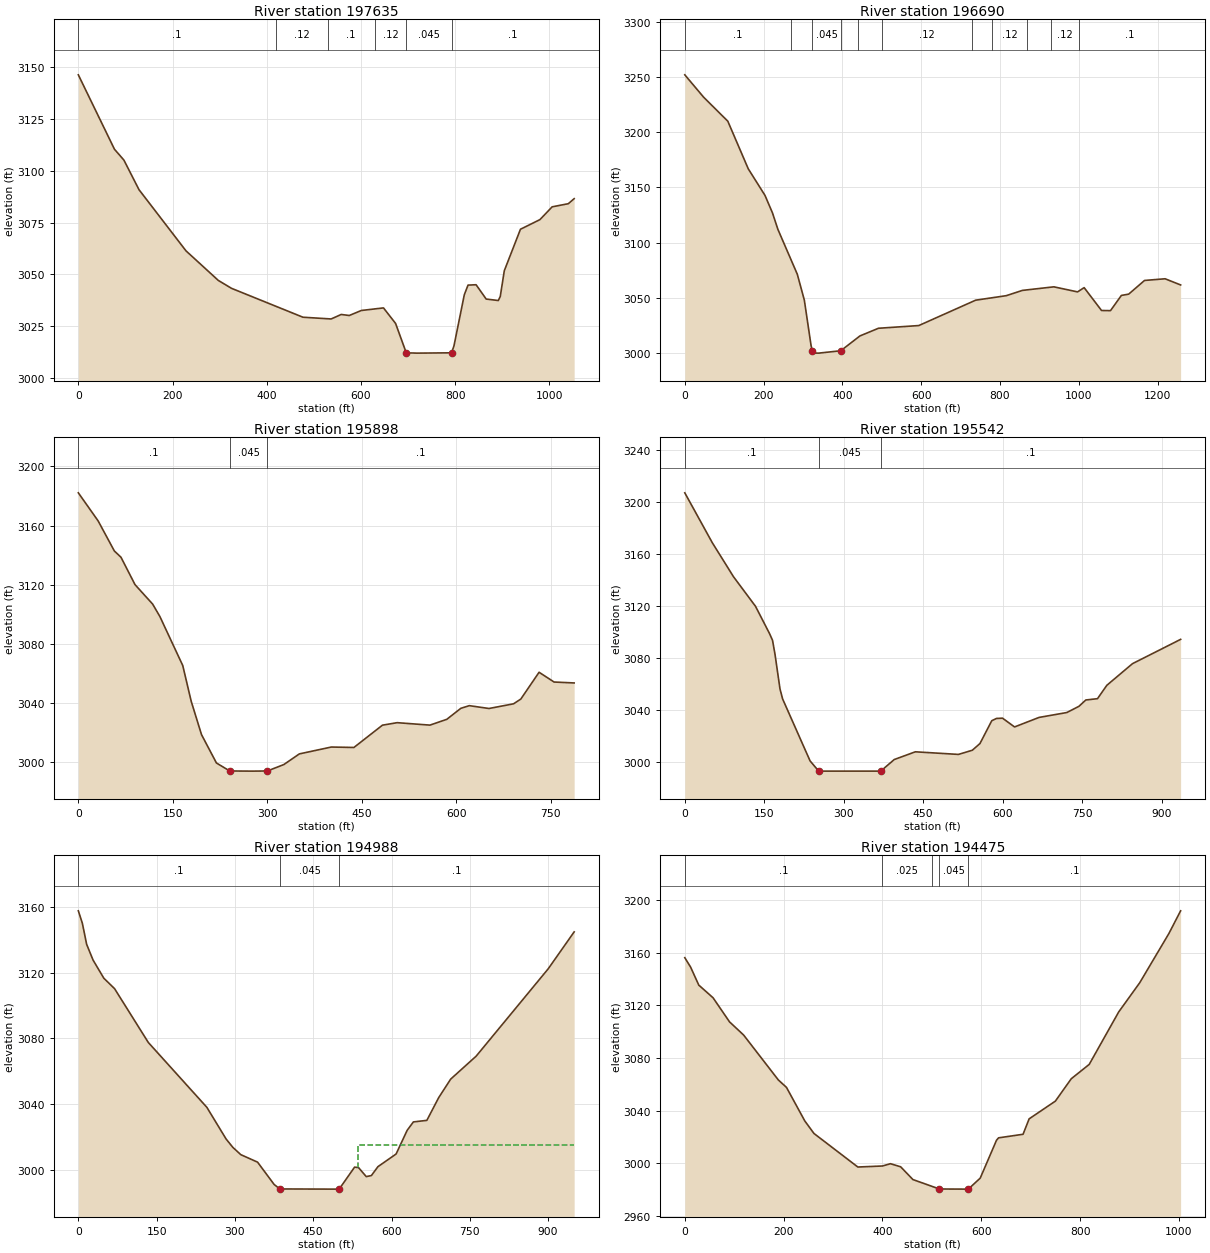
Type RM Length L Ch R = 1 ,197635  ,987.6,944.4,898.7
XS GIS Cut Line= 4
2312923.62481453639410.3893063512313281.87115186639434.272395507
2313799.33808357639629.3176236112313859.04580646639501.941148114
#Sta/Elev= 30
       0 3146.26    76.7 3110.39    96.8 3105.14   128.8 3090.89   228.6  3061.4
   297.2 3047.14   325.3 3043.32   476.9  3029.4   536.8 3028.56   558.1 3030.73
   575.2 3030.23   600.9 3032.65   647.9 3033.89   673.6  3026.4   696.2 3012.25
   718.9 3012.09  792.343012.237   797.5 3015.56   819.5 3040.25   827.4 3044.88
   844.5 3045.06   865.9 3038.16   891.6 3037.45   895.8 3039.38   904.4 3051.82
   938.7 3071.81     980 3076.45    1006 3082.62  1040.3 3084.13  1052.7 3086.55
#Mann= 6 ,-1,0
       0      .1       0  419.04     .12       0  529.04      .1       0
  629.04     .12       0   696.2    .045       0  792.34      .1       0
Bank Sta=696.2,792.34
XS Rating Curve= 0 ,0
Exp/Cntr(USF)=0,0
Exp/Cntr=0.3,0.1

Type RM Length L Ch R = 1 ,196690  ,830.7,791.8,761.6
XS GIS Cut Line= 3
2313106.81571642640493.6263006442313377.82513215  640062.1507835
2313916.27805023639541.527432237
#Sta/Elev= 30
       0 3252.15    47.7  3231.9   109.2 3210.08   161.1  3166.9   203.6 3142.77
   222.5 3126.97   236.3 3112.02   285.6 3071.27   303.4 3047.86   320.5 3006.66
  323.733001.893   326.5 2999.84     340 2999.75   395.9 3001.91   444.5 3015.33
   491.6  3022.3   593.9 3024.75   738.2 3047.76   815.9 3051.85     857 3056.65
   936.8 3059.87   996.9 3055.28  1013.6 3059.14  1057.8 3038.41  1080.5 3038.28
  1108.1 3052.07  1126.7 3053.26  1166.9 3065.66  1219.1 3067.18  1258.5 3061.59
#Mann= 11 ,-1,0
       0      .1       0     270    .025       0  323.73    .045       0
   395.9      .1       0     440    .025       0     500     .12       0
  729.53      .1       0  779.53     .12       0  869.53      .1       0
  929.53     .12       0  999.53      .1       0
Bank Sta=323.73,395.9
XS Rating Curve= 0 ,0
Exp/Cntr(USF)=0,0
Exp/Cntr=0.3,0.1

Type RM Length L Ch R = 1 ,195898  ,364.6,356,348.6
XS GIS Cut Line= 3
 2314177.4869952640333.8687537042313878.94838075639728.830495093
2313819.24065787639633.298138471
#Sta/Elev= 30
       0  3182.1    31.4 3163.14    57.2 3142.78    67.7 3138.55      90 3120.02
     118 3106.86   129.5 3098.45   165.8 3065.32   179.2 3041.18   195.6 3018.57
   219.3 2999.39   240.4 2993.99   276.3 2993.89   300.2 2993.99   326.4 2998.35
   350.9 3005.53   401.7 3010.18   437.6 3009.89   482.9 3024.97   506.3 3026.66
   558.3    3025   585.1 3028.93   607.4 3036.37   620.8 3038.17     652 3036.25
     691  3039.4   702.6 3042.62   731.6 3060.75   755.4 3054.15   787.3 3053.52
#Mann= 3 ,-1,0
       0      .1       0   240.4    .045       0   300.2      .1       0
Bank Sta=240.4,300.2
XS Rating Curve= 0 ,0
Exp/Cntr(USF)=0,0
Exp/Cntr=0.3,0.1

Type RM Length L Ch R = 1 ,195542  ,565,554.4,529.7
XS GIS Cut Line= 3
2314535.73333254640106.9794067252314066.03257914639553.687841285
2313978.46125224639362.623128039
#Sta/Elev= 30
       0  3206.7      52 3168.29      92 3142.17   133.5 3119.46   159.8 3098.62
   165.6 3093.36   170.3 3082.56   179.7 3055.97   184.7 3048.21   236.5 3000.61
   252.7 2992.82   254.2 2992.75   369.9 2992.76   395.4 3001.66   435.2  3007.6
   516.6  3005.6   542.8 3008.81   557.2 3013.96   579.5 3031.51   588.4 3033.25
   599.8 3033.46   622.5 3026.72   668.7 3034.03   721.2  3037.8   743.9 3042.54
   757.1 3047.45   779.1 3048.45   796.7 3058.73   845.2 3075.38     936 3094.04
#Mann= 3 ,-1,0
       0      .1       0   252.7    .045       0   369.9      .1       0
Bank Sta=252.7,369.9
XS Rating Curve= 0 ,0
Exp/Cntr(USF)=0,0
Exp/Cntr=0.3,0.1

Type RM Length L Ch R = 1 ,194988  ,459.2,513.1,567.1
XS GIS Cut Line= 4
2314838.25246184639768.6356436862314774.56422409639501.941148114
2314436.22046105639286.9933457132314388.45428274639016.318335282
#Sta/Elev= 30
       0 3157.81     7.7 3150.26    15.9 3137.42    28.2  3127.8    48.8 3116.74
    69.4 3110.36   134.1 3077.52   246.2    3038   283.1 3018.67     296 3013.57
   311.3 3009.11   343.4 3004.55     375 2990.99     386 2988.21   490.3  2988.1
   499.8 2988.13   529.2 3001.49   536.7 3001.27   551.6 2995.74   561.4 2996.36
     574  3001.8   608.8 3009.53     630 3023.97   641.9 3029.08   667.7 3030.03
   690.5 3043.96   713.4  3055.2   762.2  3069.2   900.3 3122.49   949.9 3144.97
#Mann= 3 ,-1,0
       0      .1       0     386    .045       0   499.8      .1       0
#XS Ineff= 2 , 0
                          536.46         3015.07
Permanent Ineff=
       F       F
Bank Sta=386,499.8
XS Rating Curve= 0 ,0
Exp/Cntr(USF)=0,0
Exp/Cntr=0.3,0.1

Type RM Length L Ch R = 1 ,194475  ,398.1,428.7,458.3
XS GIS Cut Line= 3
2314921.84327389639768.6356436862315100.96644255639064.084513593
2315069.12232368638789.428988303
#Sta/Elev= 30
       0 3156.32    11.8 3149.14    28.3 3135.48    57.2 3125.85    90.6  3107.5
   119.1  3097.5   189.3 3063.38   205.8 3057.72   242.9 3032.19   261.4 3022.69
   350.2 2997.17     400 2997.94   416.3 2999.69   436.9 2997.33   461.7 2987.63
   515.3 2980.46   573.1 2980.36     574 2980.43   597.9 2988.72   630.9 3017.54
     635 3019.35   684.6 3022.06   696.9 3033.78     750 3047.27   782.2 3064.29
   818.5 3075.18   878.2 3115.08   920.7 3137.25   979.6 3174.58  1003.5 3191.95
#Mann= 5 ,-1,0
       0      .1       0     400    .025       0     500      .1       0
   515.3    .045       0     574      .1       0
Bank Sta=515.3,574
XS Rating Curve= 0 ,0
Exp/Cntr(USF)=0,0
Exp/Cntr=0.3,0.1

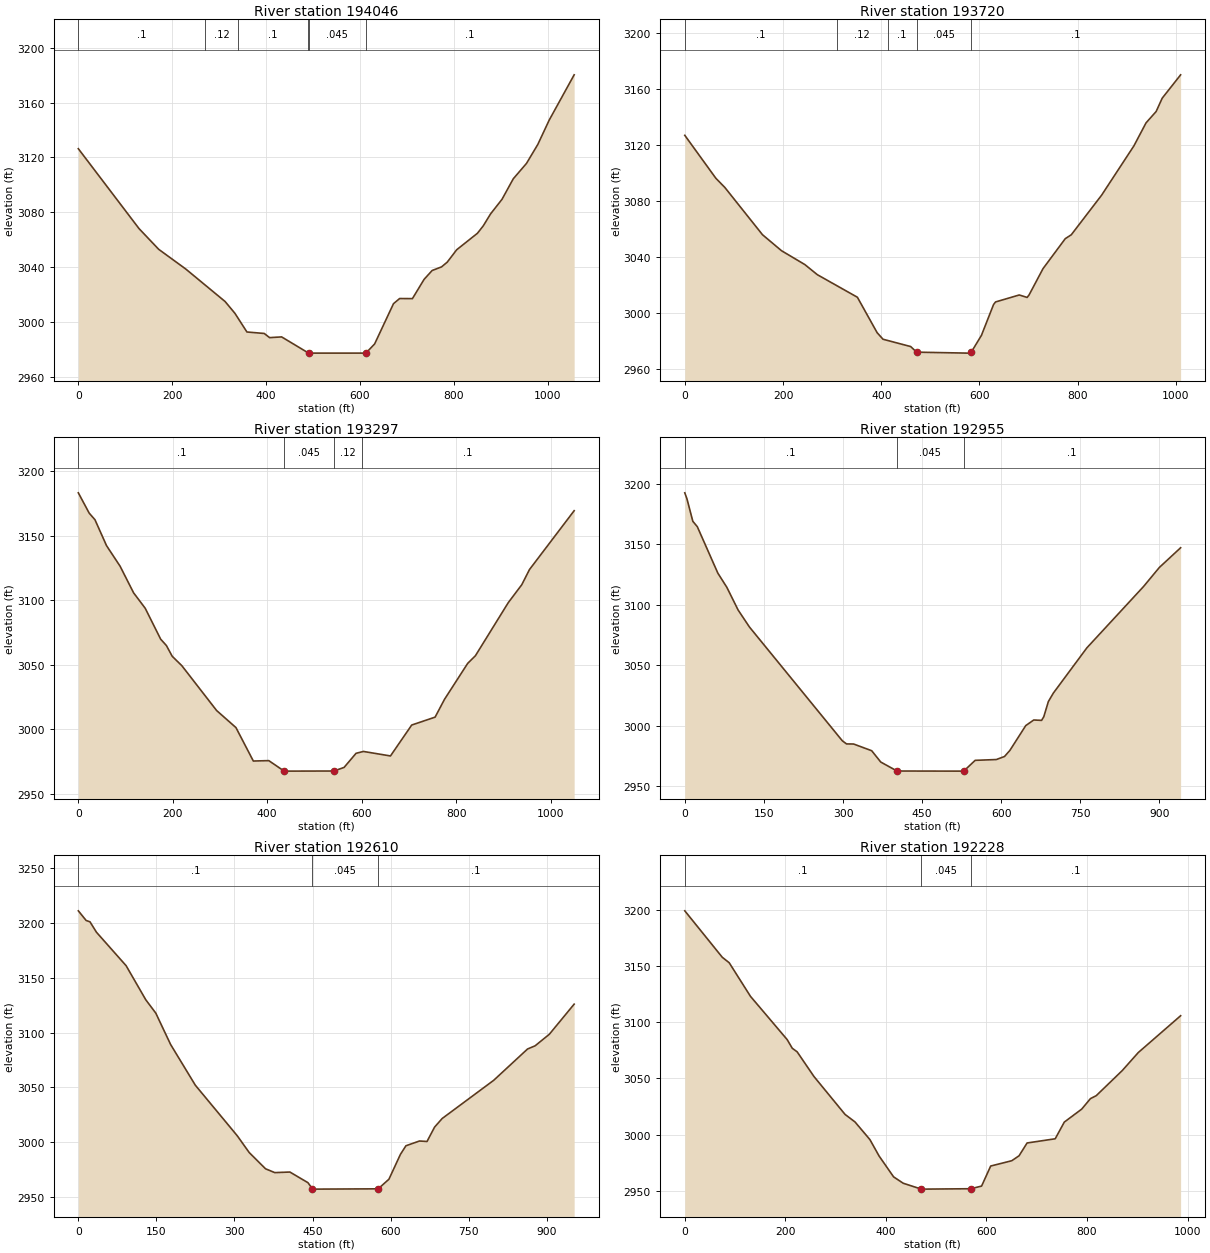
Type RM Length L Ch R = 1 ,194046  ,280.7,326.1,373.2
XS GIS Cut Line= 3
2315005.43408593639796.4992477012315570.66719595639318.837464587
2315885.12786983639286.993345713
#Sta/Elev= 30
       0 3126.39   129.3 3068.03   171.2  3052.9   228.8 3038.52   312.6 3014.78
   333.6 3006.13   359.1 2992.52     396 2991.44   407.4  2988.4     433 2988.93
   490.6 2977.08   612.5 2977.09   631.1 2983.78   671.3  3013.2   684.4 3016.96
   711.6 3016.89   736.6 3031.02   753.6 3037.42   773.7 3040.08   785.8 3043.55
   805.9 3052.58   850.1 3064.63   862.2 3069.89   878.2 3078.83   902.4 3089.41
   926.5 3104.45   954.6 3115.66   978.8 3129.57  1002.9 3147.24  1056.1 3180.35
#Mann= 6 ,-1,0
       0      .1       0     270     .12       0     340      .1       0
     490    .025       0   490.6    .045       0   612.5      .1       0
Bank Sta=490.6,612.5
XS Rating Curve= 0 ,0
Exp/Cntr(USF)=0,0
Exp/Cntr=0.3,0.1

Type RM Length L Ch R = 1 ,193720  ,417.7,422.9,430.7
XS GIS Cut Line= 4
2315021.35614537639848.2459408722315339.79733411639720.869465375
2315713.96573088639756.6940991082315996.58228589639689.025346501
#Sta/Elev= 30
       0 3126.97    63.3  3096.2    81.5 3089.66   158.1 3055.84   196.9 3044.36
   244.3 3034.46   270.1 3027.14   351.4 3011.04   391.6 2985.67   403.6 2980.96
   459.9 2975.74   471.9 2971.73   471.9 2971.72   576.4 2971.03     583 2971.59
     604 2983.77   628.6  3005.8   632.7 3007.67   680.9 3012.66     697 3010.91
     701 3012.73   729.3  3031.5   774.6 3052.97   786.9 3055.78   848.6  3084.1
   914.4 3119.43   939.1  3135.9   959.7 3144.05     972 3153.56  1009.5 3170.29
#Mann= 5 ,-1,0
       0      .1       0     310     .12       0  412.97      .1       0
   471.9    .045       0     583      .1       0
Bank Sta=471.9,583
XS Rating Curve= 0 ,0
Exp/Cntr(USF)=0,0
Exp/Cntr=0.3,0.1

Type RM Length L Ch R = 1 ,193297  ,330.1,342,348
XS GIS Cut Line= 2
2314945.72636304640047.2716838362315972.69919674640266.200001096
#Sta/Elev= 30
       0 3183.42      23 3167.67    35.2 3162.56    59.8 3142.39    88.4 3126.51
     117 3105.85   141.6 3093.87   174.3 3069.91   186.5 3064.93   198.8  3056.6
   219.3 3049.25   292.9 3014.48   333.8 3001.26   370.6 2975.32   403.3 2975.63
     436 2967.48   541.3 2967.57   562.8 2970.36   588.1 2981.29   603.7 2982.75
     661 2979.25     706 3003.25   755.5 3009.36   775.5 3023.23   824.6 3051.11
   840.9 3057.02   910.5 3098.22   939.1 3112.13   955.4 3123.89    1050 3169.54
#Mann= 4 ,-1,0
       0      .1       0     436    .045       0   541.3     .12       0
     600      .1       0
Bank Sta=436,541.3
XS Rating Curve= 0 ,0
Exp/Cntr(USF)=0,0
Exp/Cntr=0.3,0.1

Type RM Length L Ch R = 1 ,192955  ,329.5,345,354.3
XS GIS Cut Line= 2
2314878.05761043640298.0441199712315753.77087948640640.368397869
#Sta/Elev= 30
       0 3192.31     4.1 3187.34    15.2  3168.8    23.7 3164.36    62.7 3125.91
    79.6 3114.33   101.1 3095.48   122.5 3081.47   298.6 2987.45   306.7 2984.81
   320.1 2984.74   354.4 2979.19   371.6 2969.83   402.4 2962.42   521.9 2962.33
     529 2962.39   550.6 2971.24   590.7  2971.9   606.2 2974.41   616.4 2979.43
   646.5 2999.94   661.7 3004.58   676.6 3004.27   680.8 3007.36   689.4 3019.82
   698.8 3026.78   762.4 3064.19   869.8 3114.83   899.9 3130.65   940.2 3146.92
#Mann= 3 ,-1,0
       0      .1       0   402.4    .045       0     529      .1       0
Bank Sta=402.4,529
XS Rating Curve= 0 ,0
Exp/Cntr(USF)=0,0
Exp/Cntr=0.3,0.1

Type RM Length L Ch R = 1 ,192610  ,380.5,382.7,387.5
XS GIS Cut Line= 3
2314722.81753092640493.0893480752315307.95321524640867.257744848
2315538.82307708640982.692675767
#Sta/Elev= 30
       0 3211.24      15 3202.43    22.4  3201.2    34.8 3191.71    91.8 3161.14
   129.8 3129.85   148.8 3117.86   177.3 3089.19   224.8 3051.99   305.5 3005.73
   328.3  2990.5   359.7 2975.65   377.5 2972.15   406.5 2972.68   441.2 2962.96
   449.9 2957.25   452.7 2957.07   576.1 2957.34   596.8  2966.1   618.8 2988.72
   629.5 2996.68   655.5 3001.01     670 3000.59   684.5 3013.69   699.1 3021.56
   798.1 3056.45   863.1 3085.03   877.7 3087.97     905  3098.5   952.7 3126.01
#Mann= 3 ,-1,0
       0      .1       0   449.9    .045       0   576.1      .1       0
Bank Sta=449.9,576.1
XS Rating Curve= 0 ,0
Exp/Cntr(USF)=0,0
Exp/Cntr=0.3,0.1

Type RM Length L Ch R = 1 ,192228  ,298.4,288.6,282
XS GIS Cut Line= 2
2314453.97355733640757.0372883942315276.14890151641301.929967481
#Sta/Elev= 30
       0 3198.87    74.6 3157.59    88.3 3152.78   130.6 3122.94   203.7 3084.46
   213.8 3076.78   223.4 3073.68     257 3051.68   318.8 3018.04   338.6 3011.35
   368.2  2995.7   386.5  2981.1   415.3  2962.6   434.5  2956.9   469.2 2951.89
   472.9 2951.68   568.9 2952.03   590.4 2954.39   608.5  2972.2   650.5 2976.92
   664.9 2981.29   680.9 2992.67   736.8 2996.39   754.9 3011.21   789.6 3022.78
   806.9 3032.06   818.4 3034.67   870.4 3057.08   902.1 3072.99   986.3 3105.68
#Mann= 3 ,-1,0
       0      .1       0   469.2    .045       0   568.9      .1       0
Bank Sta=469.2,568.9
XS Rating Curve= 0 ,0
Exp/Cntr(USF)=0,0
Exp/Cntr=0.3,0.1