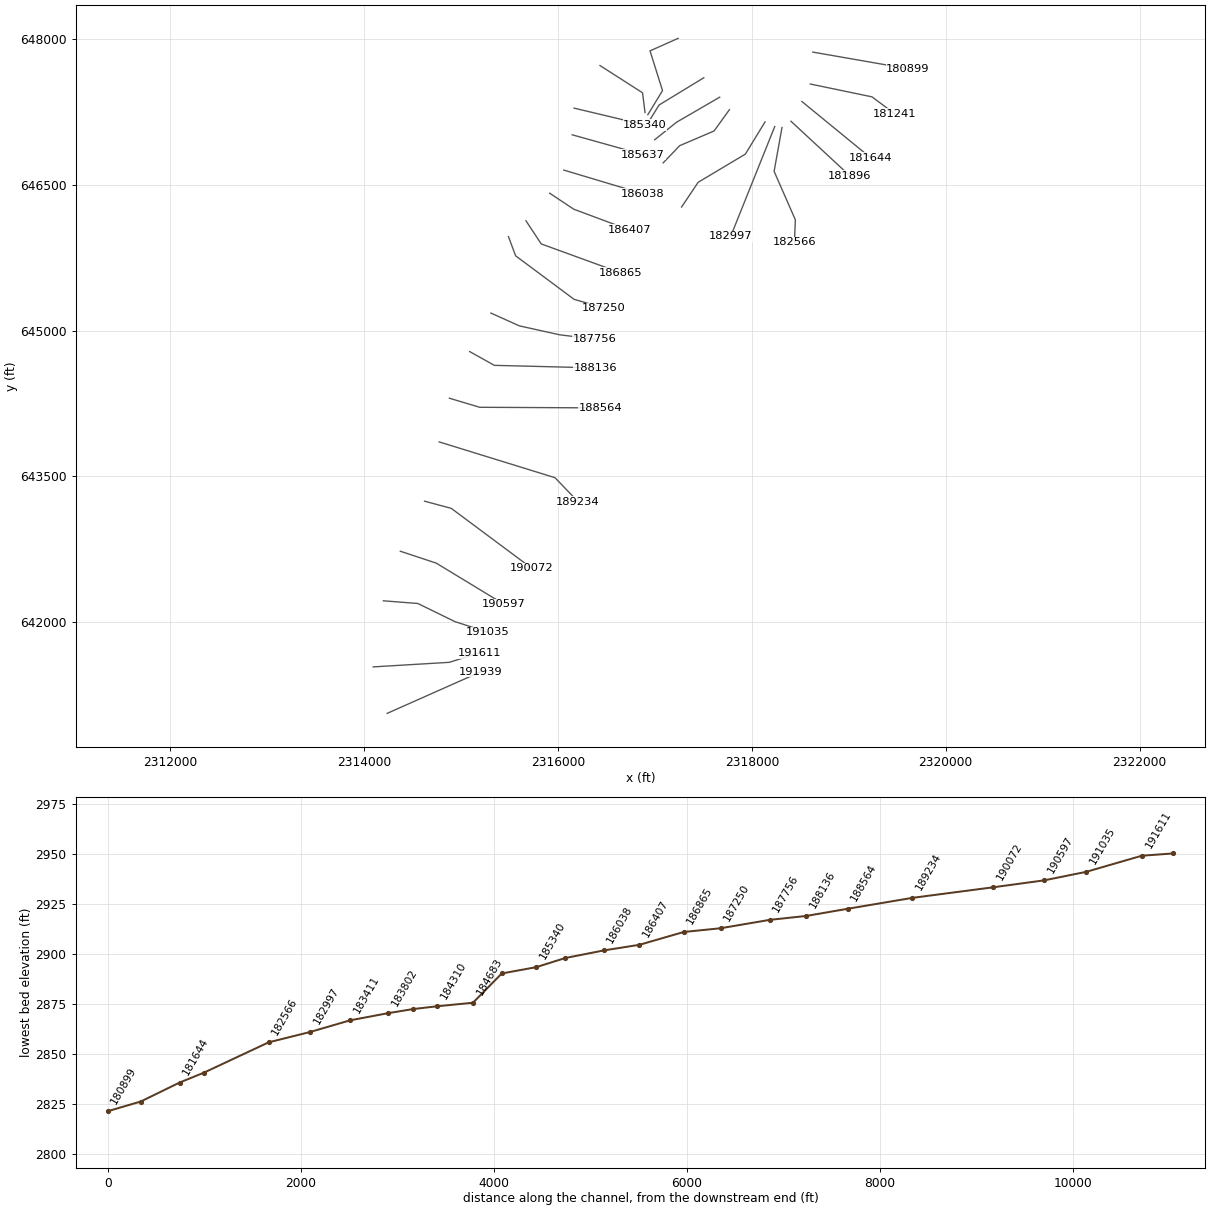
HEC-RAS study SHAVERSFK.prj: SHAVERSFK

--- SHAVERSFK.g01 (geometry) --- (continued)

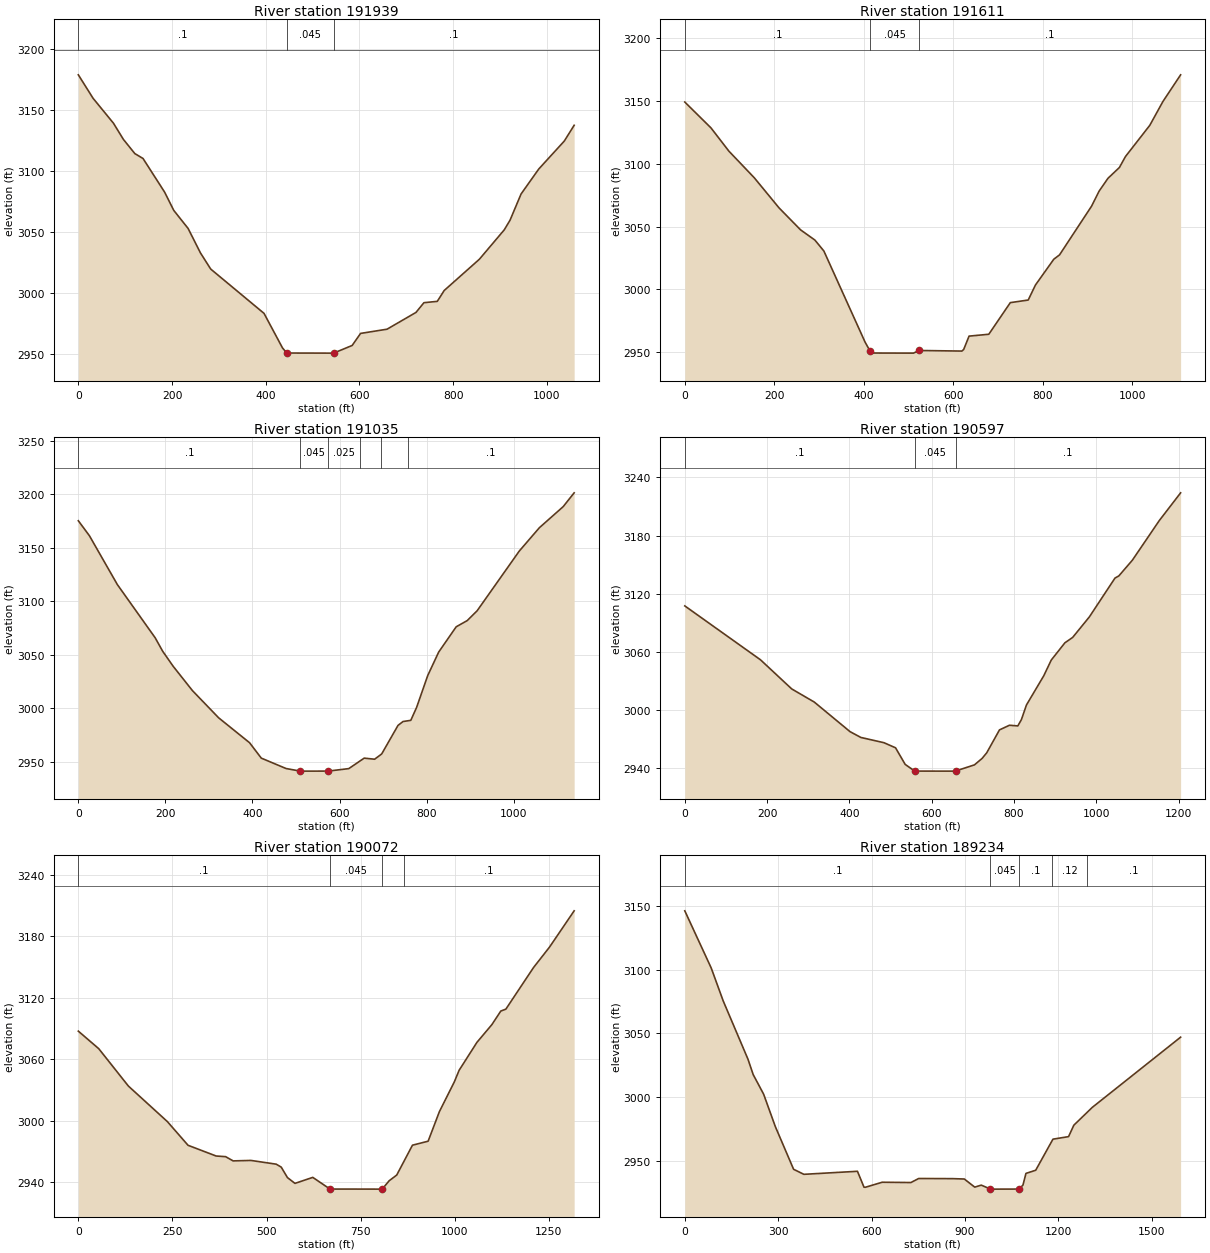
Type RM Length L Ch R = 1 ,191939  ,352.7,327.6,314.7
XS GIS Cut Line= 2
2314237.99481209641056.3988263382315205.21612672641485.710338534
#Sta/Elev= 30
       0 3178.98    31.5 3159.69      75 3139.22    96.2 3125.93   120.5  3114.3
   138.1 3110.23   184.1 3082.65   203.7 3067.61   234.3 3052.77   260.6  3032.7
   282.5 3019.42   396.3 2983.01   435.7 2954.66   444.8 2950.42   544.2 2950.34
   544.8 2950.34   584.4 2956.63   602.4 2966.54   658.8 2969.99   720.6 2983.77
   737.6 2991.78   766.1 2992.87   780.8 3001.77   855.8 3027.42     909 3051.62
   921.4 3059.58   944.9 3081.08   982.7 3101.62  1037.2  3124.6  1058.2 3137.53
#Mann= 3 ,-1,0
       0      .1       0   444.8    .045       0   544.8      .1       0
Bank Sta=444.8,544.8
XS Rating Curve= 0 ,0
Exp/Cntr(USF)=0,0
Exp/Cntr=0.3,0.1

Type RM Length L Ch R = 1 ,191611  ,606.5,576.9,558
XS GIS Cut Line= 4
2314093.82498055641535.0986830612314205.11703278  641542.0048299
2314879.57020608641582.436849615 2315185.8708245641679.163360696
#Sta/Elev= 30
       0 3149.13    58.5 3128.56    98.6 3110.02   155.2 3088.87   210.7 3064.84
   258.8 3047.35   290.9 3039.19   310.9 3030.51   403.1 2957.88     414 2950.93
   419.1 2949.25   511.3 2949.18   523.3 2951.28   619.5 2950.82   623.5 2952.13
   635.5 2962.72   679.6 2964.21   727.7 2989.39   767.7 2991.46   783.8 3003.37
   824.9 3023.96   837.7 3027.42   909.5 3066.31   926.2  3078.2     946  3088.4
   971.6 3097.03     985 3105.68  1039.5 3130.59  1068.8 3149.54  1108.4  3170.8
#Mann= 3 ,-1,0
       0      .1       0     414    .045       0   523.3      .1       0
Bank Sta=414,523.3
XS Rating Curve= 0 ,0
Exp/Cntr(USF)=0,0
Exp/Cntr=0.3,0.1

Type RM Length L Ch R = 1 ,191035  ,442,438,434.4
XS GIS Cut Line= 4
2314198.85735742642216.2408203962314553.92428544642188.589652386
2314937.60611273642001.5850642972315276.14890151641891.961685073
#Sta/Elev= 30
       0 3175.07    25.4 3161.13    89.6 3115.47   176.5 3065.72   193.9 3053.03
     218    3039   262.1 3016.35   322.3 2990.93   393.3 2967.66   420.2 2953.27
   477.1 2943.56   509.9 2941.12   573.9 2941.14   621.2 2943.48   656.6 2953.27
   680.5 2952.24   696.8  2957.2   734.3 2983.88   745.8 2987.48   763.6 2988.57
   776.9  3000.6   802.5 3030.44   827.7 3052.39   867.9 3075.99   893.3 3081.82
     916 3090.98  1012.7 3146.73    1059  3168.6  1113.6 3188.26  1138.8 3201.17
#Mann= 6 ,-1,0
       0      .1       0   509.9    .045       0   573.9    .025       0
  646.14      .1       0  696.14    .025       0  756.14      .1       0
Bank Sta=509.9,573.9
XS Rating Curve= 0 ,0
Exp/Cntr(USF)=0,0
Exp/Cntr=0.3,0.1

Type RM Length L Ch R = 1 ,190597  ,530.1,524.5,523
XS GIS Cut Line= 3
2314373.36813143642727.0338974022314744.15309057642604.513650033
2315440.58397035642182.141218315
#Sta/Elev= 30
       0 3107.43     184 3051.77   259.9  3021.7   314.7 3008.14   401.7 2977.58
   427.9 2971.62   484.1 2966.19   512.2 2960.93   535.6  2943.8   558.9 2936.88
   652.5 2936.85   657.9 2936.94     704 2943.32   722.7 2950.05   733.7 2955.71
   764.8 2979.43     789 2984.21   809.4 2983.53   818.1 2990.09   830.3 3005.12
   872.4 3035.29   890.6 3051.51   923.8 3069.34   942.6 3074.88   983.2 3096.06
  1045.5 3136.16  1054.8 3138.37  1087.6 3154.54    1153 3195.42    1205 3224.16
#Mann= 3 ,-1,0
       0      .1       0   558.9    .045       0   657.9      .1       0
Bank Sta=558.9,657.9
XS Rating Curve= 0 ,0
Exp/Cntr(USF)=0,0
Exp/Cntr=0.3,0.1

Type RM Length L Ch R = 1 ,190072  ,822.6,838,851.7
XS GIS Cut Line= 3
2314623.72681735643242.715876913 2314898.9155083643168.751631336
2315727.53928655642552.926177457
#Sta/Elev= 30
       0 3087.49    54.3 3070.37     133 3033.93   236.6 2999.27   291.5 2976.17
   366.3 2965.69   391.2 2965.09   411.3 2960.94   458.6  2961.4   525.7 2957.75
   539.1 2954.88   555.6 2944.68   575.6 2939.01   622.9 2944.87   668.7 2933.49
   807.3 2933.41   825.9 2941.58   845.9 2947.11   887.8 2976.26   929.4 2980.15
   959.3 3008.94   999.2 3038.15  1011.7 3049.27    1059 3076.51  1098.9  3093.9
  1122.5 3107.09  1135.9 3108.92  1209.6  3149.6  1251.9 3169.44  1317.4 3204.83
#Mann= 4 ,-1,0
       0      .1       0   668.7    .045       0   807.3    .025       0
  864.96      .1       0
Bank Sta=668.7,807.3
XS Rating Curve= 0 ,0
Exp/Cntr(USF)=0,0
Exp/Cntr=0.3,0.1

Type RM Length L Ch R = 1 ,189234  ,656.7,669.8,683.2
XS GIS Cut Line= 3
2314774.23992906643853.4596820352315969.35556426643484.724900866
 2316206.1953471643238.212466912
#Sta/Elev= 30
       0 3145.98    84.9  3101.2   123.4 3075.43     203  3029.8   219.7 3017.78
   253.2 3002.46   290.9 2977.01   349.5 2943.65   382.5 2939.71   554.6 2942.08
   575.5 2929.69   579.7 2929.55   634.1 2933.51   726.2 2933.28   751.3 2936.44
   860.2 2936.33   897.8 2936.04   931.3 2929.69   952.3 2931.25   981.6  2928.2
   987.1 2928.12  1073.7 2928.16  1086.2  2931.3  1095.8 2940.43  1127.1 2942.89
  1182.5 2967.23  1232.7 2969.22  1249.6 2978.17    1309 2992.14  1592.6 3047.08
#Mann= 5 ,-1,0
       0      .1       0   981.6    .045       0  1073.7      .1       0
    1180     .12       0 1290.71      .1       0
Bank Sta=981.6,1073.7
XS Rating Curve= 0 ,0
Exp/Cntr(USF)=0,0
Exp/Cntr=0.3,0.1

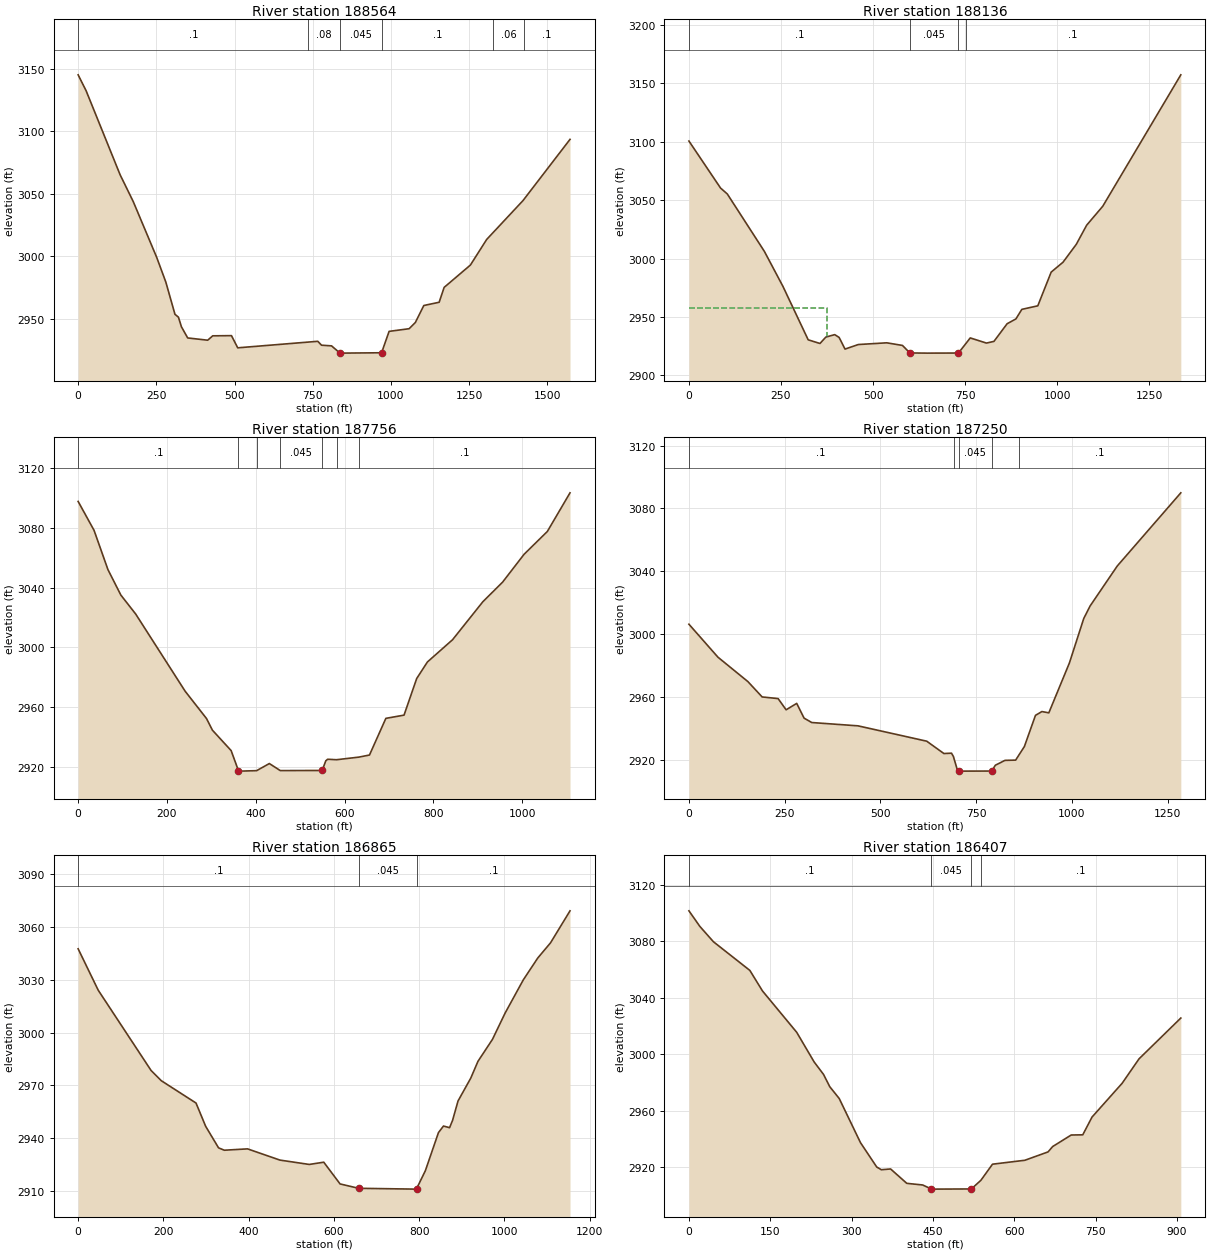
Type RM Length L Ch R = 1 ,188564  ,430.9,428.1,428.9
XS GIS Cut Line= 3
2314879.57020608644303.6760280152315192.31925858 644210.17373397
2316438.68067003644203.725299898
#Sta/Elev= 30
       0 3145.26    25.7 3132.42   134.2 3065.34   176.1 3043.95   251.1 2999.33
   280.4  2979.5   309.6 2953.72   320.7 2951.44   330.3 2943.74   350.3 2934.82
   414.3    2933   430.3 2936.51   490.3 2936.65   510.3 2926.91   766.3 2932.13
   778.3    2929   810.3 2928.48   835.9 2922.97   838.3 2922.67   970.3 2922.96
   994.3 2940.07  1058.3  2942.2  1078.3  2947.2  1105.3 2960.76  1154.3 2963.35
  1170.3 2975.24  1254.3 2993.12  1306.3 3013.58  1422.3 3044.64  1572.8 3093.65
#Mann= 6 ,-1,0
       0      .1       0  736.43     .08       0   835.9    .045       0
   970.3      .1       0 1326.43     .06       0 1426.43      .1       0
Bank Sta=835.9,970.3
XS Rating Curve= 0 ,0
Exp/Cntr(USF)=0,0
Exp/Cntr=0.3,0.1

Type RM Length L Ch R = 1 ,188136  ,485.5,379.7,370.7
XS GIS Cut Line= 3
2315089.14431342644784.0843663812315343.85745927644642.218816796
2316387.86418245644616.083384179
#Sta/Elev= 30
       0 3100.52    85.9  3060.3   104.2 3055.25   204.9 3006.14   255.3  2976.2
   323.9 2930.47   355.9 2927.35   371.9 2932.83   395.9  2934.9   407.9 2932.54
   423.9 2922.55   459.9 2926.43   537.1 2927.91     580 2925.66     600 2919.24
   647.9 2919.09     732 2919.17     764 2932.09     808 2927.69   828.4 2929.14
   864.1 2944.21   888.1 2948.37   904.1 2956.52   947.5 2959.56   983.8 2988.39
  1016.1  2996.9  1052.1  3012.2  1080.1 3028.49  1123.9 3044.74  1335.9 3157.16
#Mann= 4 ,-1,0
       0      .1       0     600    .045       0     732    .025       0
  751.56      .1       0
#XS Ineff= 2 , 0
          375.02 2957.41
Permanent Ineff=
       F       F
Bank Sta=600,732
XS Rating Curve= 0 ,0
Exp/Cntr(USF)=0,0
Exp/Cntr=0.3,0.1

Type RM Length L Ch R = 1 ,187756  ,557,506.1,486.2
XS GIS Cut Line= 4
2315308.39107187645180.6630618112315601.45312582645049.109759817
 2316017.7188198644956.8253010112316374.92351814 644913.73644048
#Sta/Elev= 30
       0  3097.9    35.8 3078.56    67.1 3052.21    96.2 3035.14   129.6 3022.42
   240.9  2970.7   289.1 2952.35   302.3 2944.59   344.5 2930.87   360.9 2917.45
     365 2917.13   401.9 2917.45   430.5 2922.21   455.1 2917.49   549.4 2917.57
   557.6 2924.05   561.7 2925.09   581.7 2924.77   631.3 2926.49   655.9 2927.91
   692.8  2952.5   733.7 2954.66   762.2  2979.2   786.3 2990.28     843 3005.22
   911.2 3030.68   955.6  3043.8  1003.9 3062.45  1056.3 3077.75  1107.4 3103.67
#Mann= 7 ,-1,0
       0      .1       0   360.9    .045       0   401.9     .08       0
   455.1    .045       0   549.4      .1       0   581.7    .025       0
   631.3      .1       0
Bank Sta=360.9,549.4
XS Rating Curve= 0 ,0
Exp/Cntr(USF)=0,0
Exp/Cntr=0.3,0.1

Type RM Length L Ch R = 1 ,187250  ,362.9,385.1,404.4
XS GIS Cut Line= 4
2315489.13997214645968.3095152362315563.10421772645770.694779403
2316166.03280345645322.5286113962316475.55763891645232.250534388
#Sta/Elev= 30
       0 3006.37    75.9 2985.38     154 2969.89   191.2 2960.13   232.9 2959.08
   253.8 2951.96   281.5 2956.03   300.7 2946.67   320.8 2943.86   441.6 2941.75
     621    2932   665.9 2924.15   685.8 2924.37   690.8 2922.25   700.8 2913.87
   704.6 2913.01   707.4 2912.96   790.5 2913.01   800.4 2916.72   825.4  2919.8
   853.3 2919.96   876.1 2928.59   905.1 2948.42   921.9 2950.84     940 2950.02
   993.7 2981.72  1031.2 3010.02  1047.8 3017.98  1118.7 3043.38  1284.7 3089.91
#Mann= 5 ,-1,0
       0      .1       0     691     .12       0   704.6    .045       0
   790.5    .025       0     861      .1       0
Bank Sta=704.6,790.5
XS Rating Curve= 0 ,0
Exp/Cntr(USF)=0,0
Exp/Cntr=0.3,0.1

Type RM Length L Ch R = 1 ,186865  ,452.3,457.8,461.7
XS GIS Cut Line= 3
2315669.50337991646131.8070874372315827.49001467645893.215026772
2316643.21692478645596.587059458
#Sta/Elev= 30
       0 3047.65    47.1 3024.13   171.2 2978.48     195  2972.7   276.6 2959.99
   299.2 2946.77   329.4 2934.54   342.9 2933.17   397.5 2933.94   473.5 2927.56
   542.3 2925.09   576.3 2926.36   614.6 2914.01   658.1 2911.53   792.4 2911.06
  794.042911.255   814.7 2921.54   845.4 2943.17   857.2 2946.91   871.5 2945.98
   878.5 2950.12   891.3 2961.14   921.1  2974.1   938.1 2983.68   972.1 2996.17
  1001.9 3011.17  1044.5    3030  1078.5 3042.44  1108.3 3051.02  1154.1 3069.23
#Mann= 3 ,-1,0
       0      .1       0   658.1    .045       0  794.04      .1       0
Bank Sta=658.1,794.04
XS Rating Curve= 0 ,0
Exp/Cntr(USF)=0,0
Exp/Cntr=0.3,0.1

Type RM Length L Ch R = 1 ,186407  ,367.4,369.1,371.8
XS GIS Cut Line= 3
2315914.54387464646415.5381866072316162.80858642 646251.10311777
2316733.49500179646038.304793392
#Sta/Elev= 30
       0 3101.56    20.2 3090.51    45.1 3079.71   112.3 3059.41   135.6 3044.88
   198.7 3015.62   230.9 2994.62   248.2 2985.81   259.7 2977.11   277.1 2968.78
   316.3 2937.56   346.2 2920.33   354.7 2918.39   371.8 2918.94   401.7 2908.76
   430.9 2907.61   446.5 2904.86   448.7 2904.67   520.8  2904.8   538.3 2910.92
   559.7 2922.31   619.4 2925.09   662.1    2931   670.6 2934.78   704.8 2942.96
   726.1 2943.08   743.2 2955.65   798.7 2979.55   829.9 2996.86   906.9 3025.71
#Mann= 4 ,-1,0
       0      .1       0   446.5    .045       0   520.8    .025       0
  537.78      .1       0
Bank Sta=446.5,520.8
XS Rating Curve= 0 ,0
Exp/Cntr(USF)=0,0
Exp/Cntr=0.3,0.1

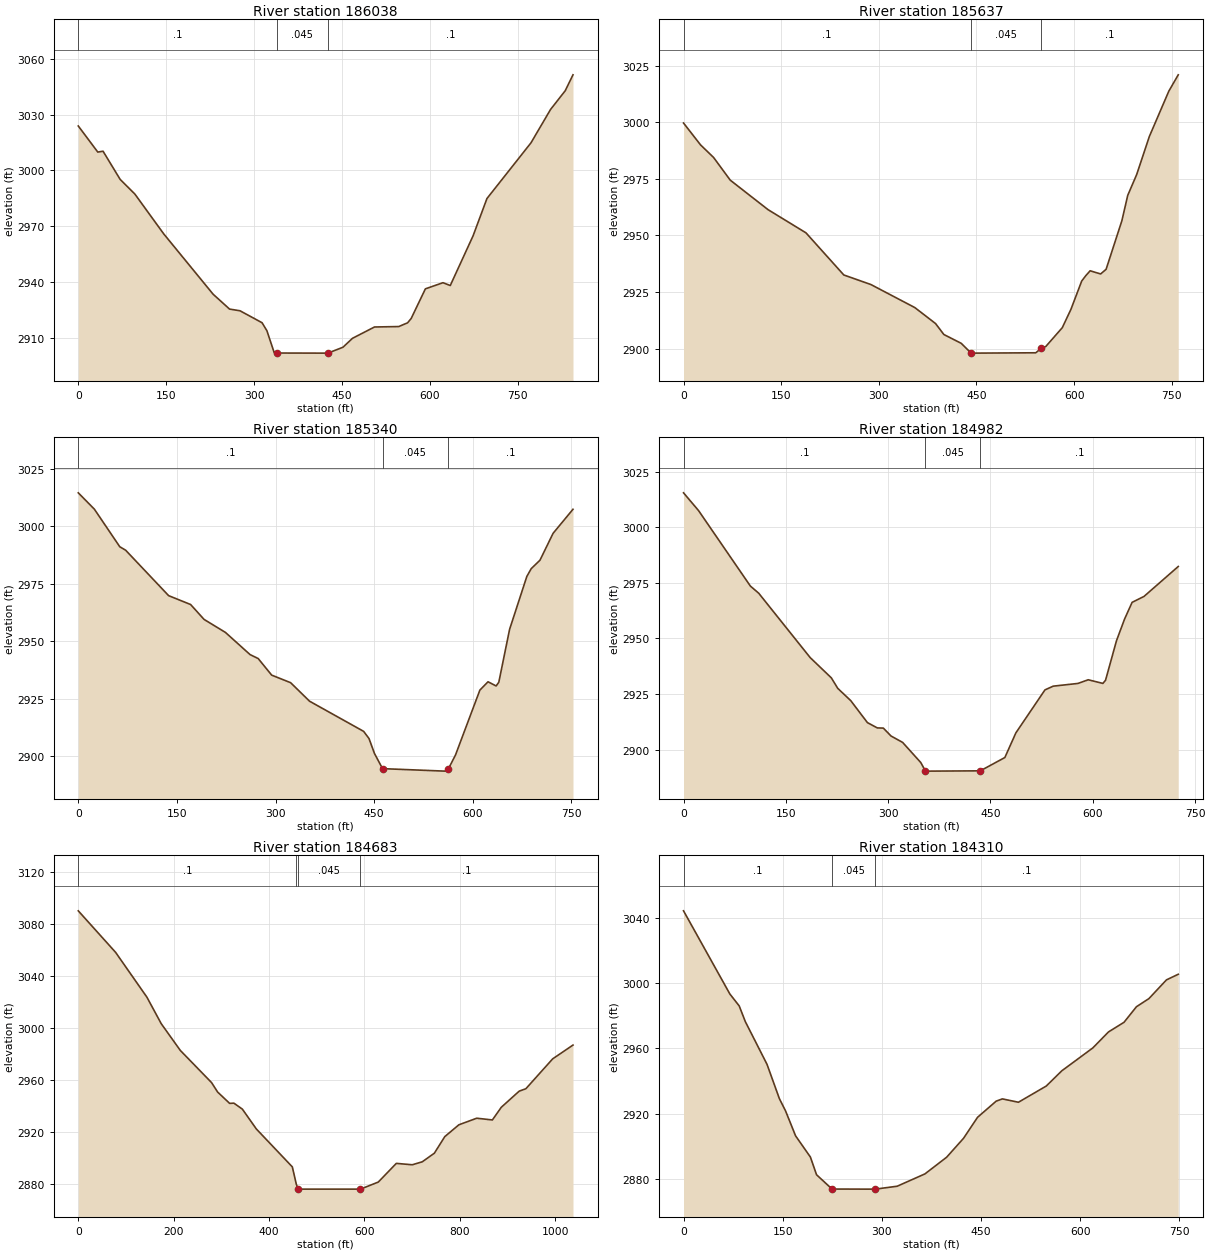
Type RM Length L Ch R = 1 ,186038  ,391.4,401.3,399.7
XS GIS Cut Line= 2
2316059.63364126646654.130247272 2316868.9121173646412.313969571
#Sta/Elev= 30
       0 3023.89    33.3 3009.88    42.3 3010.33    71.5 2995.19    96.6 2987.33
   145.8 2965.96   230.2 2933.51   258.3 2925.52   276.1 2924.61   313.7 2918.21
     322 2913.92   334.5 2902.12   338.7 2901.91     418 2901.86   426.4 2901.88
   451.9 2905.03   468.1 2909.81   505.7  2915.9   547.1 2916.13   562.2 2918.14
   568.3 2920.44   592.6 2936.39   622.6 2939.69   635.1 2938.19     674 2964.86
   697.7 2984.91   772.9 3014.85   806.3 3032.77   831.3  3042.8   844.6 3051.37
#Mann= 3 ,-1,0
       0      .1       0   338.7    .045       0   426.4      .1       0
Bank Sta=338.7,426.4
XS Rating Curve= 0 ,0
Exp/Cntr(USF)=0,0
Exp/Cntr=0.3,0.1

Type RM Length L Ch R = 1 ,185637  ,290.9,297.4,296
XS GIS Cut Line= 2
2316147.01924512 647017.593822572316878.94557233646813.292515669
#Sta/Elev= 30
       0 2999.65    26.1 2990.01    46.2 2984.43    71.8 2974.41   129.9 2961.38
   188.1 2951.15   246.2 2932.55   287.8 2928.33   355.2 2918.17   387.1 2911.11
   399.9 2906.26   426.6 2902.36441.0435 2898.25   445.6 2898.04   541.1 2898.19
549.12962900.084   556.5 2900.98   581.8 2909.28   595.1 2917.39   611.6 2929.86
   618.1 2932.32   624.6  2934.4   640.7    2933   649.1 2935.05   673.3 2956.48
   682.3 2967.68   696.1 2976.92   715.5 2993.69   745.4  3013.7   759.9 3020.93
#Mann= 3 ,-1,0
       0      .1       0441.0435    .045       0549.1296      .1       0
Bank Sta=441.0435,549.1296
XS Rating Curve= 0 ,0
Exp/Cntr(USF)=0,0
Exp/Cntr=0.3,0.1

Type RM Length L Ch R = 1 ,185340  ,373.8,357.9,346.1
XS GIS Cut Line= 2
2316166.03280345647292.5252204042316897.93007063647118.417500459
#Sta/Elev= 30
       0 3014.62    24.5  3007.5    63.1 2991.16    72.1 2989.63   137.4 2969.87
   170.8 2966.02   191.3 2959.53   223.8 2953.87   261.2 2944.23   273.6  2942.5
   294.1 2935.29   322.9    2932   351.7 2923.94   433.9 2910.82   442.1  2907.7
   450.4  2901.2   462.7 2894.59   557.3 2893.51  562.622894.381   573.7 2900.58
   610.7 2928.77   623.1 2932.39   635.4 2930.57   639.5  2932.2   655.9 2955.22
   682.1 2978.23   688.8 2981.63   702.1  2985.3     722 2996.98   752.3 3007.47
#Mann= 3 ,-1,0
       0      .1       0   462.7    .045       0  562.62      .1       0
Bank Sta=462.7,562.62
XS Rating Curve= 0 ,0
Exp/Cntr(USF)=0,0
Exp/Cntr=0.3,0.1

Type RM Length L Ch R = 1 ,184982  ,337.2,298.6,269.7
XS GIS Cut Line= 3
2316433.64281744647731.0187373022316872.13633434647450.511855169
2316897.93007063647247.386181899
#Sta/Elev= 30
       0 3015.45      22 3007.48      98 2973.54   110.3  2970.3   185.6 2941.41
   216.7 2932.27   226.1 2927.56   245.2 2922.02   269.6 2912.15   284.1 2909.77
   292.9 2909.69   304.3 2906.11   321.2 2903.26   347.8 2894.21   354.4 2890.55
   359.1 2890.34   435.1 2890.47   471.1 2896.45   487.3 2907.56   529.9 2926.86
     542 2928.54   578.3 2929.76   593.3 2931.41   614.8 2929.78   618.7 2931.18
   634.8    2949   646.7 2958.77   657.7 2966.22   675.1 2968.87   725.3 2982.33
#Mann= 3 ,-1,0
       0      .1       0   354.4    .045       0   435.1      .1       0
Bank Sta=354.4,435.1
XS Rating Curve= 0 ,0
Exp/Cntr(USF)=0,0
Exp/Cntr=0.3,0.1

Type RM Length L Ch R = 1 ,184683  ,458.7,373.2,306
XS GIS Cut Line= 4
2317239.69707645648011.5256194362316949.51754321647882.556937995
2317078.48622465647473.0813744212316926.94802395647224.816662647
#Sta/Elev= 30
       0 3090.24    78.3 3058.23   143.9 3023.72   174.1  3003.2     214 2982.65
   279.6 2957.83   292.3 2950.56   317.5 2941.81   326.4 2941.99   344.2 2937.38
   373.5  2922.1     449 2892.85   457.4 2879.41   461.6 2875.77   465.8 2875.72
   591.9 2875.72   629.3 2881.16   667.1 2895.56   700.6  2894.5   721.6 2896.79
   746.9 2903.41   768.8  2916.2   798.3  2925.3   835.8 2930.38   868.6 2929.04
   887.3  2938.8   924.8 2951.23   938.9 2953.12   995.1 2976.14  1037.7 2986.77
#Mann= 4 ,-1,0
       0      .1       0  457.55    .025       0   461.6    .045       0
   591.9      .1       0
Bank Sta=461.6,591.9
XS Rating Curve= 0 ,0
Exp/Cntr(USF)=0,0
Exp/Cntr=0.3,0.1

Type RM Length L Ch R = 1 ,184310  ,250.8,250.7,262.4
XS GIS Cut Line= 3
 2317504.0828734647605.2742728972317043.01983725647324.767390764
2316933.39645803647147.435453783
#Sta/Elev= 30
       0 3044.24    70.1 2993.34    84.2 2986.06    93.5 2976.41   126.3 2950.29
     145 2929.28   154.3 2921.82   169.5 2906.53   191.9 2893.56   201.2 2882.73
   224.6 2873.99   276.1 2873.94   290.2 2873.95   323.1 2875.71   365.1 2883.25
   397.9 2893.45   423.5 2905.05   444.7  2917.9   472.8 2927.76   482.2 2929.16
   506.5  2927.1   548.6 2937.02   572.1 2946.34   619.1 2960.37   642.7 2970.13
   666.2 2976.03     685 2985.56   703.8 2990.51   730.4 3001.99   748.2 3005.42
#Mann= 3 ,-1,0
       0      .1       0   224.6    .045       0   290.2      .1       0
Bank Sta=224.6,290.2
XS Rating Curve= 0 ,0
Exp/Cntr(USF)=0,0
Exp/Cntr=0.3,0.1

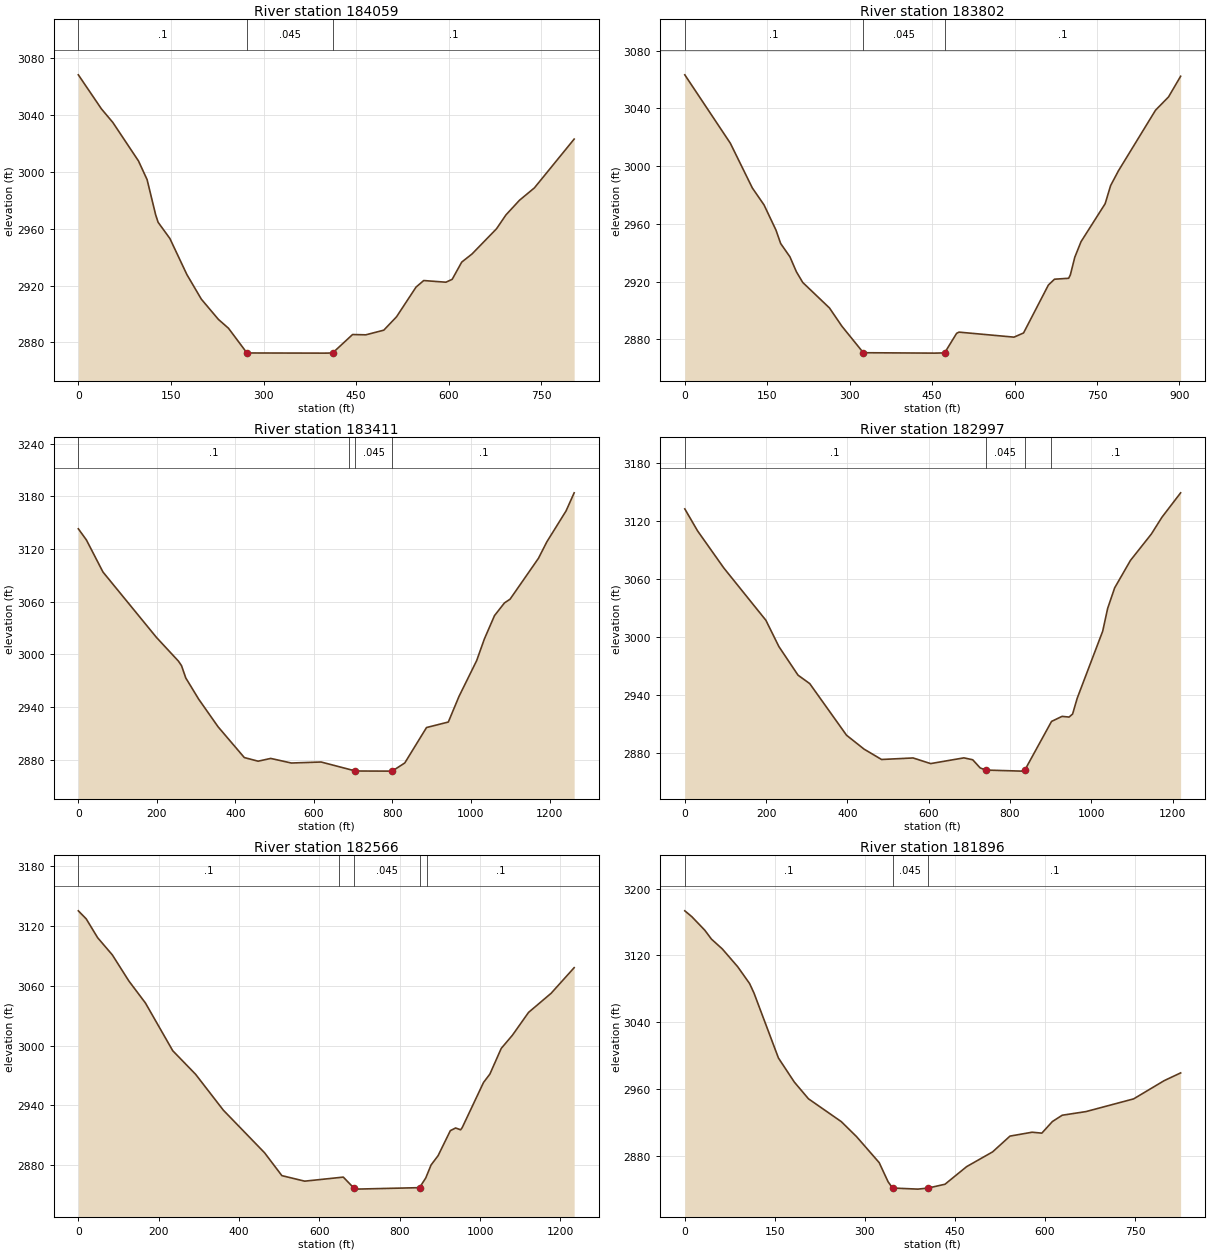
Type RM Length L Ch R = 1 ,184059  ,265.7,257.4,248
XS GIS Cut Line= 3
2317668.51794224647405.3728166642317223.57599127647147.435453783
2316997.88079875646966.879299766
#Sta/Elev= 30
       0 3067.96    37.4 3044.06    55.9 3034.52    97.5 3007.44   111.4 2994.39
   125.2  2969.8   129.2 2964.44   148.3 2953.04   175.8 2927.76   199.2 2910.48
   226.9 2896.23   243.3 2889.99   273.2 2872.64   399.2 2872.53   411.9 2872.61
   444.3 2885.59   465.8 2885.38   494.9 2888.65   515.5 2898.03   547.2 2918.94
   559.6  2923.5   595.5 2922.33   605.7 2924.35   621.1 2936.43   637.9 2942.19
   677.5 2959.85   692.8 2969.59   714.7 2979.87   738.9 2988.57   803.3 3022.84
#Mann= 3 ,-1,0
       0      .1       0   273.2    .045       0   411.9      .1       0
Bank Sta=273.2,411.9
XS Rating Curve= 0 ,0
Exp/Cntr(USF)=0,0
Exp/Cntr=0.3,0.1

Type RM Length L Ch R = 1 ,183802  ,393.1,391.1,400.8
XS GIS Cut Line= 4
2317768.46867035647276.4041352232317610.48203559647057.157376774
2317255.81816163646905.6191760812317084.93465872  646728.2872391
#Sta/Elev= 30
       0 3063.25    82.8 3015.91   122.9 2984.89   144.2 2973.13   165.9 2955.71
   174.4 2946.44   191.3  2937.2   203.1 2926.83   214.6 2919.44   263.3 2901.75
   285.8 2889.17   324.9 2870.77   454.8 2870.49   472.8 2870.67   494.6  2884.2
   498.9 2885.03     599 2881.56   616.4 2884.46   661.6 2917.67   672.7 2921.69
   698.4 2922.33   701.5 2924.63   709.7 2936.99     721 2947.71   764.9    2974
   774.8 2986.52   788.9 2996.68   856.5 3038.73   880.2 3047.95   902.2 3062.25
#Mann= 3 ,-1,0
       0      .1       0   324.9    .045       0   472.8      .1       0
Bank Sta=324.9,472.8
XS Rating Curve= 0 ,0
Exp/Cntr(USF)=0,0
Exp/Cntr=0.3,0.1

Type RM Length L Ch R = 1 ,183411  ,393.6,414,454.8
XS GIS Cut Line= 4
2318136.02941246647150.6596708192317932.90373919646818.565316109
2317446.04696675646528.3857828672317275.16346384646273.672637022
#Sta/Elev= 30
       0 3142.93    20.5 3130.28    62.7 3093.75   198.7 3019.37   254.9 2992.24
   262.8 2987.06   273.7 2973.02   306.5 2948.92   355.9 2917.44   422.7  2882.4
   457.9 2878.24     490  2881.4   542.5 2876.17   618.3 2877.32   705.9 2867.07
   796.4 2866.93   799.9 2867.12   831.4 2876.22   886.8 2916.58   942.3 2922.84
   969.6 2952.11  1014.5 2992.79  1034.1 3017.43  1059.9 3044.02  1085.2 3058.47
  1099.6 3062.77  1171.9 3109.33  1193.2 3128.06  1242.2  3163.3  1262.8  3183.9
#Mann= 4 ,-1,0
       0      .1       0  689.29    .025       0   705.9    .045       0
   799.9      .1       0
Bank Sta=705.9,799.9
XS Rating Curve= 0 ,0
Exp/Cntr(USF)=0,0
Exp/Cntr=0.3,0.1

Type RM Length L Ch R = 1 ,182997  ,365.6,430.7,473
XS GIS Cut Line= 2
2318235.98014058647102.296415278 2317781.3655385645970.596235636
#Sta/Elev= 30
       0 3132.92    31.4 3110.14      96 3071.66   199.5 3017.45   231.4 2990.26
   278.5 2960.59   307.3 2951.82   397.8 2898.34   440.9 2883.92     484 2873.17
   561.6 2874.76   604.7 2868.92   686.6 2874.86   708.2 2872.88   726.5 2864.46
   739.9 2862.22   828.9 2861.11   836.5 2862.29   902.1 2912.64     928 2917.87
   945.2 2917.14   953.9  2920.3   965.3 2936.78  1027.9 3006.12  1040.1 3029.73
  1057.3 3051.03  1096.1 3079.45  1147.7 3106.92  1173.7 3124.29  1219.6 3149.57
#Mann= 4 ,-1,0
       0      .1       0   739.9    .045       0   836.5    .025       0
     900      .1       0
Bank Sta=739.9,836.5
XS Rating Curve= 0 ,0
Exp/Cntr(USF)=0,0
Exp/Cntr=0.3,0.1

Type RM Length L Ch R = 1 ,182566  ,602.3,670,695.6
XS GIS Cut Line= 4
2318310.77672889647092.474814093 2318229.5317065646641.233379128
2318448.77846495646141.4797385452318439.10581385645911.771782428
#Sta/Elev= 30
       0 3135.12    19.6 3127.07    48.1 3108.14    84.6 3090.93   125.6 3064.85
     167 3042.65     235 2994.78   291.9 2971.12     361 2935.09   463.6 2892.36
   506.6 2869.46   563.4 2863.91   659.5 2867.97   685.7 2857.07   690.1 2855.92
   849.2 2857.39   864.8 2867.16   877.9 2880.12   895.4 2889.45   925.9 2914.57
     939 2917.26   951.5 2915.46   955.4 2917.57  1008.5 2962.91  1024.3 2971.31
  1052.6 2997.09  1080.6 3010.41  1120.6 3033.22  1176.7 3052.37  1234.1 3078.08
#Mann= 5 ,-1,0
       0      .1       0   648.5    .025       0   685.7    .045       0
   849.2    .025       0   868.5      .1       0
Bank Sta=685.7,849.2
XS Rating Curve= 0 ,0
Exp/Cntr(USF)=0,0
Exp/Cntr=0.3,0.1

Type RM Length L Ch R = 1 ,181896  ,250.4,251.8,254
XS GIS Cut Line= 2
2318403.63942645647157.1081048912319009.79222922646596.094340624
#Sta/Elev= 30
       0 3173.36    11.7 3166.36    33.4 3150.13    44.3 3139.62    62.6 3127.74
    88.1 3106.56   107.9 3086.49   115.2  3075.2     156 2997.45   182.4 2968.74
     206 2948.71   260.7 2921.42   286.2 2903.43   323.8 2872.44   338.6 2849.61
  346.012842.094   388.1 2840.77   405.1 2842.02   433.4 2846.61   469.5 2867.67
   512.7 2885.28   541.7 2904.14   578.5 2908.77   594.7 2907.68   612.3 2921.54
   628.7 2929.09   668.3 2933.44   747.6 2948.61   798.5  2970.4   825.9 2979.66
#Mann= 3 ,-1,0
       0      .1       0  346.01    .045       0   405.1      .1       0
Bank Sta=346.01,405.1
XS Rating Curve= 0 ,0
Exp/Cntr(USF)=0,0
Exp/Cntr=0.3,0.1

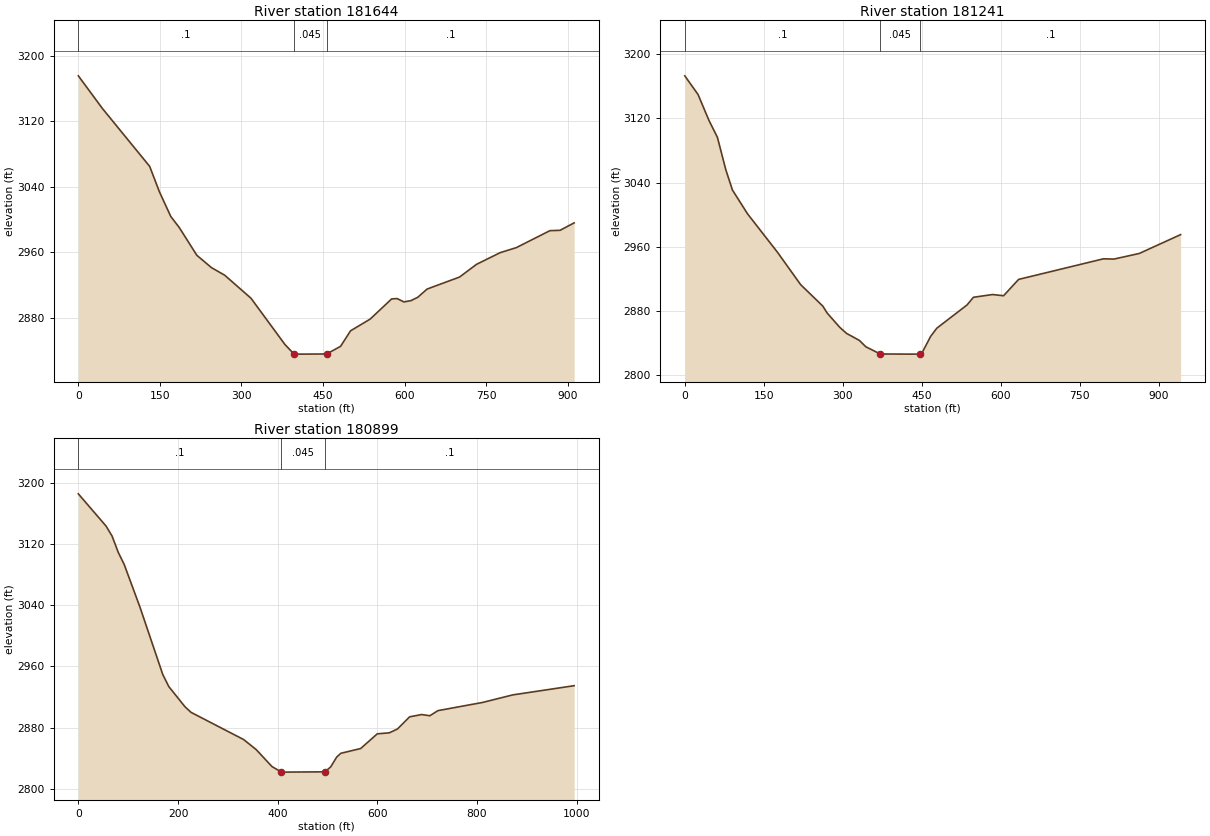
Type RM Length L Ch R = 1 ,181644  ,388.5,403,420.2
XS GIS Cut Line= 2
2318516.48702271 647360.23377816 2319222.5905536646783.098928713
#Sta/Elev= 30
       0 3175.46    44.6 3135.35   131.2 3064.99   149.4 3033.58   170.1 3003.79
   185.6  2990.4     218 2956.44     245 2941.34   269.2 2932.15   317.5 2904.11
     380 2847.61   396.7 2835.95   409.3 2835.83   456.8 2836.01   482.4 2845.37
   500.7 2864.27   536.9 2878.65   576.2 2903.17   586.3 2903.63   598.9 2899.56
   611.6 2901.06   624.5 2905.28   641.6 2915.26   701.2  2929.9   732.5 2945.45
   775.9 2959.65   805.5 2965.76   867.5 2986.52     886 2986.91     912 2996.02
#Mann= 3 ,-1,0
       0      .1       0   396.7    .045       0   456.8      .1       0
Bank Sta=396.7,456.8
XS Rating Curve= 0 ,0
Exp/Cntr(USF)=0,0
Exp/Cntr=0.3,0.1

Type RM Length L Ch R = 1 ,181241  ,340.8,342.3,343.6
XS GIS Cut Line= 3
2318603.54088268647540.7899321772319238.71163878  647408.5970337
2319474.07948241647234.489313755
#Sta/Elev= 30
       0 3172.97    25.2 3149.68    45.6 3117.88    61.9 3096.44      78 3055.73
    90.5 3030.71   119.1 3001.12   176.1 2953.13     220 2912.89   262.1 2886.14
   270.3 2877.55   294.4 2859.63   307.1 2852.19   331.6 2843.39   343.8 2835.48
   371.1 2826.52   429.7 2826.34   446.6 2826.44     450 2827.26   466.9 2848.55
   478.7 2858.74   535.9 2887.56   548.1 2897.15   584.3 2900.57   605.3 2899.07
   633.9 2919.41   794.9 2945.05   814.8 2944.72     863 2951.72   941.5 2975.19
#Mann= 3 ,-1,0
       0      .1       0   371.1    .045       0   446.6      .1       0
Bank Sta=371.1,446.6
XS Rating Curve= 0 ,0
Exp/Cntr(USF)=0,0
Exp/Cntr=0.3,0.1

Type RM Length L Ch R = 1 ,180899  ,273.4,280,285.5
XS GIS Cut Line= 2
2318629.33461897647869.6600698512319609.49659792647698.776566942
#Sta/Elev= 30
       0 3186.35    55.7 3144.03    67.8 3130.88      80 3109.75    92.2 3093.52
   123.9 3037.39   169.4 2949.58   181.5 2933.69     214 2907.19   226.2 2899.85
   331.8 2864.18     357 2850.98   388.6 2828.77   407.4  2821.6   408.9  2821.5
   494.7 2821.89   506.4 2828.39   518.5 2841.32   526.7 2846.19   566.5 2852.43
   599.8 2871.69   624.1 2873.05   640.4 2878.07   664.7 2894.01   689.1    2897
   705.3 2895.41   721.6 2902.12   810.9 2912.81   871.8 2922.76   994.9 2934.82
#Mann= 3 ,-1,0
       0      .1       0   407.4    .045       0   494.7      .1       0
Bank Sta=407.4,494.7
XS Rating Curve= 0 ,0
Exp/Cntr(USF)=0,0
Exp/Cntr=0.3,0.1