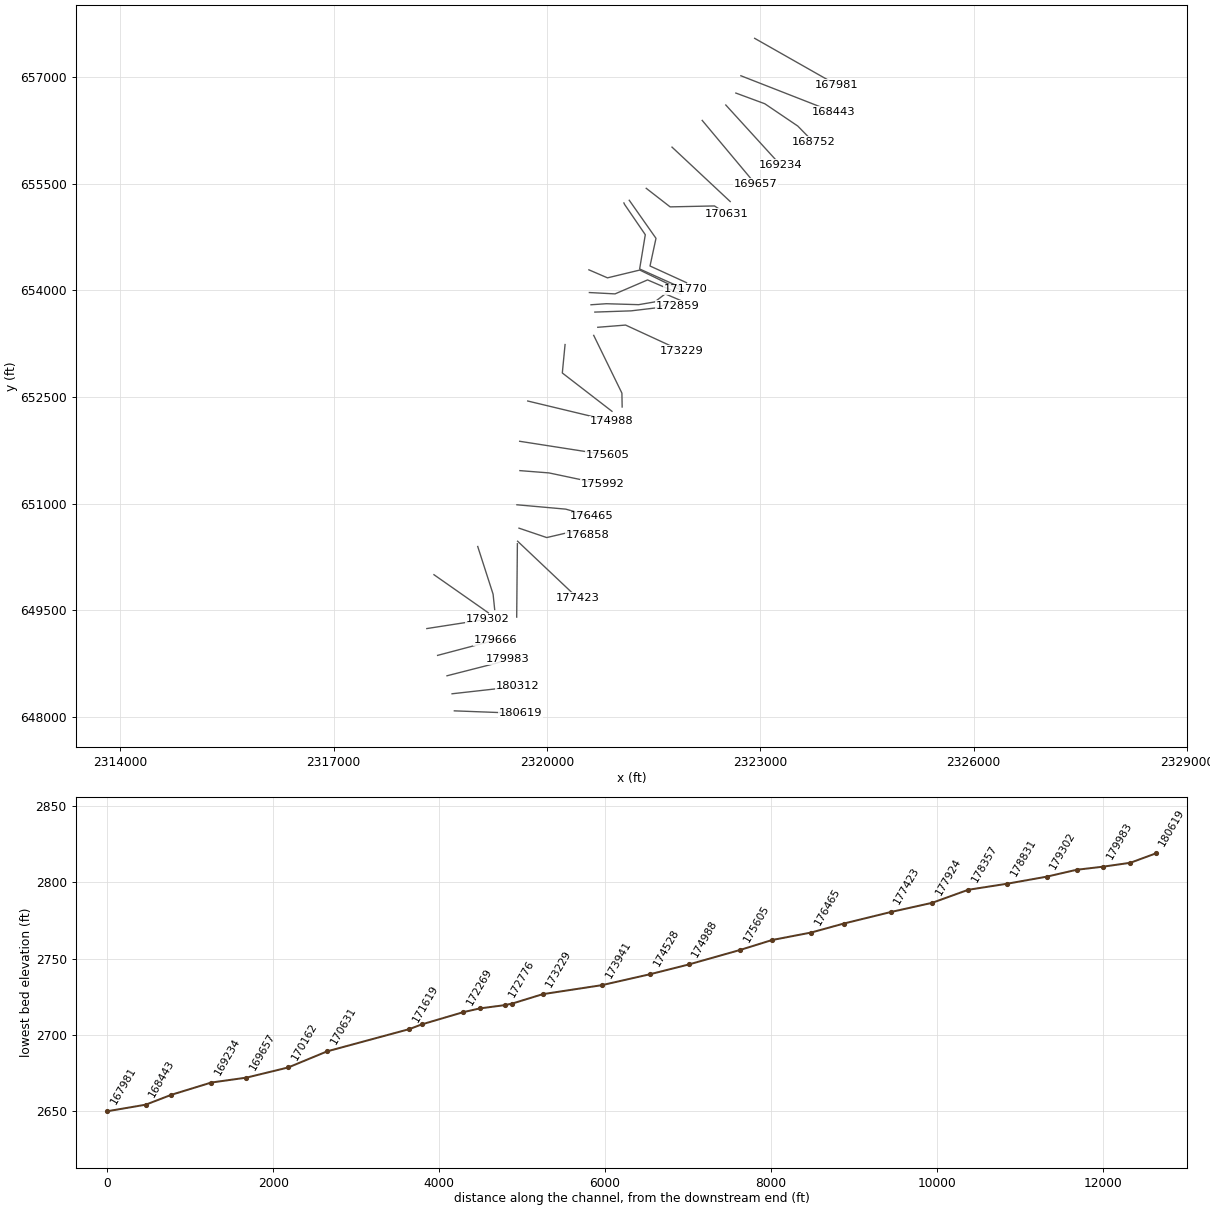
HEC-RAS study SHAVERSFK.prj: SHAVERSFK

--- SHAVERSFK.g01 (geometry) --- (continued)

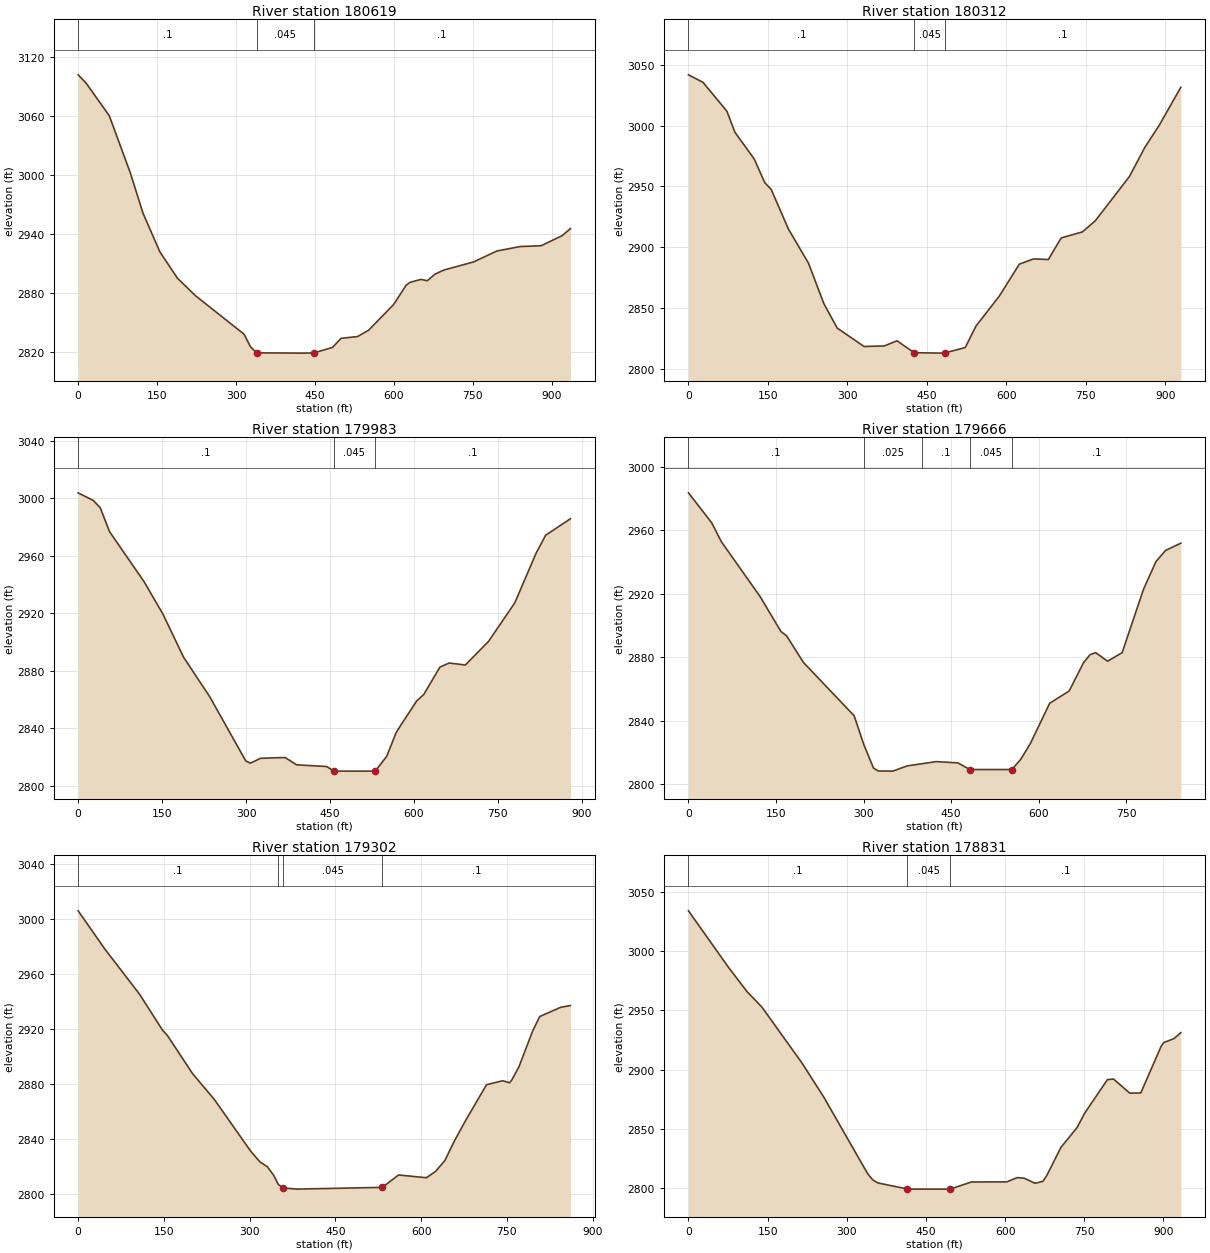
Type RM Length L Ch R = 1 ,180619  ,305.6,307.1,311.4
XS GIS Cut Line= 2
2318697.04317673648085.6826112642319632.06611717648050.216223868
#Sta/Elev= 30
       0 3101.98    15.1 3093.59    59.2 3060.34    99.2 3002.16   123.2 2961.34
   155.2 2922.05   188.6 2895.19   223.3 2877.17   315.4 2838.13   327.4 2825.43
   339.4 2819.18   427.4  2818.9   447.9  2819.1   483.5 2824.73   499.5 2833.91
   531.1  2835.8   551.9 2842.13   599.6 2868.34   623.6 2888.13     631 2890.95
   651.6 2893.91   663.6 2892.52   678.4 2899.32   695.6  2903.5   751.7 2911.69
   795.7 2922.75   840.4 2927.34   879.8  2928.1   919.8 2938.38   935.7 2945.59
#Mann= 3 ,-1,0
       0      .1       0   339.4    .045       0   447.9      .1       0
Bank Sta=339.4,447.9
XS Rating Curve= 0 ,0
Exp/Cntr(USF)=0,0
Exp/Cntr=0.3,0.1

Type RM Length L Ch R = 1 ,180312  ,324.3,328.6,333.9
XS GIS Cut Line= 2
2318664.98140832648325.9333913812319588.61485816648429.707662477
#Sta/Elev= 30
       0  3041.7    27.4 3035.55    72.5  3011.8    87.7 2994.45     124 2972.54
   144.1 2952.97   156.2  2947.4   188.4 2915.09   226.6  2886.7   255.5 2853.58
   280.8 2833.35   331.5 2818.23   369.5 2818.64   393.7 2822.89426.10532813.079
   482.2 2812.75484.67652812.998   522.5 2817.36   542.6 2834.89   586.9 2859.73
   624.6 2885.96   651.3 2890.26   679.4 2889.76   703.6 2907.53   743.8  2912.5
     768 2921.64   832.4 2958.01   861.5 2981.99   888.8 3000.28   929.4 3031.43
#Mann= 3 ,-1,0
       0      .1       0426.1053    .045       0484.6765      .1       0
Bank Sta=426.1053,484.6765
XS Rating Curve= 0 ,0
Exp/Cntr(USF)=0,0
Exp/Cntr=0.3,0.1

Type RM Length L Ch R = 1 ,179983  ,316.8,317.4,317.5
XS GIS Cut Line= 3
2318593.86823157648578.9878177752319299.97176246648759.543971792
2319441.83731205648811.131444368
#Sta/Elev= 30
       0 3003.91    27.2 2998.55    39.5 2993.53    56.1 2976.88     118 2941.94
   151.7 2919.37   188.2 2889.61   234.9 2862.15   299.6 2817.28   307.9 2815.74
   325.9 2819.13   369.8  2819.7   390.5 2814.59   444.2 2813.41   456.5 2810.26
   466.1 2810.21   530.9 2810.22   551.5 2820.56     568 2836.79   575.8 2841.74
   605.2 2859.14   617.6 2863.56   646.5 2882.61     663 2885.45   691.9 2884.08
   733.3 2900.48   780.2 2927.27   818.4 2961.95   835.4 2974.38   879.8 2985.89
#Mann= 3 ,-1,0
       0      .1       0   456.5    .045       0   530.9      .1       0
Bank Sta=456.5,530.9
XS Rating Curve= 0 ,0
Exp/Cntr(USF)=0,0
Exp/Cntr=0.3,0.1

Type RM Length L Ch R = 1 ,179666  ,407.7,363.7,355.8
XS GIS Cut Line= 2
 2318461.6753331648865.9431339812319277.40224321649081.965675394
#Sta/Elev= 30
       0  2983.6    39.8 2964.72    56.4 2952.78   122.6 2918.32   158.5 2896.19
   168.3 2893.42   197.1 2876.67     284 2843.07   300.5 2824.95   317.1 2810.14
   325.3 2808.28   350.2 2808.19     375  2811.5   424.6 2814.19   461.9 2813.37
   482.3  2809.2   554.3  2809.2   569.5  2815.6     586 2825.63   619.1 2850.97
   652.5 2858.71   677.1 2876.55   688.4 2881.61   697.8  2882.9   718.4 2877.47
   743.3 2882.89     780  2922.9   801.2 2940.24   817.7 2947.29   843.8 2951.85
#Mann= 5 ,-1,0
       0      .1       0     300    .025       0     400      .1       0
   482.3    .045       0   554.3      .1       0
Bank Sta=482.3,554.3
XS Rating Curve= 0 ,0
Exp/Cntr(USF)=0,0
Exp/Cntr=0.3,0.1

Type RM Length L Ch R = 1 ,179302  ,516.1,470.7,438.7
XS GIS Cut Line= 2
 2318310.1371324649243.1765271952319161.33042991649375.369425672
#Sta/Elev= 30
       0 3005.83    46.6 2978.13   107.3 2945.33   147.8 2919.04   155.9  2915.4
   200.4 2887.44   238.3 2868.79   301.4 2831.51   317.8 2823.51   330.7 2820.04
   342.1 2813.73   350.2 2807.02   358.3  2804.6   381.9 2803.65   532.3 2804.94
   560.6 2813.94   609.3 2811.93   625.4 2816.54   641.6  2824.4   657.8 2838.25
   678.1 2853.64   714.5 2879.49   742.8 2882.38     755 2880.91     759 2883.15
   771.2 2892.51   795.5  2918.8   807.6 2929.04     844  2935.7   861.4 2937.05
#Mann= 4 ,-1,0
       0      .1       0     350    .025       0   358.3    .045       0
   532.3      .1       0
Bank Sta=358.3,532.3
XS Rating Curve= 0 ,0
Exp/Cntr(USF)=0,0
Exp/Cntr=0.3,0.1

Type RM Length L Ch R = 1 ,178831  ,503.4,473.8,454.1
XS GIS Cut Line= 2
2318410.08786052650000.8675306592319174.22729806 649465.64750268
#Sta/Elev= 30
       0 3033.88    75.9 2986.17     111 2965.74   139.3 2952.59   215.6 2905.18
   256.9 2876.36   339.5 2812.14   349.3 2806.86   359.1 2804.29   414.8 2799.22
   417.7 2799.09   495.8 2799.09   536.3 2805.13   603.2  2805.2   622.8 2808.82
     636 2808.33   656.9 2804.02   671.6 2805.64   679.1 2810.69   705.8 2834.32
   736.5 2851.11   750.9 2863.23   793.9 2891.49   805.4 2891.99   836.1 2880.09
   857.1 2880.23   896.2 2920.15   901.1 2922.86   919.8 2926.02   932.9 2931.11
#Mann= 3 ,-1,0
       0      .1       0   414.8    .045       0   495.8      .1       0
Bank Sta=414.8,495.8
XS Rating Curve= 0 ,0
Exp/Cntr(USF)=0,0
Exp/Cntr=0.3,0.1

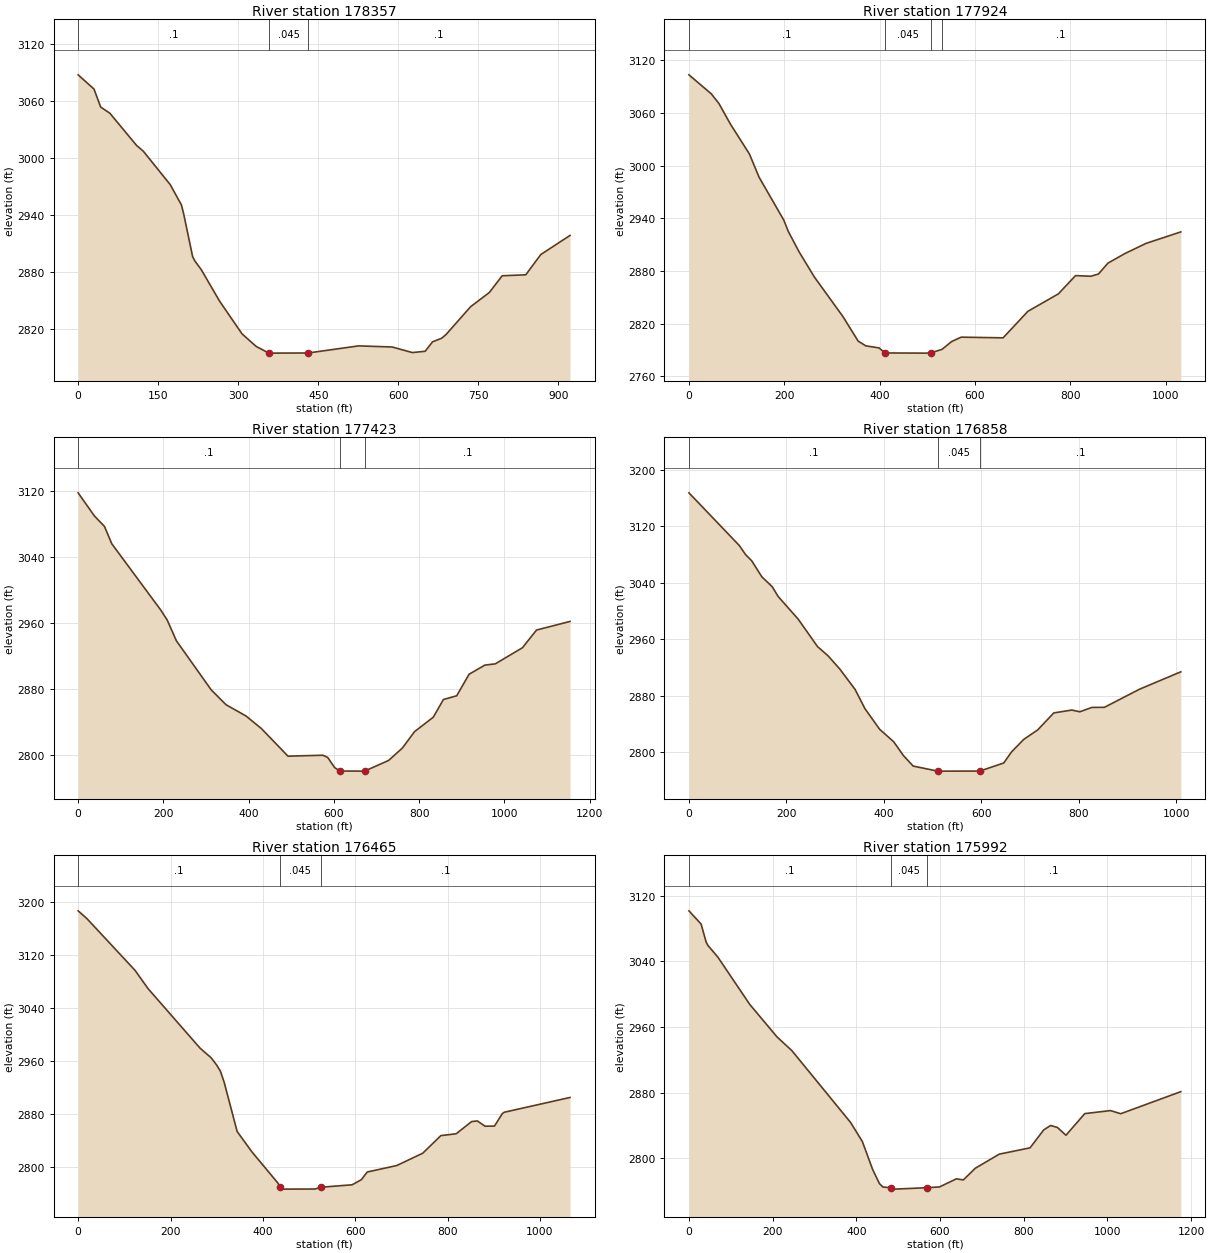
Type RM Length L Ch R = 1 ,178357  ,450.3,433.1,429.9
XS GIS Cut Line= 3
 2319025.9133144650397.4462260892319241.93585581649726.809082598
2319264.50537507649510.786541184
#Sta/Elev= 30
       0 3088.04    29.7 3073.09    42.3  3054.1    59.6 3047.55   109.5 3013.73
   122.2 3007.62   172.6 2972.44   193.6 2951.03   197.8 2941.64   214.6 2896.56
   218.8 2892.07   230.9  2882.8     265 2849.89   307.1 2815.38   333.5 2802.19
   357.5 2795.07   431.1 2795.22   525.6  2802.7   588.6 2801.52   626.4 2795.66
   650.4 2797.04   664.3 2807.01   681.1  2810.7   689.5 2814.67   735.3 2843.83
   770.6  2858.9   794.7 2876.52   838.9 2877.52   867.1 2898.89   921.8 2918.97
#Mann= 3 ,-1,0
       0      .1       0   357.5    .045       0   431.1      .1       0
Bank Sta=357.5,431.1
XS Rating Curve= 0 ,0
Exp/Cntr(USF)=0,0
Exp/Cntr=0.3,0.1

Type RM Length L Ch R = 1 ,177924  ,468.6,501,520.6
XS GIS Cut Line= 2
2319583.70286163650436.1368305222319574.03021052649404.387378996
#Sta/Elev= 30
       0 3103.25      47 3081.58      63 3070.52      87 3047.21     127 3013.07
     147 2986.86     199 2937.91   208.5 2925.01     231 2901.86     263  2873.3
     323 2828.21     355 2800.22     371 2794.84     399 2792.47     411 2786.76
   496.1 2786.56     507 2786.74     531 2790.89     551 2799.74     571 2804.74
     659 2803.96     711 2834.14     775    2854   810.9 2874.76     843 2874.04
     859 2876.57     879    2889     915    2900     959 2911.46  1031.8 2924.52
#Mann= 4 ,-1,0
       0      .1       0     411    .045       0     507    .025       0
     530      .1       0
Bank Sta=411,507
XS Rating Curve= 0 ,0
Exp/Cntr(USF)=0,0
Exp/Cntr=0.3,0.1

Type RM Length L Ch R = 1 ,177423  ,525.1,565.6,593.4
XS GIS Cut Line= 2
2319586.92707867650471.6032179182320425.22350803649678.445827057
#Sta/Elev= 30
       0 3118.23    38.4 3090.04    61.7 3077.54      79 3056.39   194.5 2975.54
   209.2 2963.63   230.5 2938.73     312 2879.27   346.9 2861.13   393.5 2847.54
   429.9  2832.2   492.4 2798.64   574.4 2799.79   585.5 2797.13   601.9 2784.81
   613.8 2780.62     667  2780.5   672.8 2780.67   728.6  2793.5   760.9 2808.57
   789.2 2828.36   833.2 2845.92   857.1 2867.42   888.2 2871.94   917.3 2898.08
   954.4 2909.17   978.8 2910.69  1042.5 2930.25  1075.5 2951.71  1154.1 2962.15
#Mann= 3 ,-1,0
       0      .1       0   613.8    .045       0   672.8      .1       0
Bank Sta=613.8,672.8
XS Rating Curve= 0 ,0
Exp/Cntr(USF)=0,0
Exp/Cntr=0.3,0.1

Type RM Length L Ch R = 1 ,176858  ,410,392.5,382.3
XS GIS Cut Line= 4
2319606.27238088650655.3835889712319996.40264224650523.190690494
2320383.30868656650613.4687675032320573.53749169650552.208643818
#Sta/Elev= 30
       0 3167.51   103.4 3092.78     116 3080.12   128.7 3071.22   149.8 3048.21
   170.9  3034.4     183  3020.6   224.1 2988.48   263.9 2949.45     285 2936.75
   309.2 2917.96   340.8 2888.86     361 2861.67   391.2 2832.31   419.9 2814.73
   440.4 2794.73     460 2780.15   510.3 2772.97   596.7 2773.03   645.8 2784.52
   662.2 2800.51   686.9 2817.98   715.6 2831.48   748.5 2855.48   785.5 2859.56
   801.9 2857.11   826.9 2863.35   852.2 2863.38   924.6 2889.15  1009.1 2913.75
#Mann= 3 ,-1,0
       0      .1       0   510.3    .045       0   596.7      .1       0
Bank Sta=510.3,596.7
XS Rating Curve= 0 ,0
Exp/Cntr(USF)=0,0
Exp/Cntr=0.3,0.1

Type RM Length L Ch R = 1 ,176465  ,480.1,473.4,469.8
XS GIS Cut Line= 3
2319577.25442756650984.2537266452320264.01265623 650922.99360296
2320625.12496427650819.818657808
#Sta/Elev= 30
       0 3187.02      19 3175.31   123.3 3097.14   151.5 3069.53     264 2979.83
   288.1 2965.25   299.7 2954.56   308.1    2945   316.2 2928.33   344.3 2854.06
   376.4  2823.2   432.6 2776.21  437.372769.757   440.7  2767.1   512.9 2767.25
     525 2769.92   593.3 2773.64   613.3 2781.39   625.9 2792.95   689.7 2802.65
   746.1 2821.28   785.3 2847.83   818.6 2850.66   851.9 2869.01   864.4 2869.99
     881 2862.05   901.4 2862.23   918.5 2881.14   922.6  2883.1    1065 2905.41
#Mann= 3 ,-1,0
       0      .1       0  437.37    .045       0     525      .1       0
Bank Sta=437.37,525
XS Rating Curve= 0 ,0
Exp/Cntr(USF)=0,0
Exp/Cntr=0.3,0.1

Type RM Length L Ch R = 1 ,175992  ,389.1,386.8,389.4
XS GIS Cut Line= 3
2319619.16924903651464.662065012 2320028.6448126651432.419894651
2320776.66316496651274.433259886
#Sta/Elev= 30
       0 3101.66    29.1 3085.49    41.1 3063.58    45.1 3059.64    69.2 3045.12
   145.5 2987.39   210.7 2947.72   245.8 2931.21   386.2 2843.54   414.4  2820.2
   438.9  2786.2   455.2 2768.89   463.4 2764.78   483.9 2763.76     492 2762.17
   568.3 2763.91   598.7 2764.85   639.2 2774.75   655.6 2773.39   684.2 2787.63
   741.4 2804.83     815 2812.53   847.7 2834.39   864.1 2839.81   880.4 2837.42
   900.9  2827.9   945.8 2854.29  1007.2    2858  1031.7 2854.14  1175.3 2881.08
#Mann= 3 ,-1,0
       0      .1       0   483.9    .045       0   568.3      .1       0
Bank Sta=483.9,568.3
XS Rating Curve= 0 ,0
Exp/Cntr(USF)=0,0
Exp/Cntr=0.3,0.1

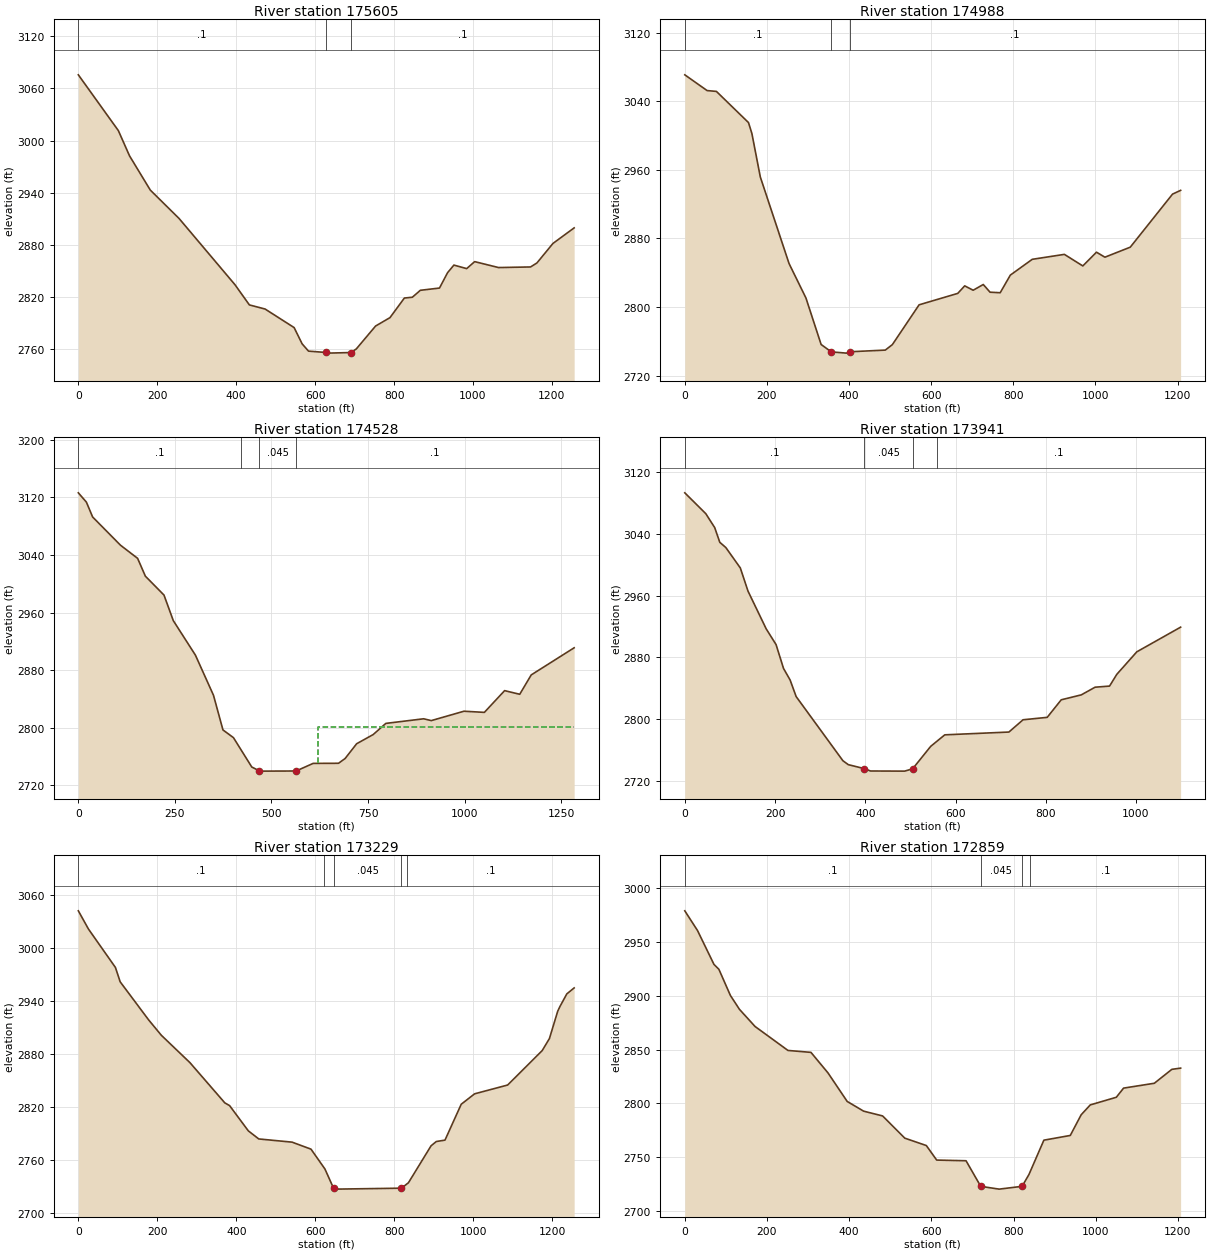
Type RM Length L Ch R = 1 ,175605  ,621,616.6,626.9
XS GIS Cut Line= 2
2319615.94503199651877.3618456222320857.26859086651683.908823461
#Sta/Elev= 30
       0 3075.64   101.4 3011.51   129.8 2982.41   182.4 2943.08   255.3 2910.43
     397 2834.25   433.4 2811.07   473.2 2806.34   546.8    2785     567 2766.33
   583.2 2757.93   627.7 2756.38   631.8 2755.63   690.6  2756.3   704.4  2760.5
   753.2  2786.8   789.6 2796.42   826.1 2818.98   846.3  2819.9   866.6 2827.87
   915.1 2830.46   935.5 2848.08   951.6 2856.86     984 2852.81  1004.2 2860.84
  1064.7 2854.03  1145.9 2854.71  1162.1 2859.38  1202.6 2881.76  1256.3 2899.65
#Mann= 3 ,-1,0
       0      .1       0   627.7    .045       0   690.6      .1       0
Bank Sta=627.7,690.6
XS Rating Curve= 0 ,0
Exp/Cntr(USF)=0,0
Exp/Cntr=0.3,0.1

Type RM Length L Ch R = 1 ,174988  ,480.2,460.7,452.6
XS GIS Cut Line= 3
2319729.32707083 652443.84275115 2320744.4209946652200.081449377
 2320903.2399721652161.241894869
#Sta/Elev= 30
       0 3071.03    54.3 3052.66      77 3051.66   155.1  3015.3   163.4 3002.54
   183.9 2951.81   253.9 2850.74     295 2810.57     332 2756.26   356.7 2747.63
   393.7 2746.17     402 2747.76   488.3 2749.71   505.5  2756.1   570.6 2802.56
   664.7  2815.9   681.7 2824.69   702.3 2819.58   726.9 2826.28   743.4 2817.28
   768.1 2816.67   792.8 2837.24   846.2 2855.68   924.4 2861.45   969.3 2847.95
  1002.6 2863.99  1023.1 2858.16  1084.9 2869.86  1187.8 2931.78  1207.5 2936.18
#Mann= 3 ,-1,0
       0      .1       0   356.7    .045       0     402      .1       0
Bank Sta=356.7,402
XS Rating Curve= 0 ,0
Exp/Cntr(USF)=0,0
Exp/Cntr=0.3,0.1

Type RM Length L Ch R = 1 ,174528  ,618.1,586.4,577.2
XS GIS Cut Line= 3
2320254.34000512653237.9814348222320215.64940069652838.178522355
 2320914.0428661652299.094680858
#Sta/Elev= 30
       0 3126.42    20.9  3113.5      37 3092.88   109.3 3053.59   153.5 3035.42
   173.6 3010.65   221.8  2984.4   245.9 2948.93   303.2 2900.96     350 2845.19
   374.5 2797.09   401.7 2786.35   449.1 2745.58   468.8 2740.24   473.1 2739.86
     564 2740.04   608.1 2750.62   673.7 2750.75   690.8 2757.38   720.7  2777.9
   763.4 2790.62   796.3 2806.16   894.3 2812.56   913.9 2810.03   998.6 2823.07
  1051.4 2821.47  1103.8 2851.66    1143 2846.61  1172.7 2873.48  1283.9 2911.18
#Mann= 4 ,-1,0
       0      .1       0  421.67    .025       0   468.8    .045       0
     564      .1       0
#XS Ineff= 2 , 0
                          621.66         2800.86
Permanent Ineff=
       F       F
Bank Sta=468.8,564
XS Rating Curve= 0 ,0
Exp/Cntr(USF)=0,0
Exp/Cntr=0.3,0.1

Type RM Length L Ch R = 1 ,173941  ,686.3,712,788.6
XS GIS Cut Line= 3
2320657.36713463653366.9501162622321053.94583006652554.447423186
2321057.51174342 652359.71520806
#Sta/Elev= 30
       0 3093.01    46.5 3066.05    66.2 3048.07    77.6 3028.91      91 3022.12
   123.1 2995.69     140 2965.86   180.3 2916.98   202.3 2896.47   218.8 2865.64
   233.4 2850.65   246.8 2829.17   350.4 2746.11   362.4    2741   398.1 2735.84
   411.5  2732.8   487.1 2732.63   504.9 2735.58     545 2764.72   576.2 2779.62
   718.3 2783.23   749.7 2799.13   803.2 2802.26   834.3 2824.98   878.8 2831.39
   909.4 2841.32   941.4 2842.76   957.4 2857.93  1001.8 2887.12  1098.9 2919.06
#Mann= 4 ,-1,0
       0      .1       0   398.1    .045       0   504.9    .025       0
     560      .1       0
Bank Sta=398.1,504.9
XS Rating Curve= 0 ,0
Exp/Cntr(USF)=0,0
Exp/Cntr=0.3,0.1

Type RM Length L Ch R = 1 ,173229  ,347.9,370.3,426.2
BEGIN DESCRIPTION:
Structure XS 4
END DESCRIPTION:
XS GIS Cut Line= 3
2320714.61449471 653480.822801512321105.53330263653512.039882883
2321889.01804239653150.927574849
#Sta/Elev= 30
       0 3041.64    25.6 3021.05    93.9 2977.58   105.9 2961.33   178.1 2918.13
   210.2 2900.78   282.5 2869.85   370.7 2824.36   382.8 2821.26   430.3 2792.64
   456.7 2783.52     541  2779.9   588.9 2771.97   624.1 2749.54   646.1 2727.64
   650.5 2726.74   817.9 2727.81   835.5 2733.96   892.8 2775.78     906 2780.61
     928 2782.19   969.1 2822.79  1002.9 2834.57  1086.6 2844.54  1174.1 2883.54
  1192.3 2897.14  1213.3 2928.05  1218.7 2933.18  1236.3 2947.64  1254.9 2954.42
#Mann= 5 ,-1,0
       0      .1       0  622.16    .025       0   646.1    .045       0
   817.9    .025       0  832.16      .1       0
Bank Sta=646.1,817.9
XS Rating Curve= 0 ,0
Exp/Cntr(USF)=0,0
Exp/Cntr=0.3,0.1

Type RM Length L Ch R = 1 ,172859  ,80.1,83,87.3
BEGIN DESCRIPTION:
Structure XS 3
END DESCRIPTION:
XS GIS Cut Line= 6
2320673.23411583653694.646214873 2321182.9145115653711.941339116
2321563.37212175653757.0803776212321660.09863283653802.219416125
2321698.78923726653840.9100205572321840.65478684653786.098330945
#Sta/Elev= 30
       0 2978.77      31 2960.46      71 2929.06      83  2924.5     111 2900.24
     133 2887.38     171 2871.45   251.1 2849.22     307 2847.44   348.4 2828.43
   395.2 2801.91   435.2  2792.9   481.4 2788.45   535.4 2767.85   587.8 2760.98
     613  2747.5   684.4 2746.88   720.2 2723.11     765 2720.55   820.8 2723.14
   837.5 2734.09   873.8 2765.97   938.1 2770.35   964.6 2789.55   986.7 2798.68
  1050.1 2805.78  1067.8 2814.27  1142.6 2818.77  1185.3  2831.7  1206.6 2832.82
#Mann= 4 ,-1,0
       0      .1       0   720.2    .045       0   820.8    .025       0
  839.97      .1       0
Bank Sta=720.2,820.8
XS Rating Curve= 0 ,0
Exp/Cntr(USF)=0,0
Exp/Cntr=0.3,0.1

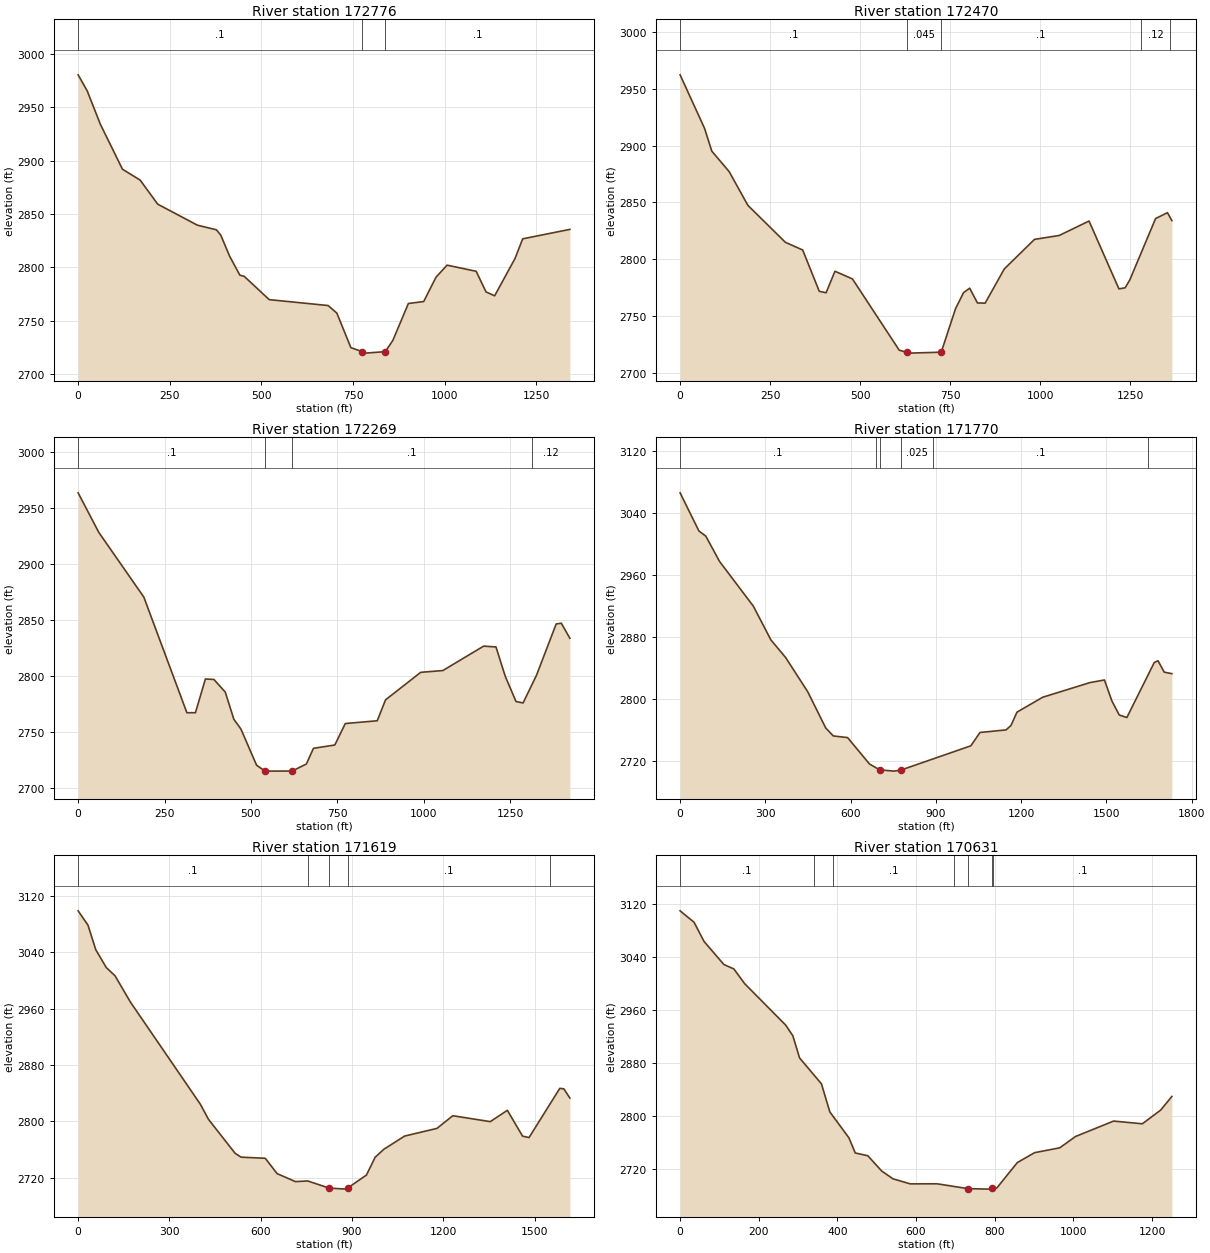
Type RM Length L Ch R = 1 ,172776  ,307.5,305.8,314.1
BEGIN DESCRIPTION:
Structure XS 2
END DESCRIPTION:
XS GIS Cut Line= 6
 2320619.4475152653797.6284137742320834.14997798653812.312718243
2321289.31367369653798.9951990892321515.00886621653837.685803521
2321663.32284986653950.5333997822321898.69069349653850.582671665
#Sta/Elev= 30
       0 2980.28    24.8 2965.23    60.9 2933.79     121 2891.87   169.3 2881.66
   217.2 2859.11   325.3 2839.46   377.3  2835.1   389.3 2830.05   413.3  2810.4
   441.3 2792.59   453.2  2791.5   521.4 2769.68   681.9 2764.18   705.9 2757.08
   744.2  2724.7   774.9 2721.04     783 2719.59   837.9 2720.97   858.5 2731.41
     901 2766.08   942.8  2767.9   976.4  2790.7  1006.6 2801.99  1085.9 2796.26
  1112.9 2776.93  1136.4 2773.28  1191.7 2808.07  1212.9 2826.64  1341.6 2835.52
#Mann= 3 ,-1,0
       0      .1       0   774.9    .045       0   837.9      .1       0
Bank Sta=774.9,837.9
XS Rating Curve= 0 ,0
Exp/Cntr(USF)=0,0
Exp/Cntr=0.3,0.1

Type RM Length L Ch R = 1 ,172470  ,208.2,200.8,198.2
BEGIN DESCRIPTION:
Structure XS 1
END DESCRIPTION:
XS GIS Cut Line= 4
 2320596.2997572653969.5370056692320957.21931898653950.533399782
2321415.05813809654147.2106389792321879.34539128653947.309182746
#Sta/Elev= 30
       0 2962.24      68 2915.07      88 2895.11   136.1 2877.14   188.1 2847.43
   292.3  2814.9   340.3 2808.14   386.4  2771.8   405.3 2770.52   429.9 2789.44
   478.4  2782.7   608.4 2719.96   629.1 2718.18   636.7 2717.41     725 2718.24
   764.6 2756.46   786.9 2770.61   803.9 2774.53   825.5 2761.55   846.8 2761.38
   900.1 2791.51   983.9 2817.48  1052.6 2820.93  1135.3 2833.63  1218.3 2773.92
  1235.5 2774.88  1248.5 2781.85    1320 2835.77    1353    2841  1365.2 2834.05
#Mann= 5 ,-1,0
       0      .1       0   629.1    .045       0     725      .1       0
 1279.71     .12       0 1359.71      .1       0
Bank Sta=629.1,725
XS Rating Curve= 0 ,0
Exp/Cntr(USF)=0,0
Exp/Cntr=0.3,0.1

Type RM Length L Ch R = 1 ,172269  ,566.7,499.8,420.8
BEGIN DESCRIPTION:
Structure XS 4
END DESCRIPTION:
XS GIS Cut Line= 4
2320589.65857687654289.0761885642320850.82015679654176.228592303
2321305.43475887654285.851971528 2321908.3633446 653992.44822125
#Sta/Elev= 30
       0 2963.45    59.6 2928.24   190.1 2870.34   314.7 2767.07   339.4 2767.09
   368.2 2797.19   392.9 2796.79   425.8 2785.47   450.5 2761.26   471.1 2752.46
   516.3 2720.21     541 2714.93   619.2    2715   660.3 2721.28   680.9 2735.31
   742.6 2738.25     773 2757.43   865.4  2759.9   889.4 2778.57   991.1 2803.15
  1055.3 2804.76  1173.3 2826.56  1208.9 2825.82  1235.6 2799.78  1266.8 2777.11
  1287.3  2775.8  1326.2 2800.57  1383.1 2846.36  1397.9 2847.05  1422.7 2833.56
#Mann= 4 ,-1,0
       0      .1       0     541    .045       0   619.2      .1       0
 1312.14     .12       0
Bank Sta=541,619.2
XS Rating Curve= 0 ,0
Exp/Cntr(USF)=0,0
Exp/Cntr=0.3,0.1

Type RM Length L Ch R = 1 ,171770  ,152,150.4,146.9
BEGIN DESCRIPTION:
Structure XS 3
END DESCRIPTION:
XS GIS Cut Line= 5
2321082.14998923655229.7205005492321090.99557781655209.817926253
2321382.90000082654783.0182774522321303.28970364 654300.93370005
2321944.59487541654013.452071324
#Sta/Elev= 30
       0  3065.8    66.2 3016.58    90.4    3010   138.9 2977.29   257.7 2919.68
   319.5 2876.15   371.5 2853.33     449 2809.35   512.3 2762.67   538.9 2752.33
   589.4 2750.16   666.4 2716.14   702.42708.566     752 2706.93   775.9 2708.15
    1023 2739.58  1055.2 2756.77  1146.8 2760.08  1164.2 2765.74  1185.3 2782.97
  1276.1 2802.25  1442.6 2821.14  1493.1 2824.46  1519.4  2797.4  1545.1 2779.37
    1572 2776.08  1668.4 2846.96  1681.6 2849.25  1703.5 2834.58  1730.3 2832.59
#Mann= 6 ,-1,0
       0      .1       0  688.85    .025       0   702.4    .045       0
   775.9    .025       0  888.85      .1       0 1647.47     .12       0
Bank Sta=702.4,775.9
XS Rating Curve= 0 ,0
Exp/Cntr(USF)=0,0
Exp/Cntr=0.3,0.1

Type RM Length L Ch R = 1 ,171619  ,924.3,988.3,1034.9
BEGIN DESCRIPTION:
Structure XS 2
END DESCRIPTION:
XS GIS Cut Line= 4
2321157.33749213655267.3142519982321533.27500662654732.156143139
2321449.24191514654342.9502457872321962.28605256654108.542148518
#Sta/Elev= 30
       0 3098.74    32.3 3078.52    58.1 3043.45    92.6 3018.23   121.3 3006.56
   171.9 2969.25   401.6 2824.39   428.5 2802.84   515.9 2754.72   535.4 2749.23
   615.2  2747.6     654  2725.8   714.3 2714.53     755 2715.42   824.8  2705.3
   882.1 2703.84   886.1 2705.43   947.6 2723.82   976.2 2749.06  1004.9 2760.43
    1073 2779.12  1179.5 2790.03  1231.3 2808.01  1354.5  2799.6  1410.8 2815.69
  1460.7 2779.02    1482 2777.03  1583.1 2846.82  1596.3 2846.13  1616.2 2833.14
#Mann= 5 ,-1,0
       0      .1       0  754.01    .025       0   824.8    .045       0
   886.1      .1       0 1552.18     .12       0
Bank Sta=824.8,886.1
XS Rating Curve= 0 ,0
Exp/Cntr(USF)=0,0
Exp/Cntr=0.3,0.1

Type RM Length L Ch R = 1 ,170631  ,492,469.3,452.1
BEGIN DESCRIPTION:
Structure XS 1
END DESCRIPTION:
XS GIS Cut Line= 4
2321396.16838369655435.3804349452321732.30074958655174.435571948
 2322355.9147442655187.7039548122322523.98092715 655077.13409761
#Sta/Elev= 30
       0 3109.28    35.5 3092.04    60.8 3063.16   111.4 3028.22   136.7 3021.58
   164.1 2999.41   268.4  2936.9   286.7 2920.78   303.8 2887.29   359.5 2848.16
   380.7 2805.89   429.4 2766.67   445.4 2743.86   477.4 2739.68   512.5  2716.7
   541.4 2704.88   585.4 2697.23   653.5 2697.37   732.82689.992   785.5 2689.31
   793.5 2690.38   805.5 2691.11   857.5 2729.34   901.5 2744.34   965.5 2751.66
  1005.5 2768.71  1102.3 2791.99  1175.5 2787.92    1222 2808.54  1250.5 2829.12
#Mann= 7 ,-1,0
       0      .1       0     340     .05       0     390      .1       0
  695.53    .025       0   732.8    .045       0   793.5    .025       0
  795.53      .1       0
Bank Sta=732.8,793.5
XS Rating Curve= 0 ,0
Exp/Cntr(USF)=0,0
Exp/Cntr=0.3,0.1

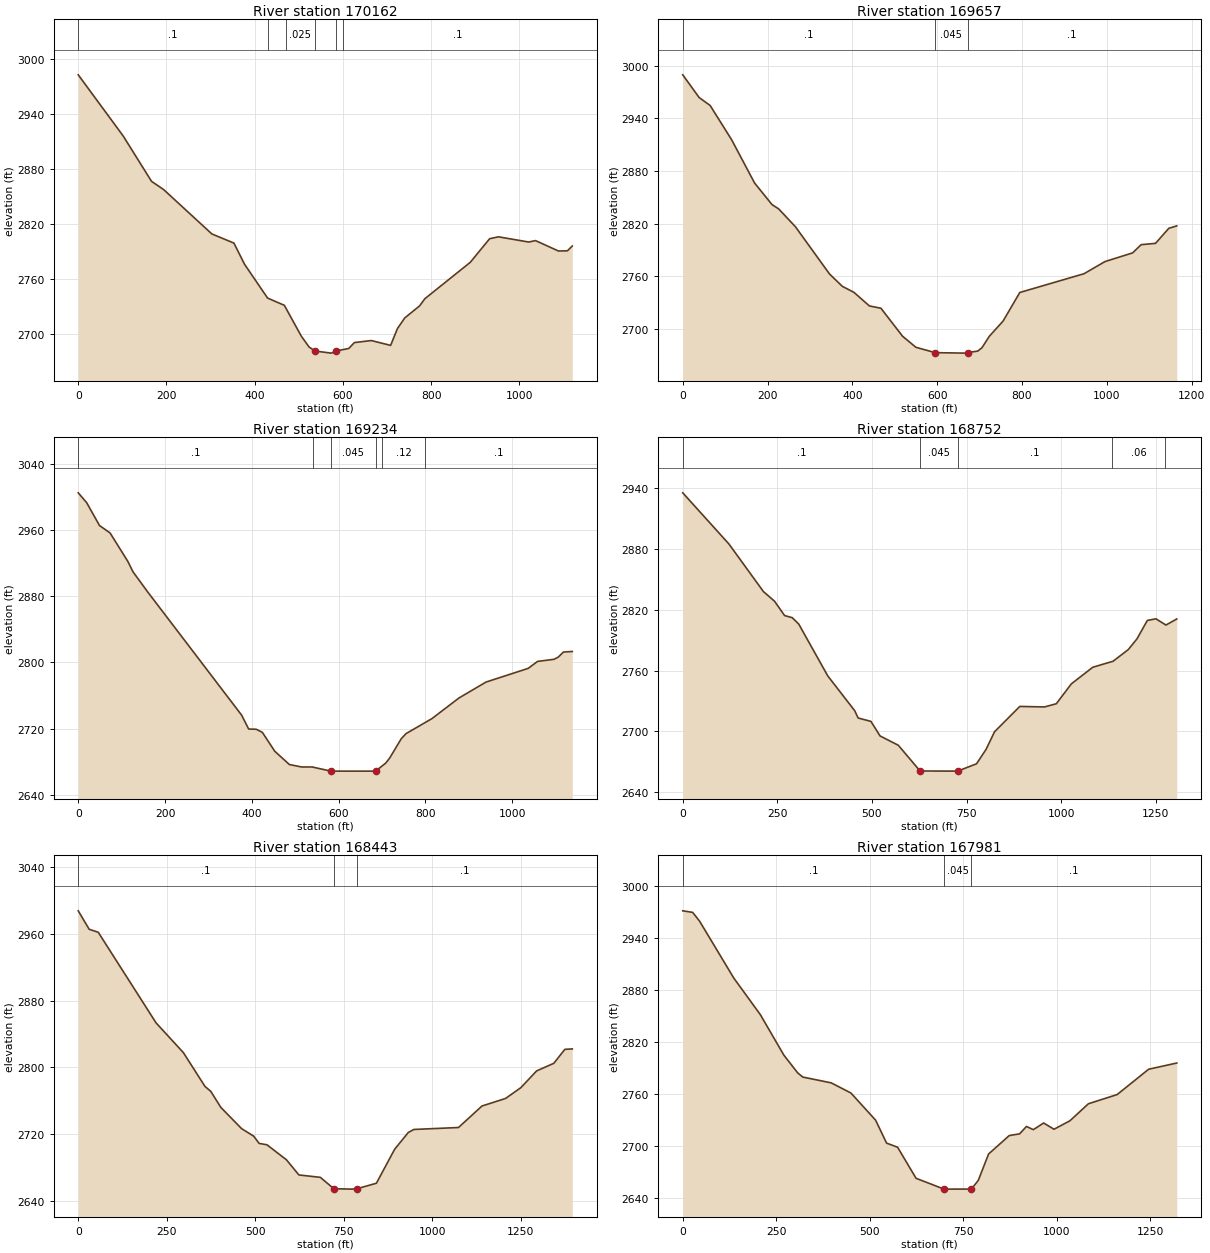
Type RM Length L Ch R = 1 ,170162  ,505,504.6,503.3
XS GIS Cut Line= 2
2321758.83751531656014.7664866852322577.05445861655249.623074846
#Sta/Elev= 30
       0 2982.41   101.9 2915.69   166.1 2866.23   193.5 2857.28     303  2808.8
     353 2798.82   377.1 2775.72   429.4  2738.8   467.3 2730.95   505.8 2697.28
   523.5 2685.39   536.9 2681.07   573.7 2678.76   585.1 2681.17   613.4 2683.84
   626.1 2690.25   664.5  2692.5   708.3 2687.21   723.7 2705.49   740.2 2717.06
     774 2730.32     786 2738.15     889 2777.88   932.8 2803.59     953 2805.65
  1021.3 2799.98  1036.9 2801.53  1088.8 2790.19  1109.2 2790.39  1120.2 2795.67
#Mann= 6 ,-1,0
       0      .1       0     430     .05       0     470    .025       0
   536.9    .045       0   585.1    .025       0     600      .1       0
Bank Sta=536.9,585.1
XS Rating Curve= 0 ,0
Exp/Cntr(USF)=0,0
Exp/Cntr=0.3,0.1

Type RM Length L Ch R = 1 ,169657  ,419.5,422.8,426.7
XS GIS Cut Line= 2
2322183.42576697656390.7040011732322930.87800165655497.299554979
#Sta/Elev= 30
       0 2989.77    38.5 2963.94    64.6 2954.78   115.2 2915.72   169.5 2866.19
   210.6  2841.6   226.2 2836.73   265.7 2816.35   346.2 2762.34   376.4 2748.28
   403.6 2741.48   440.1 2725.96   467.3 2723.31   518.4  2691.3   549.7 2678.77
   595.1 2672.62   666.1 2672.08   671.8 2672.62   695.6 2674.43   705.6  2678.3
   722.9 2691.34   755.4 2708.77   794.7 2741.31     946  2762.7   995.8 2776.64
  1060.8 2786.52  1080.7 2795.87  1114.7  2797.4    1146 2814.55  1164.8 2817.35
#Mann= 3 ,-1,0
       0      .1       0   595.1    .045       0   671.8      .1       0
Bank Sta=595.1,671.8
XS Rating Curve= 0 ,0
Exp/Cntr(USF)=0,0
Exp/Cntr=0.3,0.1

Type RM Length L Ch R = 1 ,169234  ,467.5,482.5,491.4
XS GIS Cut Line= 2
2322515.13533857656607.4209212892323282.01161637655766.074454814
#Sta/Elev= 30
       0 3004.63    19.4 2992.78      49 2965.18    73.4  2956.2   114.4 2921.79
   126.2 2909.34     160 2885.11   376.5 2736.41   392.7 2719.67   410.1 2719.41
   424.2  2715.7   452.8 2692.91   486.5 2676.86   514.8 2673.87   538.9 2673.92
   582.1 2668.89     685 2668.89   708.2 2678.41   717.5 2684.55   744.5 2708.09
   755.3 2714.12     815 2732.23   877.2 2757.09   939.5  2776.3  1036.8 2792.86
  1058.4 2801.24  1096.3  2803.8    1106 2806.41    1118 2812.56  1138.4 2813.23
#Mann= 6 ,-1,0
       0      .1       0     540    .025       0   582.1    .045       0
     685      .1       0     700     .12       0     800      .1       0
Bank Sta=582.1,685
XS Rating Curve= 0 ,0
Exp/Cntr(USF)=0,0
Exp/Cntr=0.3,0.1

Type RM Length L Ch R = 1 ,168752  ,297.1,308.4,311.8
XS GIS Cut Line= 4
2322656.66475579656775.487104237 2323063.5618303656625.112098442
2323527.95523055656311.093703987 2323745.6877024656088.759109289
#Sta/Elev= 30
       0 2935.17     122 2884.78   213.1 2837.89   242.5 2828.38   269.2 2814.17
   289.5 2812.09   306.6 2805.79   383.3  2754.7   454.4 2720.44   463.5 2713.22
   497.3 2709.88   521.5 2695.51   569.7 2686.35   627.2 2660.98   726.5 2660.84
   776.4 2668.07   801.5  2682.2     824 2699.64   890.7 2724.61     956 2724.11
   987.3 2727.27    1027 2746.87  1083.6 2763.24  1137.3 2769.17  1177.6 2780.69
  1200.5 2791.25  1227.8 2809.38  1250.5 2810.98    1277 2804.83  1305.6 2810.84
#Mann= 5 ,-1,0
       0      .1       0   627.2    .045       0   726.5      .1       0
 1134.39     .06       0 1274.39      .1       0
Bank Sta=627.2,726.5
XS Rating Curve= 0 ,0
Exp/Cntr(USF)=0,0
Exp/Cntr=0.3,0.1

Type RM Length L Ch R = 1 ,168443  ,465.4,462.3,454.3
XS GIS Cut Line= 2
 2322727.4294644657018.740790082 2324027.7309851656510.119446951
#Sta/Elev= 30
       0 2987.44    30.9 2965.37    56.6 2961.74   219.9 2853.36   297.2 2817.71
   358.3 2777.22   374.5 2771.46   403.1 2752.13   461.8 2726.73   495.8 2717.79
   511.2 2709.12   533.4 2707.43   588.4 2689.52   623.6 2671.34   684.1  2668.5
   722.4 2654.84   773.9 2654.38   786.8 2654.75   842.6 2661.42   894.2 2702.09
   932.8 2722.19   948.6 2725.79  1074.6 2728.12    1141 2753.84  1207.7  2762.9
  1250.7 2775.75  1295.4 2795.85  1343.9 2804.93  1375.2 2821.67  1396.2 2822.19
#Mann= 3 ,-1,0
       0      .1       0   722.4    .045       0   786.8      .1       0
Bank Sta=722.4,786.8
XS Rating Curve= 0 ,0
Exp/Cntr(USF)=0,0
Exp/Cntr=0.3,0.1

Type RM Length L Ch R = 1 ,167981  ,528.5,508.4,486.1
XS GIS Cut Line= 2
2322921.18180269657545.1378017962324069.57759863656893.116458066
#Sta/Elev= 30
       0 2971.23    26.4 2969.47    44.8 2959.44   136.8 2893.42   207.5 2851.39
   270.2 2804.79     307 2784.37   320.8 2779.42   396.9 2772.71   449.6 2760.99
   515.6 2729.66   544.9 2703.19   574.3 2698.44   623.7 2662.58     698 2650.18
   702.6 2650.09   771.6 2650.16     790 2660.18   817.6 2690.65   872.8  2711.9
   900.4 2713.87   918.8 2722.41   937.2 2718.71   964.8 2726.41   992.4 2719.19
  1034.9 2728.93  1084.4  2748.6  1161.1 2759.18  1245.4 2788.43  1320.6  2795.6
#Mann= 3 ,-1,0
       0      .1       0     698    .045       0   771.6      .1       0
Bank Sta=698,771.6
XS Rating Curve= 0 ,0
Exp/Cntr(USF)=0,0
Exp/Cntr=0.3,0.1