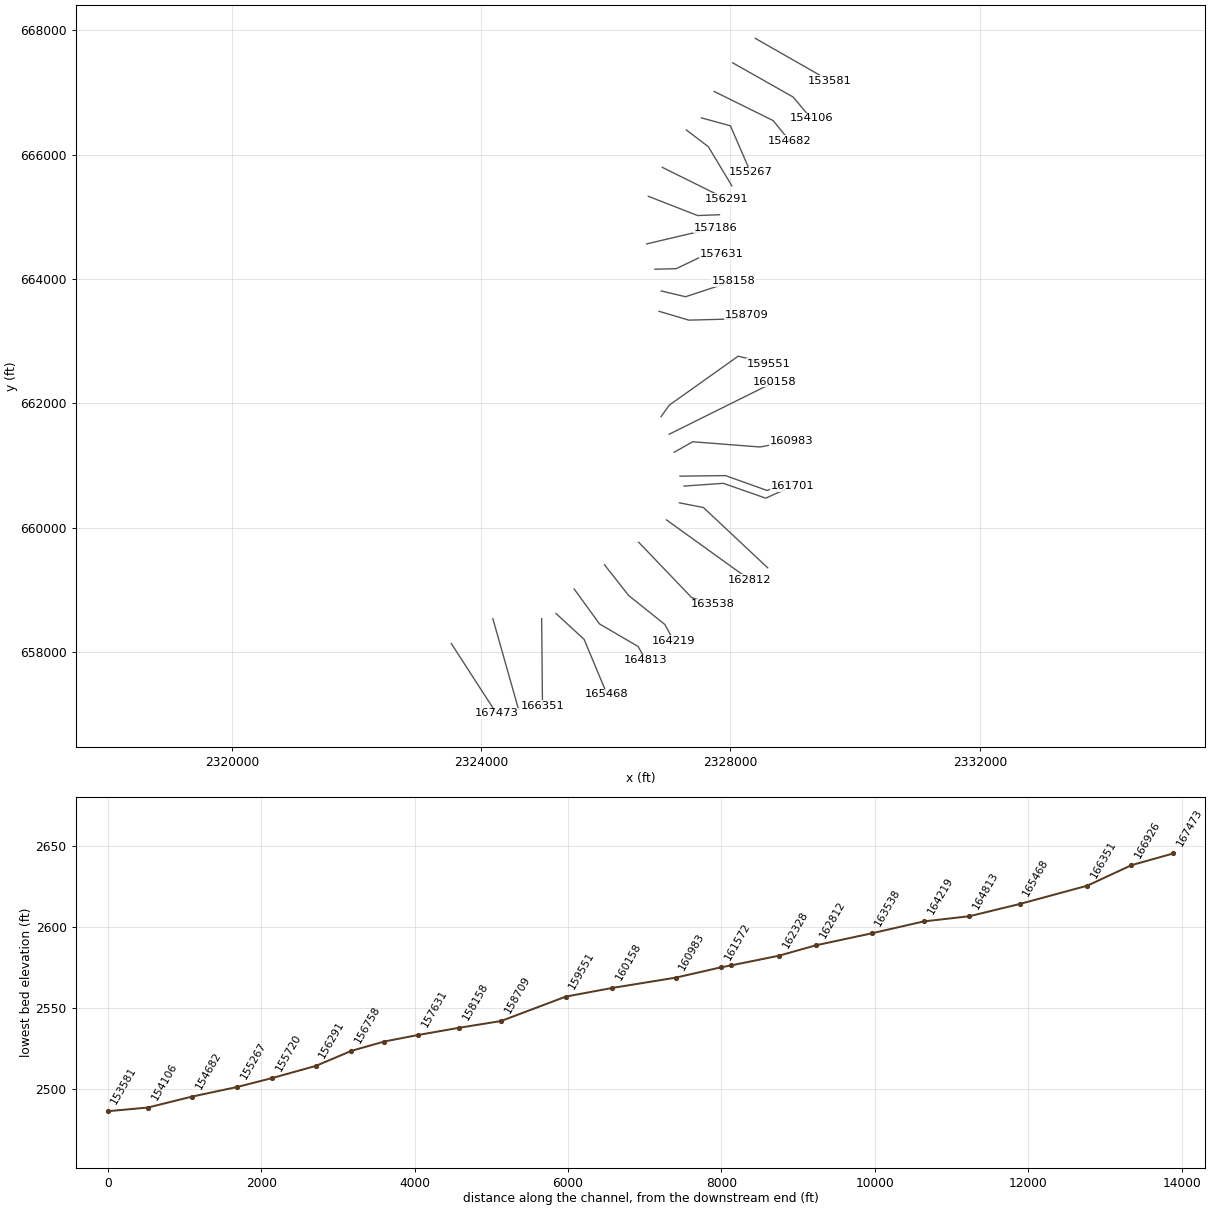
HEC-RAS study SHAVERSFK.prj: SHAVERSFK

--- SHAVERSFK.g01 (geometry) --- (continued)

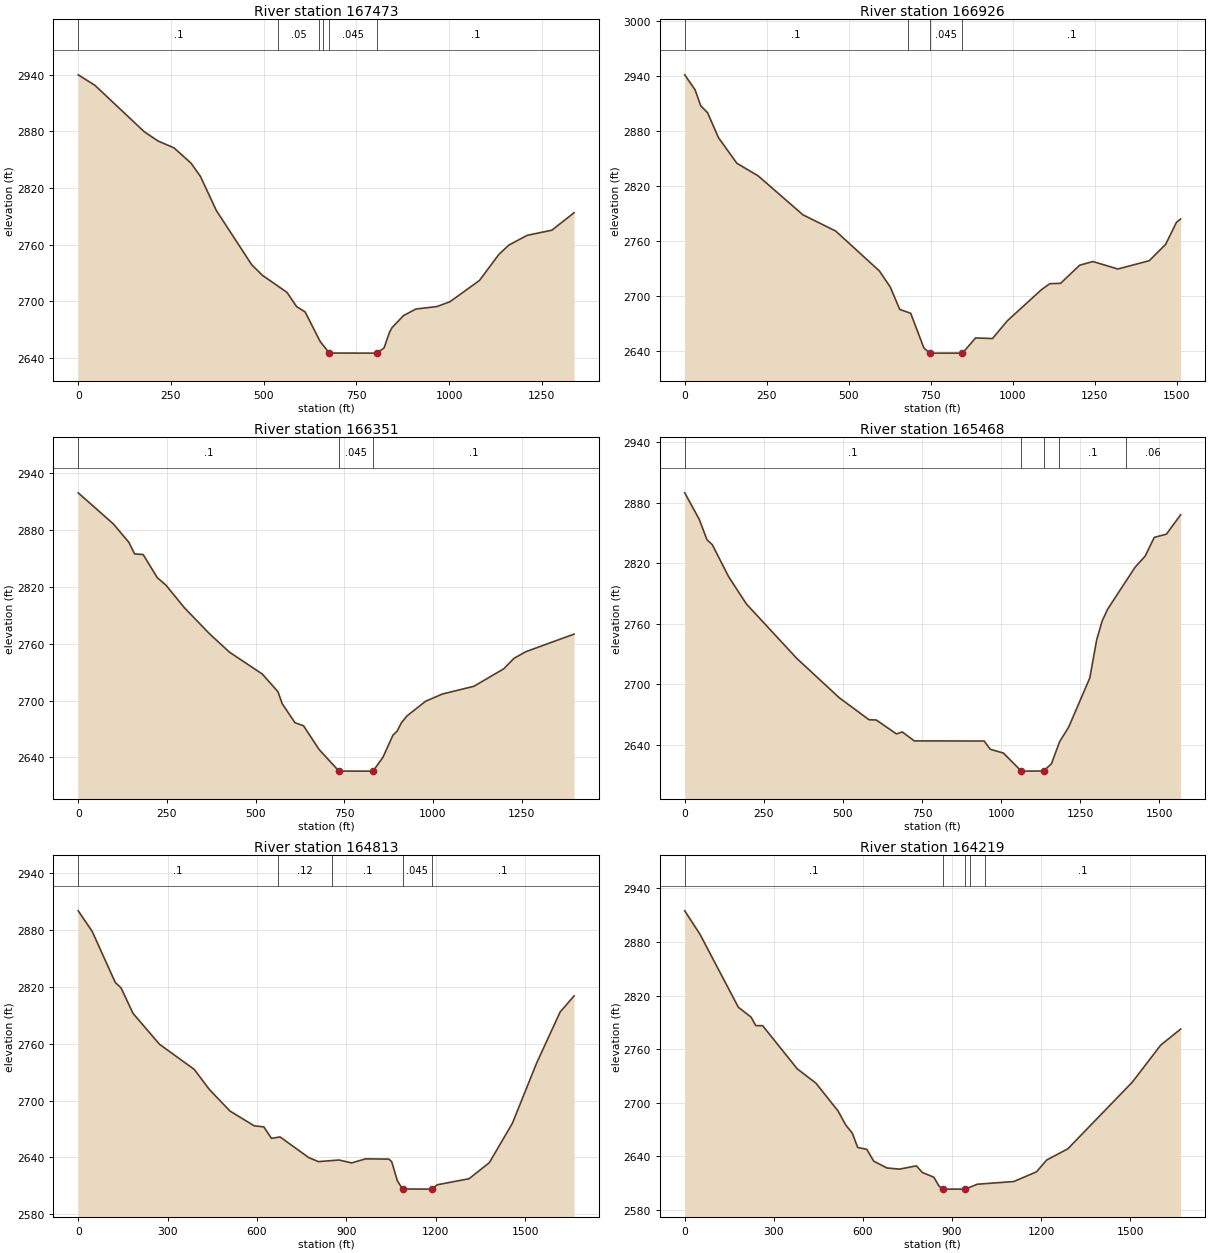
Type RM Length L Ch R = 1 ,167473  ,563.3,547.1,531.2
XS GIS Cut Line= 2
2323519.10964197658142.1305392572324244.44790522657018.740790082
#Sta/Elev= 30
       0 2939.69    44.9 2928.67   177.9 2879.57   215.4 2869.64   258.2 2862.47
   304.3 2846.22   329.7 2832.17   372.5 2796.16   467.7 2738.89   496.3 2727.75
     563 2709.55   588.8 2694.57   611.9 2688.84   652.4 2657.65   677.2 2645.37
   788.4 2645.28   805.8 2645.28   824.8 2650.84   839.1 2667.05   846.3 2672.29
   877.2 2684.99   910.5 2691.91   967.7 2694.59  1002.5 2699.67    1082 2722.13
  1134.3 2749.68  1161.7 2759.68  1210.8 2769.91  1277.2 2775.32  1337.2 2793.82
#Mann= 6 ,-1,0
       0      .1       0     540     .05       0     650      .1       0
     660     .05       0   677.2    .045       0   805.8      .1       0
Bank Sta=677.2,805.8
XS Rating Curve= 0 ,0
Exp/Cntr(USF)=0,0
Exp/Cntr=0.3,0.1

Type RM Length L Ch R = 1 ,166926  ,589.4,574.3,562.7
XS GIS Cut Line= 2
2324186.95157947658540.1820251852324598.27144826657085.082704403
#Sta/Elev= 30
       0 2941.31    31.6 2924.97    48.8 2907.57    69.6 2900.06   102.9 2872.86
     159 2844.93   223.8 2831.23   360.6 2788.72   460.4 2771.06   593.4 2727.64
   626.6 2710.17   655.7 2685.65     689 2681.46   729.3  2643.6   747.2 2638.16
   754.5 2638.03   846.9 2638.04   886.8 2654.56   938.4 2653.94   984.1 2673.42
    1088 2707.25    1113 2713.67  1146.2 2714.13  1204.4 2733.86  1244.6 2737.85
  1320.8 2729.71  1416.4 2738.75  1466.3 2756.49  1499.5 2780.58  1512.1 2784.18
#Mann= 4 ,-1,0
       0      .1       0     680    .025       0   747.2    .045       0
   846.9      .1       0
Bank Sta=747.2,846.9
XS Rating Curve= 0 ,0
Exp/Cntr(USF)=0,0
Exp/Cntr=0.3,0.1

Type RM Length L Ch R = 1 ,166351  ,868.4,883.2,894.1
XS GIS Cut Line= 2
2324969.78616846658540.1820251852324983.05455133657142.579030148
#Sta/Elev= 30
       0 2919.33      99 2886.55     143 2866.97     159 2854.81     183  2854.2
   222.7  2829.8     247 2821.96     299  2798.1     371 2770.12     427 2750.88
     519 2727.94     563 2709.32     575 2696.63     611 2676.53     635 2673.36
     679 2648.26     735 2625.43     831 2625.41     859  2640.1     887 2663.28
     899  2667.7     911 2676.53     927 2683.81     979 2699.16  1026.4 2706.84
  1115.3 2715.02  1199.1  2733.4  1228.3 2744.54  1261.5 2751.52  1397.7 2770.15
#Mann= 3 ,-1,0
       0      .1       0     735    .045       0     831      .1       0
Bank Sta=735,831
XS Rating Curve= 0 ,0
Exp/Cntr(USF)=0,0
Exp/Cntr=0.3,0.1

Type RM Length L Ch R = 1 ,165468  ,632.7,655.1,683.2
XS GIS Cut Line= 3
2325199.77147144658624.2151166592325650.89648883658208.472453578
2326017.98841474657328.336390248
#Sta/Elev= 30
       0 2889.67    45.8 2863.45    70.4 2843.12    87.1 2838.36   138.3 2806.87
   194.9  2779.6   354.1 2725.74   488.5 2686.71   582.7 2664.94   605.4 2664.72
   669.1 2650.94   687.3 2652.91   725.4 2644.04   946.4 2643.89   965.6 2635.73
  1007.1    2632  1063.6 2614.09  1133.8 2614.21  1158.8 2621.34  1184.8  2643.3
  1213.4 2657.71  1280.1 2706.41    1302 2744.33  1319.2 2762.86  1336.5 2774.48
  1423.2 2816.03    1455 2826.98  1483.8 2845.55  1522.3 2848.76  1567.1 2867.93
#Mann= 5 ,-1,0
       0      .1       0  1063.6    .045       0  1133.8    .025       0
 1183.48      .1       0 1393.48     .06       0
Bank Sta=1063.6,1133.8
XS Rating Curve= 0 ,0
Exp/Cntr(USF)=0,0
Exp/Cntr=0.3,0.1

Type RM Length L Ch R = 1 ,164813  ,599.1,593.6,588.9
XS GIS Cut Line= 4
2325491.67589446659017.8438082992325898.57296896658456.148933711
 2326517.7641693658093.4798020882326641.60240936657872.340087683
#Sta/Elev= 30
       0 2900.04    46.7  2878.5   124.3  2824.6   144.1 2818.65   184.1 2791.86
   272.9 2759.32   389.5 2732.83   440.4 2711.59   509.6 2688.87   590.9 2673.29
   623.2 2672.19   648.6  2660.1   677.5  2661.6   774.3 2639.72   806.7 2635.55
   875.3 2637.26     918  2634.2   964.3 2638.47  1043.1  2638.2  1052.4 2635.45
  1071.4 2615.38  1088.7 2606.68  1186.8 2606.55  1205.4 2611.14    1312 2617.53
  1380.1 2634.46  1457.4 2675.96  1538.9 2739.55  1617.8 2793.37  1664.6 2810.38
#Mann= 5 ,-1,0
       0      .1       0     670     .12       0  853.59      .1       0
  1088.7    .045       0  1186.8      .1       0
Bank Sta=1088.7,1186.8
XS Rating Curve= 0 ,0
Exp/Cntr(USF)=0,0
Exp/Cntr=0.3,0.1

Type RM Length L Ch R = 1 ,164219  ,687,681.8,684.1
XS GIS Cut Line= 4
2325978.18326615659407.049705651 2326367.3891635658911.696745385
2326946.77521524658447.3033451352327088.30463246658186.358482138
#Sta/Elev= 30
       0 2914.91    51.2 2888.76   180.4 2807.02   223.4 2795.88   239.2  2786.4
   262.2 2786.38   378.7 2738.05   441.5 2722.06   516.2 2690.87   541.6 2675.35
   563.9 2666.13   582.3 2650.01   612.8 2647.94   636.1 2634.74   680.7 2627.05
   723.2 2625.79   779.6 2629.44   800.1 2622.01   838.7  2616.7   856.5 2606.56
   870.6 2603.42   943.7 2603.38   985.2 2608.89  1107.7 2611.88    1184 2622.71
  1218.5 2635.99  1289.6  2648.5  1506.9 2723.23  1602.4 2764.64  1669.3 2782.51
#Mann= 5 ,-1,0
       0      .1       0   870.6    .045       0   943.7      .1       0
  959.96    .025       0 1009.96      .1       0
Bank Sta=870.6,943.7
XS Rating Curve= 0 ,0
Exp/Cntr(USF)=0,0
Exp/Cntr=0.3,0.1

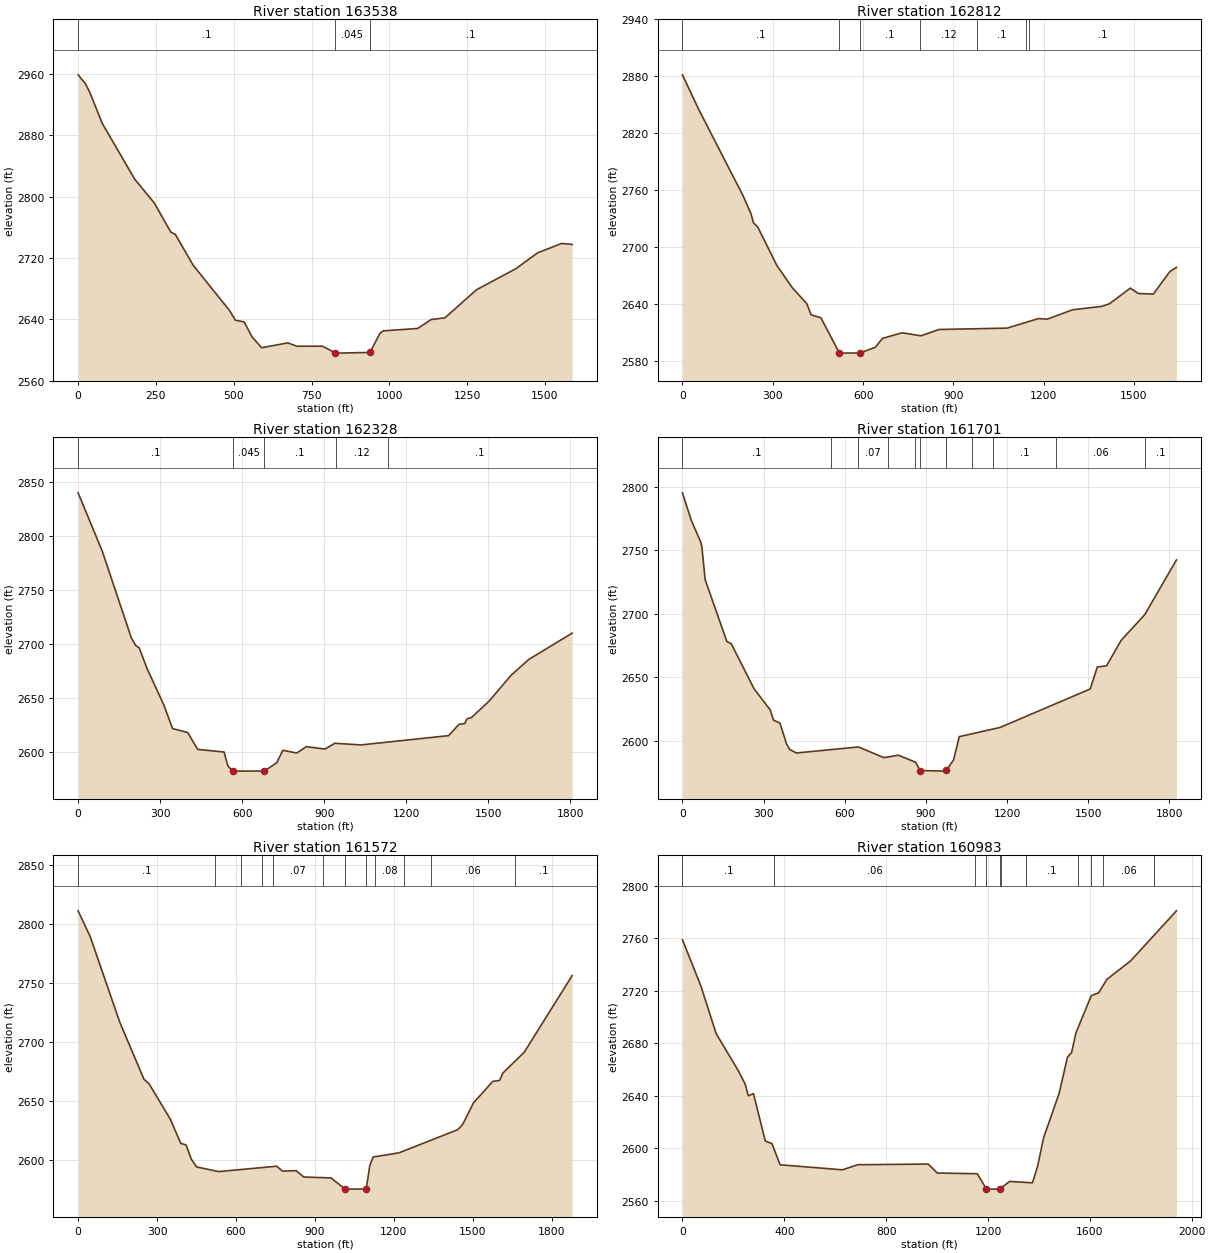
Type RM Length L Ch R = 1 ,163538  ,716.3,725.6,746.7
XS GIS Cut Line= 3
2326526.60975787659769.7188372742327375.78626119658880.737185368
2327716.34142137658770.167328166
#Sta/Elev= 30
       0 2959.06    22.9 2947.79      37 2936.84    77.5 2895.74   181.8 2822.96
   244.8 2791.89   297.6 2754.09   312.7 2750.79   369.3 2710.89   487.5 2651.14
   505.1 2638.96   533.4 2636.77   559.4 2616.95     590 2603.05     674 2609.37
     703 2604.97   785.2 2605.05     825 2596.69   830.4    2596   937.9  2596.9
   969.1 2621.21   979.9 2625.03    1091 2628.18  1134.7 2639.86  1178.4 2641.99
  1280.1 2678.63  1406.4 2706.09    1477 2726.95  1553.6 2739.05  1587.4 2737.85
#Mann= 3 ,-1,0
       0      .1       0     825    .045       0   937.9      .1       0
Bank Sta=825,937.9
XS Rating Curve= 0 ,0
Exp/Cntr(USF)=0,0
Exp/Cntr=0.3,0.1

Type RM Length L Ch R = 1 ,162812  ,487.9,483.6,477.6
XS GIS Cut Line= 2
2326973.31198097 660127.965174612328304.57306168659168.218814094
#Sta/Elev= 30
       0 2881.44    52.8 2845.81   200.8 2754.56   227.5 2735.43   236.1  2725.7
   250.1 2721.33   313.5 2680.96   365.1 2657.33   412.8  2640.8   427.6 2628.91
   459.8 2625.87   521.3 2588.83   526.2 2588.63   590.3 2588.83   640.9 2594.83
   664.3 2604.12   729.8 2610.04   792.5 2606.86   852.2 2613.51  1078.5 2614.94
  1182.1 2624.93  1211.7 2624.36  1295.5 2634.18  1394.1 2637.86  1418.8 2640.62
  1487.8 2657.03  1514.1 2651.39  1564.3 2650.72    1619 2674.38  1641.1 2678.85
#Mann= 7 ,-1,0
       0      .1       0   521.3    .045       0   590.3      .1       0
     790     .12       0     980      .1       0    1140     .12       0
    1150      .1       0
Bank Sta=521.3,590.3
XS Rating Curve= 0 ,0
Exp/Cntr(USF)=0,0
Exp/Cntr=0.3,0.1

Type RM Length L Ch R = 1 ,162328  ,603.6,626.9,642.4
BEGIN DESCRIPTION:
Structure XS 4
END DESCRIPTION:
XS GIS Cut Line= 3
2327181.18331251660402.1784204712327565.96641557660326.990917574
 2328596.4774847659358.398968482
#Sta/Elev= 30
       0 2840.23    88.6 2785.94   194.3 2705.96   210.9 2698.53   223.1 2696.64
   251.7 2677.54   312.8 2643.91   345.4 2621.67   400.6    2618   437.4 2602.34
   533.6 2599.95   547.7 2587.02   564.7  2582.2   680.9 2582.28     726 2589.93
   748.6 2601.51   799.6 2598.97   834.3 2604.87   902.8 2602.67   938.6 2608.02
  1034.4  2606.5  1354.2 2615.09  1393.4 2625.68  1413.6 2626.31  1422.1  2630.7
  1438.1 2631.86    1504 2647.43  1583.4 2671.17  1648.5 2685.88  1806.3 2710.11
#Mann= 5 ,-1,0
       0      .1       0   564.7    .045       0   680.9      .1       0
  942.06     .12       0 1132.06      .1       0
Bank Sta=564.7,680.9
XS Rating Curve= 0 ,0
Exp/Cntr(USF)=0,0
Exp/Cntr=0.3,0.1

Type RM Length L Ch R = 1 ,161701  ,131,128.9,127.8
BEGIN DESCRIPTION:
Structure XS 3
END DESCRIPTION:
XS GIS Cut Line= 4
2327256.37081541660671.9688720452327884.40760432660716.196814926
2328565.51792468660477.3659233692328998.95176492660671.968872045
#Sta/Elev= 30
       0  2795.2    31.9 2774.03      68 2756.19      72 2752.43      84 2726.86
   164.2 2678.19   180.2  2676.5   264.5 2641.12   324.6  2624.3   336.6 2616.35
   360.7 2613.97   384.8 2597.63   396.8 2593.27   420.8 2590.48   650.4 2595.22
   744.8 2586.83   798.9  2588.7   862.5 2583.13   878.9 2576.66   968.4  2576.2
  976.172576.811  1002.4 2585.04  1023.6 2603.34  1174.7 2610.59  1507.6 2640.84
    1534 2658.17  1568.1 2659.06  1621.7 2679.05  1709.4 2699.37  1826.5 2742.43
#Mann= 11 ,-1,0
       0      .1       0     550     .06       0  649.59     .07       0
  759.59     .06       0  859.59     .07       0   878.9    .045       0
  976.17      .1       0 1069.59     .08       0 1149.59      .1       0
 1381.36     .06       0 1711.36      .1       0
Bank Sta=878.9,976.17
XS Rating Curve= 0 ,0
Exp/Cntr(USF)=0,0
Exp/Cntr=0.3,0.1

Type RM Length L Ch R = 1 ,161572  ,578.1,589,599.7
BEGIN DESCRIPTION:
Structure XS 2
END DESCRIPTION:
XS GIS Cut Line= 4
2327190.02890109660831.1894664162327919.78995862660840.035054992
2328587.63189612660601.2041634352328998.95176491660751.579169231
#Sta/Elev= 30
       0 2811.04    46.1 2789.11   158.2 2716.66   250.2 2668.23   270.2 2664.15
   350.2 2634.41   390.2 2613.81   410.2 2612.56   430.2 2600.39   450.2 2593.86
   534.2 2589.91   754.3 2594.47     777 2590.29   827.9 2590.71   857.7 2585.31
   960.8 2584.55  1014.8 2575.04  1015.82575.042  1094.7 2575.16  1108.3 2595.02
    1121 2602.27  1218.8 2605.79  1442.6 2625.46  1461.3 2629.94  1501.9 2648.07
  1575.9 2666.46  1601.5 2667.23  1614.1 2673.55  1695.2 2691.12    1877 2756.05
#Mann= 12 ,-1,0
       0      .1       0     520     .06       0     620     .07       0
     700     .06       0  739.81     .07       0  929.81     .06       0
  1015.8    .045       0  1094.7     .07       0 1129.81     .08       0
 1239.81     .07       0 1339.81     .06       0 1659.08      .1       0
Bank Sta=1015.8,1094.7
XS Rating Curve= 0 ,0
Exp/Cntr(USF)=0,0
Exp/Cntr=0.3,0.1

Type RM Length L Ch R = 1 ,160983  ,807.6,825.1,849.4
BEGIN DESCRIPTION:
Structure XS 1
END DESCRIPTION:
XS GIS Cut Line= 4
2327097.15022104 661215.972569482327393.47743834661384.038752428
2328472.63924463661300.0056609542328981.26058776661392.884341004
#Sta/Elev= 30
       0 2758.81    72.5 2723.52   132.2 2687.31   219.6 2658.92   246.7 2648.57
   258.4  2639.8   278.9 2641.54   325.4 2605.32   351.4 2603.42   383.5 2587.25
   628.2  2583.4   688.4 2587.28   965.3 2587.79    1001 2580.96  1157.8 2580.42
  1193.9 2568.76  1246.1 2568.68  1284.6 2574.56  1374.5 2573.49  1394.5 2585.86
  1418.6 2607.98  1479.6 2641.83  1512.1 2669.35  1528.3 2672.81  1545.4 2687.84
  1605.6 2716.17    1635 2718.43  1666.6 2728.55  1760.1  2742.7  1940.1 2780.86
#Mann= 11 ,-1,0
       0      .1       0  360.67     .06       0 1150.67      .1       0
  1193.9    .045       0  1246.1      .1       0 1250.67    .025       0
 1350.67      .1       0  1553.1     .06       0  1603.1      .1       0
  1653.1     .06       0  1853.1      .1       0
Bank Sta=1193.9,1246.1
XS Rating Curve= 0 ,0
Exp/Cntr(USF)=0,0
Exp/Cntr=0.3,0.1

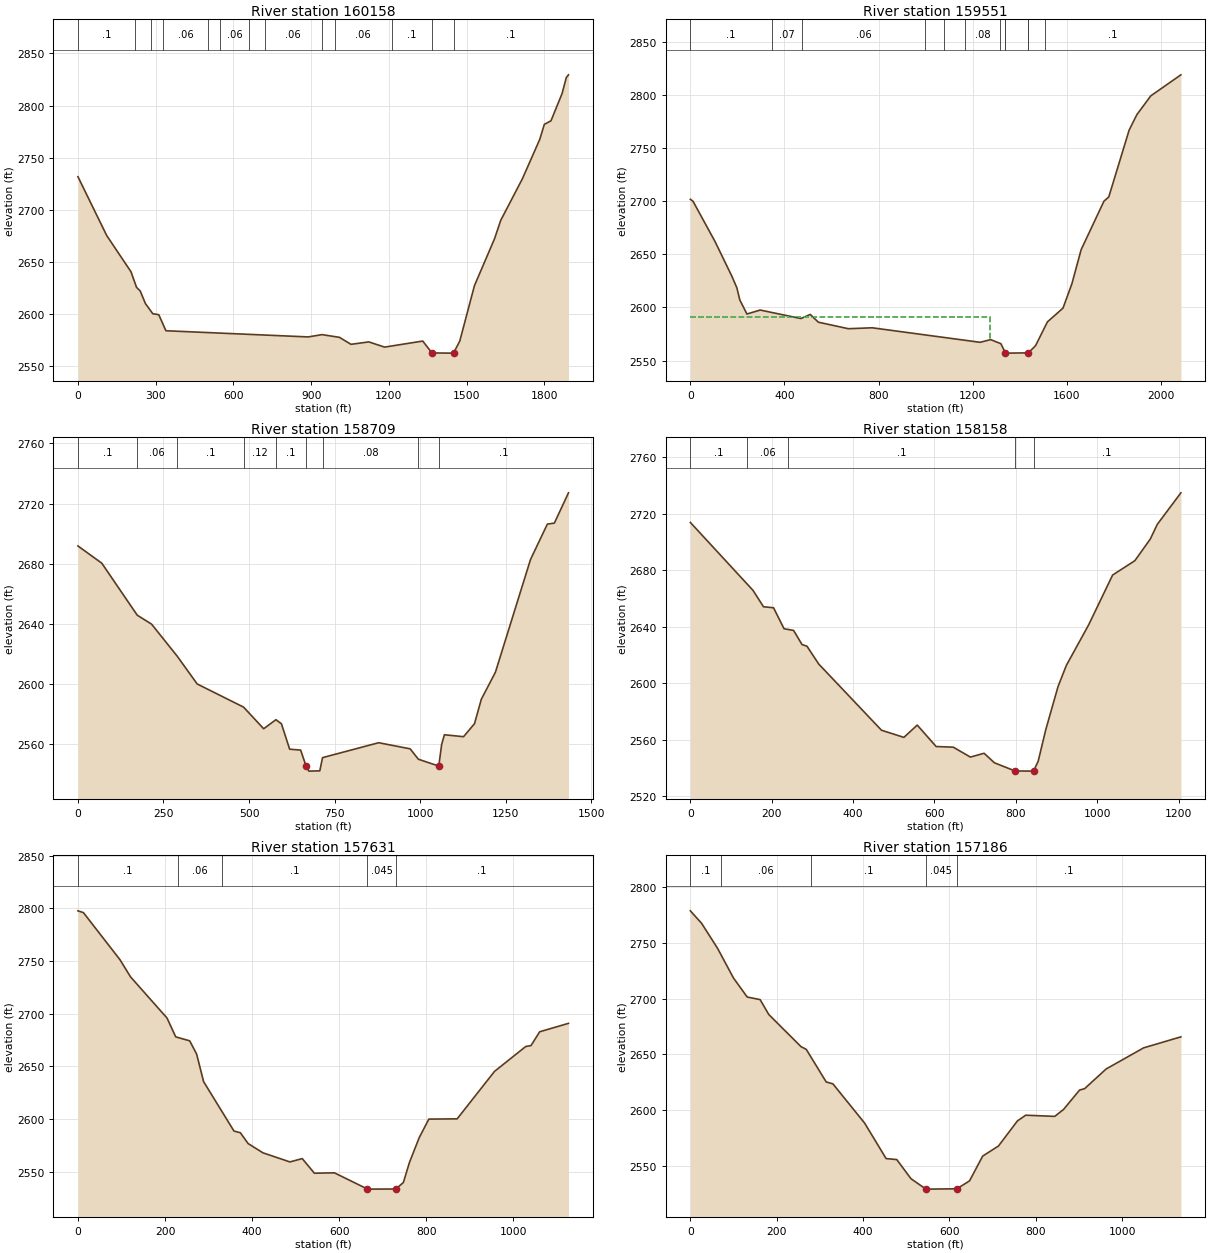
Type RM Length L Ch R = 1 ,160158  ,601,607.4,614.4
XS GIS Cut Line= 2
2327016.88302922661505.2474837592328711.47013619662348.207907231
#Sta/Elev= 30
       0 2731.72   110.9 2675.31   204.7 2640.47   226.2 2625.49   240.5 2621.97
   260.3 2609.97   288.8 2600.24   311.9 2599.26   339.5 2583.85   888.3 2577.92
   941.9 2580.13  1008.9 2577.53  1053.6 2570.82  1122.5 2573.16  1183.1 2568.15
  1330.5 2573.96  1365.8 2562.55  1440.4 2562.37  1449.4 2562.47  1473.3 2573.97
  1529.9 2627.11  1607.5 2672.22  1631.4 2689.86  1714.8 2729.68  1781.8 2767.45
  1799.6 2781.99  1825.3 2785.41  1867.9 2811.49  1884.5 2826.97  1892.7 2829.52
#Mann= 13 ,-1,0
       0      .1       0     220     .06       0     280     .07       0
     330     .06       0     500     .07       0     550     .06       0
     660     .07       0     720     .06       0     940     .07       0
     990     .06       0    1210      .1       0  1365.8    .045       0
  1449.4      .1       0
Bank Sta=1365.8,1449.4
XS Rating Curve= 0 ,0
Exp/Cntr(USF)=0,0
Exp/Cntr=0.3,0.1

Type RM Length L Ch R = 1 ,159551  ,854.3,842.5,692.1
XS GIS Cut Line= 4
2326885.99248613 661788.008080682327017.53992385661972.270392744
2328123.23849587662759.5277760242328609.74586756662640.112330245
#Sta/Elev= 30
       0 2701.89    11.3 2700.05   104.6 2662.23   175.9 2629.69   197.4  2618.7
   210.3 2607.04   240.4 2593.85   296.9 2597.58   469.9 2589.58   509.5 2593.45
   543.9 2586.15   671.6    2580   772.8 2580.87  1231.3  2567.2  1276.2 2569.74
  1319.7  2565.9  1338.9 2557.19  1345.2    2557  1436.4 2557.25    1467 2564.01
  1517.6 2586.45  1583.7 2599.41  1621.8 2622.57  1660.7 2654.41  1757.7 2700.11
  1778.3 2704.15  1864.8 2767.09  1897.7 2781.66  1956.8 2799.35  2084.7 2819.15
#Mann= 12 ,-1,0
       0      .1       0   346.4     .07       0   476.4     .06       0
   996.4     .08       0  1076.4     .06       0  1166.4     .08       0
  1316.4     .05       0  1336.4      .1       0  1338.9    .045       0
  1436.4      .1       0  1436.4    .025       0  1506.4      .1       0
#XS Ineff= 2 , 0
         1274.37 2591.38
Permanent Ineff=
       F       F
Bank Sta=1338.9,1436.4
XS Rating Curve= 0 ,0
Exp/Cntr(USF)=0,0
Exp/Cntr=0.3,0.1

Type RM Length L Ch R = 1 ,158709  ,547.4,550.7,540.8
XS GIS Cut Line= 4
2326853.89653519663480.443244983 2327331.5583183663338.913827764
2328008.24584438663356.605004916 2328260.3451188663414.101330661
#Sta/Elev= 30
       0 2691.78    69.7 2680.33   173.4  2645.7   215.1 2639.79   290.2 2618.44
   348.6 2599.94     484 2584.58   542.8 2570.17   578.7 2576.19   594.8 2573.47
   618.8 2556.57   650.9 2555.96  666.932545.299   674.9 2541.97   706.9 2542.16
   714.9 2550.94   878.9 2560.87     971  2556.8     995 2549.89  1054.7 2545.33
    1063 2559.64    1071 2566.17    1127 2564.88    1159 2573.52  1179.1 2589.84
  1220.2 2607.78  1322.7 2682.73    1372 2706.32  1392.5 2706.99  1433.7 2727.13
#Mann= 9 ,-1,0
       0      .1       0   173.4     .06       0   290.2      .1       0
     484     .12       0   578.7      .1       0  666.93    .045       0
   714.9     .08       0     995    .045       0  1054.7      .1       0
Bank Sta=666.93,1054.7
XS Rating Curve= 0 ,0
Exp/Cntr(USF)=0,0
Exp/Cntr=0.3,0.1

Type RM Length L Ch R = 1 ,158158  ,525.4,527.2,530.8
XS GIS Cut Line= 3
 2326889.2788895663807.7300223012327278.48478685663714.851342251
2328043.62819869663966.950616673
#Sta/Elev= 30
       0 2713.95   153.9 2665.85   179.8 2654.21   204.5  2653.5   230.3 2638.64
   253.8 2637.44   274.4 2627.46   286.7 2626.25   315.5 2613.64   469.8 2566.74
   524.8 2561.67   557.7 2570.37   604.1 2555.19   646.2 2554.74   688.3 2547.71
     722 2550.42   747.3 2543.68   797.8 2537.89   840.5 2537.76   843.6 2537.88
     855 2544.82   873.6 2567.16   903.8 2597.72   924.1 2612.62   978.9 2641.34
  1037.9 2676.68  1092.6 2686.86  1130.5 2702.18  1147.7 2712.59  1205.7 2734.93
#Mann= 5 ,-1,0
       0      .1       0     140     .06       0     240      .1       0
   797.8    .045       0   843.6      .1       0
Bank Sta=797.8,843.6
XS Rating Curve= 0 ,0
Exp/Cntr(USF)=0,0
Exp/Cntr=0.3,0.1

Type RM Length L Ch R = 1 ,157631  ,452.9,444.8,436.6
XS GIS Cut Line= 4
2326787.55462087 664157.130771062327128.10978105664165.976359637
2327610.19435845664395.9616626172327862.29363288664400.384456906
#Sta/Elev= 30
       0 2797.75    12.6 2796.05    96.7 2751.26   120.7 2735.08   204.7 2695.89
   224.7 2678.01   256.7 2674.28   272.7 2661.64   288.7 2635.49   358.5 2588.54
   373.1 2586.94   391.1 2576.64   424.9  2567.9     487 2559.23   515.3 2562.39
   543.2  2548.5   589.2 2548.87   664.5  2533.6   668.7 2533.39   730.2  2533.5
   747.6 2539.69   761.8 2558.96   783.9 2582.17   806.1  2599.9   871.2 2600.15
     957 2645.23  1028.8  2668.9  1040.8 2669.72  1060.8 2682.87  1126.9 2690.85
#Mann= 5 ,-1,0
       0      .1       0     230     .06       0     330      .1       0
   664.5    .045       0   730.2      .1       0
Bank Sta=664.5,730.2
XS Rating Curve= 0 ,0
Exp/Cntr(USF)=0,0
Exp/Cntr=0.3,0.1

Type RM Length L Ch R = 1 ,157186  ,445,428,398.1
XS GIS Cut Line= 2
2326654.87079223664564.0278455652327760.56936425664824.972708562
#Sta/Elev= 30
       0 2778.74      26 2767.57      63 2745.15     100 2718.46   131.7 2701.49
   161.6 2699.16   181.6 2685.82   256.2 2657.06   268.5 2654.57   314.6 2625.39
   330.1  2623.7   403.7 2588.46   453.4  2556.7   478.1 2555.81     511 2538.66
   544.9 2529.55     548 2529.33   617.2 2529.62   646.6 2536.72     677 2558.92
   713.6 2567.98   757.6  2590.5   776.8 2595.59   843.9 2594.52   864.4 2600.75
   901.4  2618.1   913.1 2619.36     963 2637.02  1049.9 2655.95  1136.1  2665.8
#Mann= 5 ,-1,0
       0      .1       0      70     .06       0     280      .1       0
   544.9    .045       0   617.2      .1       0
Bank Sta=544.9,617.2
XS Rating Curve= 0 ,0
Exp/Cntr(USF)=0,0
Exp/Cntr=0.3,0.1

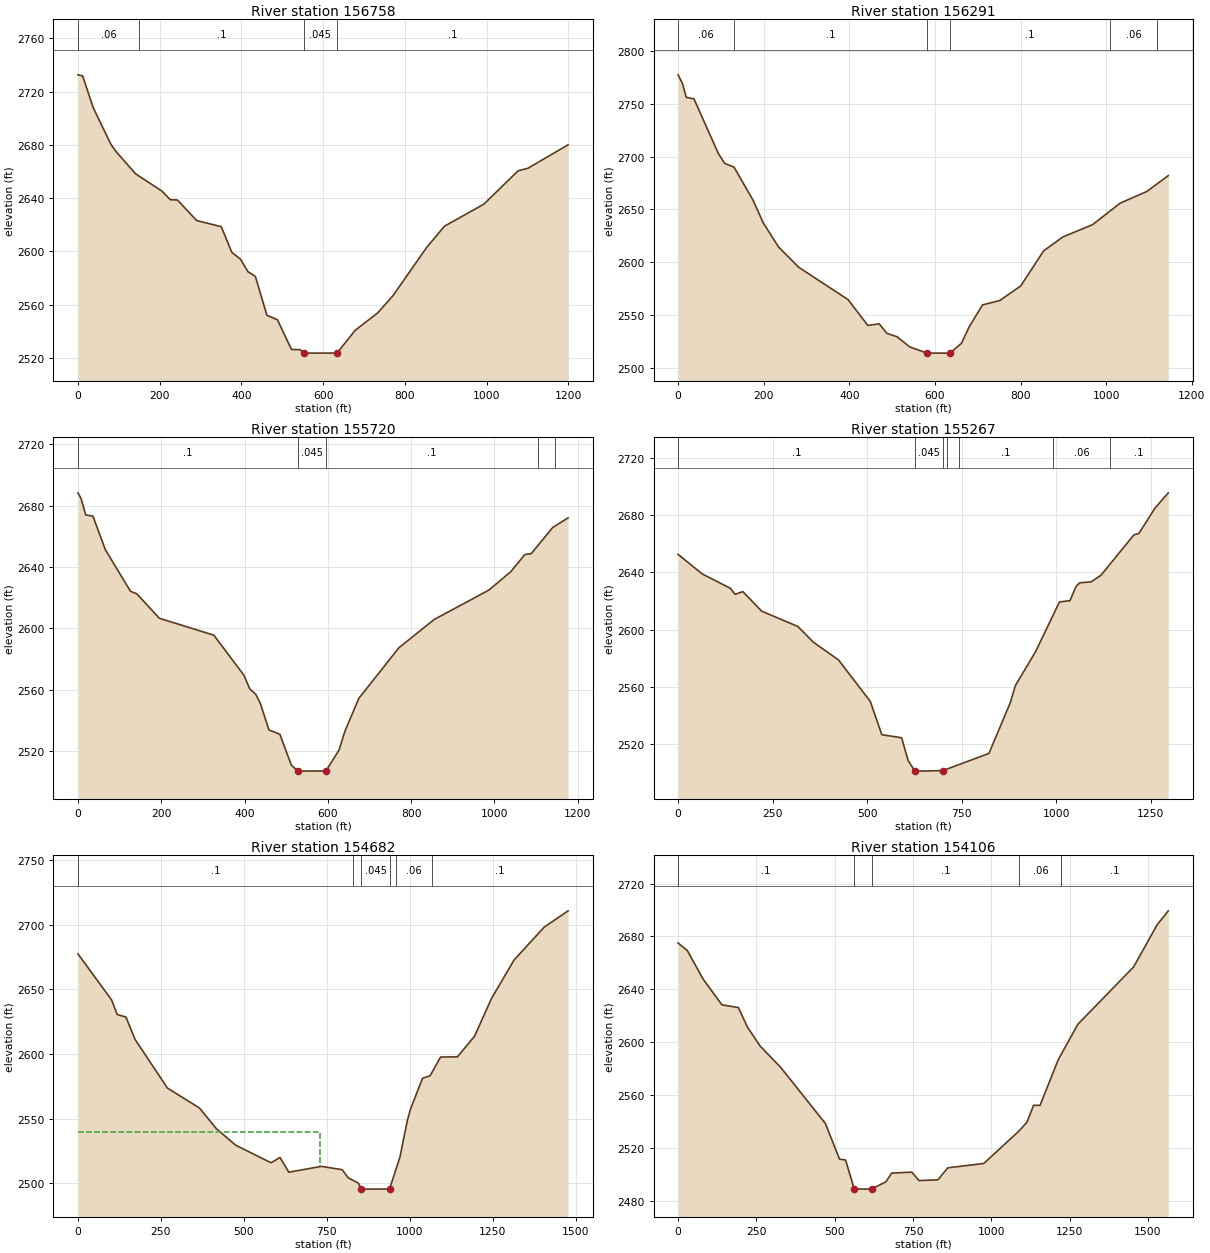
Type RM Length L Ch R = 1 ,156758  ,469.8,467,461.3
XS GIS Cut Line= 3
2326681.40755796665329.1712574052327473.08773552665019.575657238
2327822.48848428665032.844040103
#Sta/Elev= 30
       0 2732.68    11.6 2731.85    37.3 2708.11    80.3 2680.66    93.2 2675.08
   141.1 2658.33   205.9 2645.25   226.3 2638.82   243.5 2638.64   290.7 2623.18
   350.9 2618.57   376.6 2599.29   398.1 2594.09   415.9 2584.86   434.4 2581.12
   462.5 2552.03   488.3 2548.66   522.7 2526.31   544.1 2526.21   552.7 2523.58
   634.3 2523.63   678.3 2540.67   733.1 2553.66   770.9 2566.65   853.2 2602.88
   897.2 2618.97   993.3 2635.46  1077.3 2660.58  1101.3 2662.49  1199.7 2680.13
#Mann= 4 ,-1,0
       0     .06       0     150      .1       0   552.7    .045       0
   634.3      .1       0
Bank Sta=552.7,634.3
XS Rating Curve= 0 ,0
Exp/Cntr(USF)=0,0
Exp/Cntr=0.3,0.1

Type RM Length L Ch R = 1 ,156291  ,583.4,570.8,546
XS GIS Cut Line= 2
2326906.97006665665793.5646576542327933.05834149665284.943314524
#Sta/Elev= 30
       0 2777.27    10.3 2769.05    19.1 2755.95    37.1 2754.59    93.7 2703.24
   108.9 2693.57   130.8 2689.99   175.5 2658.54     199 2637.31     235 2614.47
   281.8 2595.42   397.2 2564.83   443.3 2540.43   469.8 2541.94     488 2532.91
   511.6 2529.75   541.4 2520.07   581.7  2514.3   635.3 2514.26   662.1 2523.59
   679.9 2538.94   711.2 2559.84   751.4 2563.94   800.5 2577.73   854.1 2610.96
   898.7 2623.99   968.3 2635.66  1032.6 2655.93  1095.1 2667.01  1145.2 2682.03
#Mann= 6 ,-1,0
       0     .06       0     130      .1       0   581.7    .045       0
   635.3      .1       0    1010     .06       0    1120      .1       0
Bank Sta=581.7,635.3
XS Rating Curve= 0 ,0
Exp/Cntr(USF)=0,0
Exp/Cntr=0.3,0.1

Type RM Length L Ch R = 1 ,155720  ,461.9,453.3,451.9
XS GIS Cut Line= 3
2327291.75316971666395.0646808352327645.57671276666125.274229261
2328021.51422725665497.237440352
#Sta/Elev= 30
       0 2688.35     7.4 2684.72    18.8 2673.94    36.1 2673.13    65.9 2651.19
   126.3 2624.07   141.4 2622.44   195.7 2606.48   326.4 2595.46   398.4  2569.4
   412.6 2560.38   426.9 2556.93   438.2 2550.77   458.6 2533.63   484.8 2530.83
   512.3 2510.71   527.9  2506.8     529 2506.75   595.6 2506.89   626.9 2520.51
   640.9 2532.69   674.4 2554.22   770.6 2587.23   855.3 2605.71   986.4 2624.82
  1038.9 2636.81  1073.1 2648.07  1088.5 2648.72  1139.7 2665.67  1176.9 2672.03
#Mann= 5 ,-1,0
       0      .1       0   527.9    .045       0   595.6      .1       0
 1104.95     .06       0 1144.95      .1       0
Bank Sta=527.9,595.6
XS Rating Curve= 0 ,0
Exp/Cntr(USF)=0,0
Exp/Cntr=0.3,0.1

Type RM Length L Ch R = 1 ,155267  ,556.5,584.8,614.7
XS GIS Cut Line= 3
2327535.00685556666589.6676295112327999.40025581666461.406595156
2328322.26423884665713.954360469
#Sta/Elev= 30
       0 2652.63    63.5 2638.98   138.2 2628.91   150.6 2624.71   171.4 2626.57
   221.1 2612.92   316.6 2602.26   358.1 2591.18   424.1 2578.92   508.2 2549.94
   538.7  2526.7     591 2524.58   608.4 2508.57   625.6 2501.56   630.2 2501.28
   699.9 2501.64   821.9 2513.64   878.5 2549.15   891.6 2560.89   945.1 2584.61
  1008.3 2619.36  1036.3 2620.29  1051.6 2629.98  1061.5  2632.7    1092 2633.41
  1118.2 2638.04  1205.3 2666.24  1218.4 2667.18  1260.5 2684.74    1296 2695.54
#Mann= 7 ,-1,0
       0      .1       0   625.6    .045       0   699.9      .1       0
  711.78    .025       0  741.78      .1       0  991.78     .06       0
 1141.78      .1       0
Bank Sta=625.6,699.9
XS Rating Curve= 0 ,0
Exp/Cntr(USF)=0,0
Exp/Cntr=0.3,0.1

Type RM Length L Ch R = 1 ,154682  ,573.3,576.1,584.9
XS GIS Cut Line= 3
2327738.45539281667014.2558811672328684.93337046 666545.43968663
2328950.30102775666218.152909311
#Sta/Elev= 30
       0 2677.57   101.6 2641.84   118.5 2630.56   144.8 2628.62   172.2 2611.32
   269.7 2573.69   366.3 2558.22     417 2542.31   475.1 2529.49   582.2 2515.81
     609 2519.94   635.8  2508.5   733.5 2513.02   796.5 2510.47   814.3 2504.28
   845.6 2499.99   854.5 2495.41   939.3 2495.47   970.6  2520.1   992.9 2548.43
  1002.7 2557.52  1038.8 2581.22  1061.7 2583.22  1093.1 2597.67  1143.9 2597.82
  1195.6 2613.81  1246.4 2642.87  1314.7 2672.81  1405.7 2698.27  1477.6 2710.86
#Mann= 6 ,-1,0
       0      .1       0     830     .12       0   854.5    .045       0
   939.3     .12       0     960     .06       0 1066.22      .1       0
#XS Ineff= 2 , 0
          730.11 2539.48
Permanent Ineff=
       F       F
Bank Sta=854.5,939.3
XS Rating Curve= 0 ,0
Exp/Cntr(USF)=0,0
Exp/Cntr=0.3,0.1

Type RM Length L Ch R = 1 ,154106  ,525.1,525.2,540.6
XS GIS Cut Line= 3
2328034.78261011667474.226487129 2329003.3745592666925.799995405
2329295.27898222666580.822040934
#Sta/Elev= 30
       0    2675    29.2 2669.43    79.7 2647.76   140.1 2628.18   192.6 2626.14
   221.3  2611.4   261.9 2597.03   327.6 2580.86   470.5 2538.29   515.4 2511.38
   534.8 2510.67   562.4 2488.81   617.6 2488.65   619.1 2488.88   663.5 2494.17
   681.9  2500.8   746.3 2501.51   769.2 2495.13   829.4 2495.69   861.2 2504.78
   976.1 2508.09    1090    2533  1114.3 2539.48  1134.9  2552.1  1155.8 2552.13
  1213.4 2586.47  1276.3 2613.45  1454.5 2656.94  1529.2 2688.72    1565 2699.37
#Mann= 5 ,-1,0
       0      .1       0   562.4    .045       0   619.1      .1       0
    1090     .06       0 1223.08      .1       0
Bank Sta=562.4,619.1
XS Rating Curve= 0 ,0
Exp/Cntr(USF)=0,0
Exp/Cntr=0.3,0.1

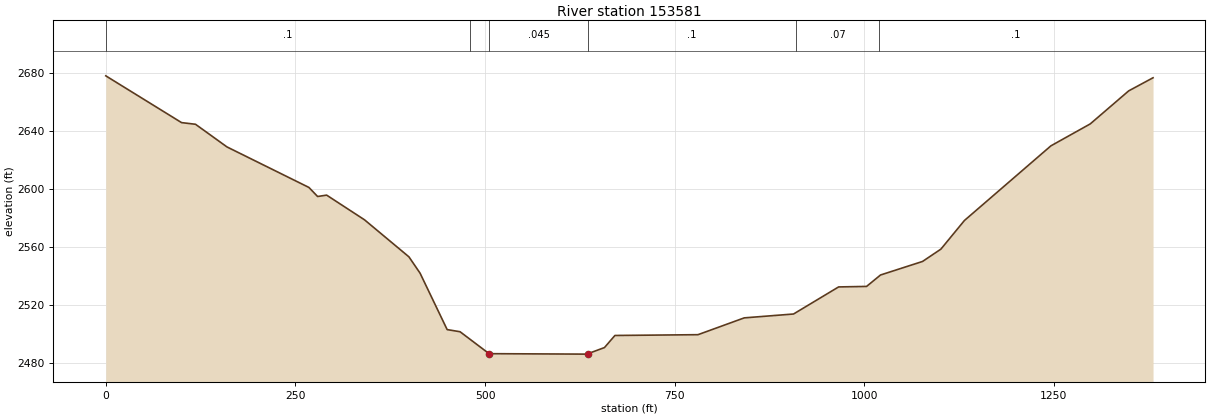
Type RM Length L Ch R = 1 ,153581  ,537.5,543.7,542.8
XS GIS Cut Line= 2
2328397.45174173667867.8551787692329596.02899381667182.322064115
#Sta/Elev= 30
       0 2678.36    99.9 2646.08   118.3 2644.94   159.8  2629.3   267.8 2601.36
   279.3  2595.1   291.2 2596.05   341.1 2579.03   399.7 2553.47   414.4 2542.19
   450.1 2503.27   467.1  2501.8   505.4 2486.66   633.8 2486.35  636.292486.766
   657.5 2490.87   671.3 2499.22   780.8 2499.76   841.8 2511.36   906.8 2514.03
   966.2 2532.71  1003.1 2533.06  1021.5 2540.95  1076.9 2550.29  1101.1  2558.8
  1132.1 2578.54  1246.1 2630.04    1298 2645.19  1348.7 2667.98  1380.8 2677.02
#Mann= 6 ,-1,0
       0      .1       0     480    .025       0   505.4    .045       0
  636.29      .1       0     910     .07       0    1020      .1       0
Bank Sta=505.4,636.29
XS Rating Curve= 0 ,0
Exp/Cntr(USF)=0,0
Exp/Cntr=0.3,0.1