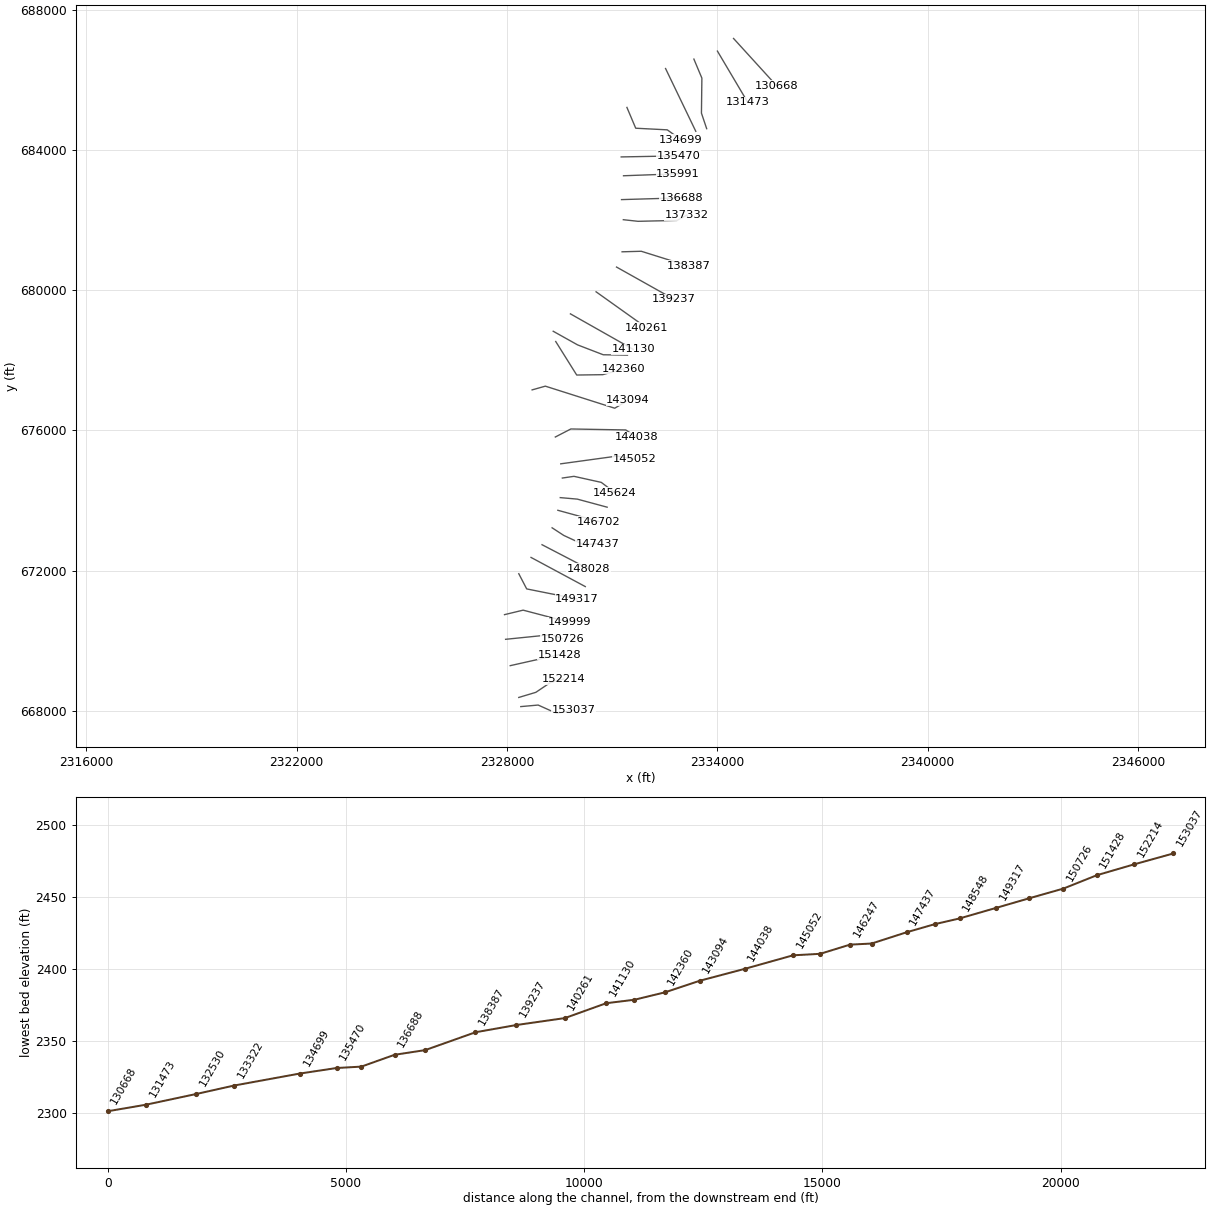
HEC-RAS study SHAVERSFK.prj: SHAVERSFK

--- SHAVERSFK.g01 (geometry) --- (continued)

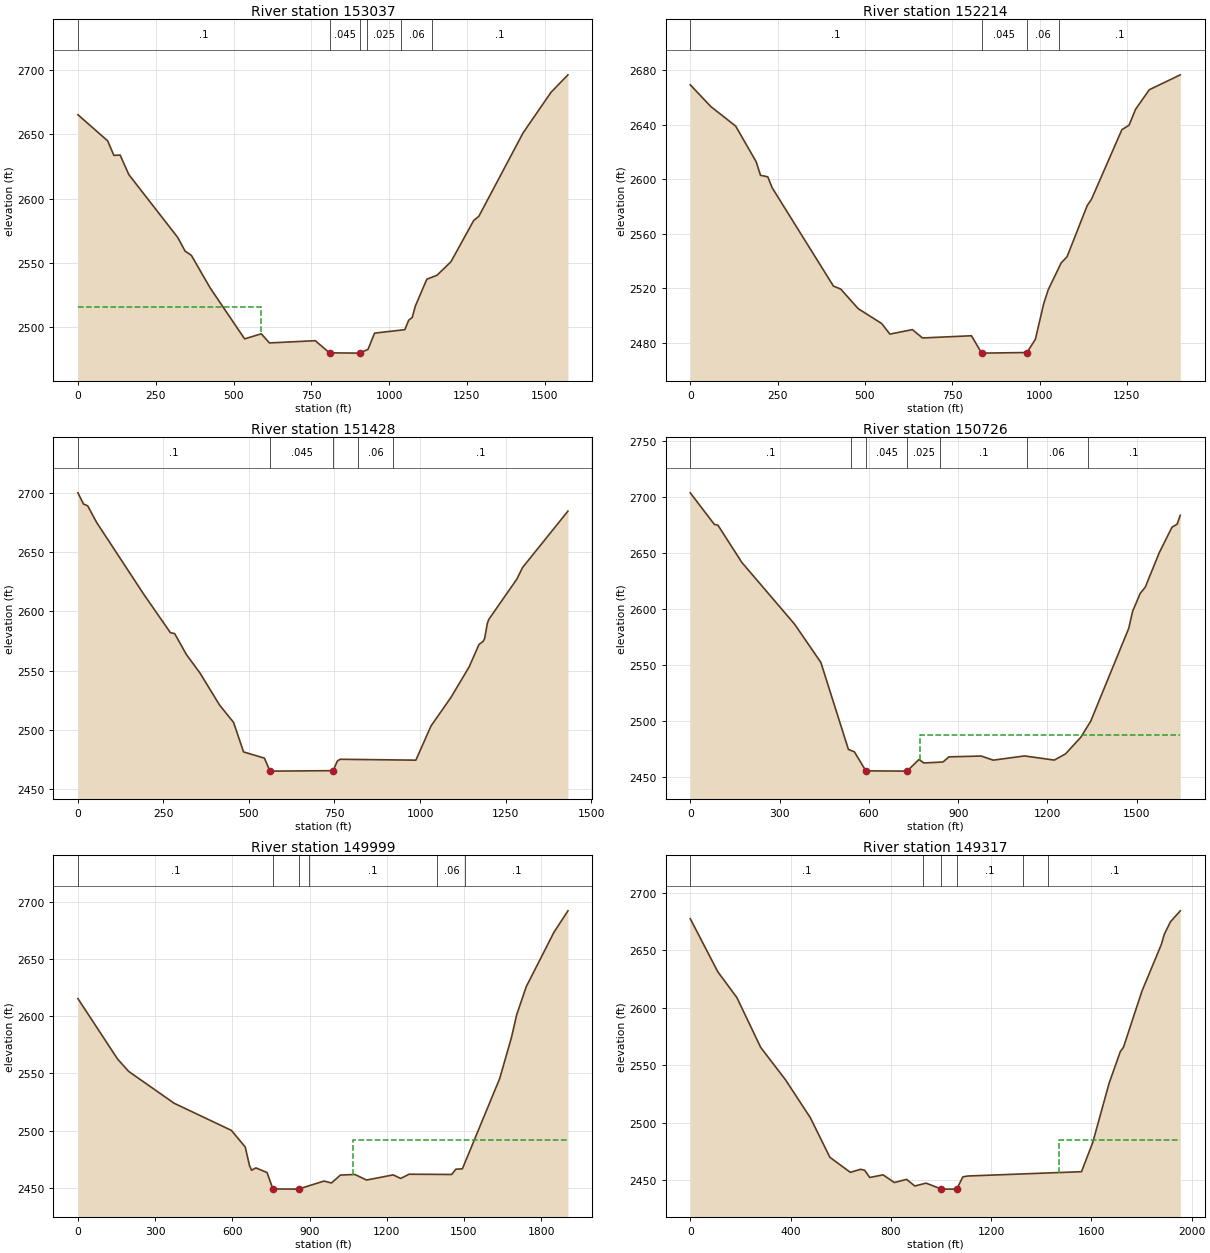
Type RM Length L Ch R = 1 ,153037  ,754.5,823.2,867.7
XS GIS Cut Line= 4
2328393.02894745 668119.954453192328888.38190771668164.182396071
2329419.11722228667925.3515045142329905.62459397668018.230184564
#Sta/Elev= 30
       0 2665.15    95.5 2644.89   115.6 2633.59   135.7 2633.82   163.8  2618.6
   320.4    2570   344.5 2559.27   364.6 2555.97   424.8 2530.76   535.7 2491.16
   589.2  2495.1   615.5 2488.02   762.6 2489.75   808.5 2480.32   904.8  2480.1
   905.6 2480.22     932 2482.97   953.3 2495.63  1050.5 2498.31  1062.9 2505.68
  1074.2 2507.77  1084.5 2516.78  1121.1 2537.47  1153.7 2540.51  1198.5 2550.98
  1271.8 2583.06  1288.1 2586.24  1430.6 2651.09  1520.2 2682.55  1574.6 2696.11
#Mann= 6 ,-1,0
       0      .1       0   808.5    .045       0   905.6      .1       0
  927.32    .025       0 1037.32     .06       0 1139.32      .1       0
#XS Ineff= 2 , 0
          588.01 2515.95
Permanent Ineff=
       F       F
Bank Sta=808.5,905.6
XS Rating Curve= 0 ,0
Exp/Cntr(USF)=0,0
Exp/Cntr=0.3,0.1

Type RM Length L Ch R = 1 ,152214  ,836.6,786,772.4
XS GIS Cut Line= 4
 2328335.5326217668380.8993161872328822.03999339668526.851527694
2329242.20545076668809.9103621322329618.14296525 668907.21183647
#Sta/Elev= 30
       0 2669.12    59.1 2653.12   130.1 2638.83   188.6  2612.8   201.1 2602.83
     222 2601.68   234.5 2593.68   409.9 2521.66   430.8 2519.46   480.9  2505.1
   547.9 2494.25   571.7 2486.48   635.9 2489.77   664.8 2483.65   805.1 2485.27
   833.9  2472.7   839.7 2472.54   963.9 2472.99     988 2482.64  1012.1 2508.96
  1024.8 2518.96    1062 2538.67  1078.6 2543.09  1136.4 2580.62  1148.8 2585.33
  1235.7 2636.23  1256.2 2639.48  1274.7 2651.09  1314.2 2665.49  1402.9 2676.41
#Mann= 4 ,-1,0
       0      .1       0   833.9    .045       0   963.9     .06       0
 1054.55      .1       0
Bank Sta=833.9,963.9
XS Rating Curve= 0 ,0
Exp/Cntr(USF)=0,0
Exp/Cntr=0.3,0.1

Type RM Length L Ch R = 1 ,151428  ,705.7,702.1,687.1
XS GIS Cut Line= 2
2328092.27893586669287.5721452462329489.88193089  669601.5905397
#Sta/Elev= 30
       0 2700.16    16.3 2690.72    28.6 2689.18    54.8  2675.1   192.6 2614.37
   270.5 2581.94   282.8  2581.2   317.5 2563.31   356.6 2547.98     414 2520.83
     455 2506.15   484.2 2481.19   545.2 2475.93  560.792465.445   565.7 2464.96
     746 2465.36   758.3 2473.45   766.5 2474.97   987.9 2474.23  1032.3 2503.21
  1090.4 2527.26  1143.7 2553.11  1172.4 2572.02  1184.7 2574.63  1188.8 2577.05
    1197 2590.04  1201.1 2593.22  1283.1 2627.25  1299.5 2636.95  1432.4 2684.71
#Mann= 5 ,-1,0
       0      .1       0  560.79    .045       0     746      .1       0
     820     .06       0     920      .1       0
Bank Sta=560.79,746
XS Rating Curve= 0 ,0
Exp/Cntr(USF)=0,0
Exp/Cntr=0.3,0.1

Type RM Length L Ch R = 1 ,150726  ,738.7,726.3,693.8
XS GIS Cut Line= 3
2327959.59510721670039.4471742212329268.74221649670172.131002864
2329578.33781666670057.138351374
#Sta/Elev= 30
       0 2704.02      81 2675.85    93.1 2675.11   173.2 2641.95   350.4 2586.85
   438.8 2552.65   531.3 2475.04   551.4 2472.89   589.8 2455.94   728.3 2455.67
  728.472455.787   768.5 2466.06   784.6 2462.95   848.9 2463.82     869 2468.41
   977.6 2469.12  1017.8 2465.46  1122.8 2469.23  1222.8 2465.53  1260.4 2471.02
  1311.3  2485.7  1345.1 2500.14  1473.1 2583.22  1485.9 2598.28  1511.5 2614.24
  1528.6 2619.95  1575.5  2650.6  1618.2 2673.35  1635.3    2676  1646.1 2683.96
#Mann= 7 ,-1,0
       0      .1       0     540    .025       0   589.8    .045       0
  728.47    .025       0     840      .1       0    1130     .06       0
 1335.85      .1       0
#XS Ineff= 2 , 0
                          770.69         2487.76
Permanent Ineff=
       F       F
Bank Sta=589.8,728.47
XS Rating Curve= 0 ,0
Exp/Cntr(USF)=0,0
Exp/Cntr=0.3,0.1

Type RM Length L Ch R = 1 ,149999  ,690.4,682.3,679
XS GIS Cut Line= 3
 2327928.6355472670742.6714660282328459.37086177670870.932500382
2329772.94076533670525.954545911
#Sta/Elev= 30
       0 2615.36   154.1 2562.52   197.1 2551.74     374 2523.88   596.5 2500.18
   650.2 2485.66   666.8 2469.34     675 2465.37   691.6  2467.4   734.8 2463.38
   757.6 2449.01     857 2448.85   859.3 2449.05   956.3 2455.92   985.2 2454.23
  1019.8 2461.12  1076.2 2461.66  1121.7  2456.8  1225.1  2461.3    1254 2458.21
  1287.1 2461.87  1452.6 2461.67  1468.5 2466.27  1493.9 2466.59  1638.7 2545.35
  1684.7 2581.46  1704.8 2601.14    1742 2625.73  1849.6 2673.25  1904.1 2692.04
#Mann= 6 ,-1,0
       0      .1       0   757.6    .045       0   859.3    .025       0
  896.01      .1       0 1396.01     .06       0 1506.01      .1       0
#XS Ineff= 2 , 0
                         1067.15         2492.07
Permanent Ineff=
       F       F
Bank Sta=757.6,859.3
XS Rating Curve= 0 ,0
Exp/Cntr(USF)=0,0
Exp/Cntr=0.3,0.1

Type RM Length L Ch R = 1 ,149317  ,781.4,769.4,756.8
XS GIS Cut Line= 3
 2328335.5326217671910.2891580842328561.09513039671476.855317851
2329998.50327402671189.373689125
#Sta/Elev= 30
       0 2677.42   109.5 2631.38   186.1 2608.78   280.8 2565.55     380 2537.32
   479.2 2504.29     557 2469.96   638.6 2456.88   679.4 2459.53   695.7 2458.66
   716.1 2452.41   769.1 2454.71     814 2448.03     863 2450.78   895.6    2445
   940.5 2447.51  1001.7 2442.35  1062.8 2442.29  1087.3 2452.97  1107.7  2453.7
  1560.5 2457.45  1605.4 2482.87  1670.6 2534.37  1715.5 2561.95  1727.8 2565.56
  1801.2 2614.21  1878.7 2654.85  1890.9 2663.89  1915.3  2674.7  1954.5 2684.23
#Mann= 6 ,-1,0
       0      .1       0  928.61     .07       0  1001.7    .045       0
  1062.8      .1       0 1328.61     .06       0 1428.61      .1       0
#XS Ineff= 2 , 0
                         1470.04         2484.83
Permanent Ineff=
       F       F
Bank Sta=1001.7,1062.8
XS Rating Curve= 0 ,0
Exp/Cntr(USF)=0,0
Exp/Cntr=0.3,0.1

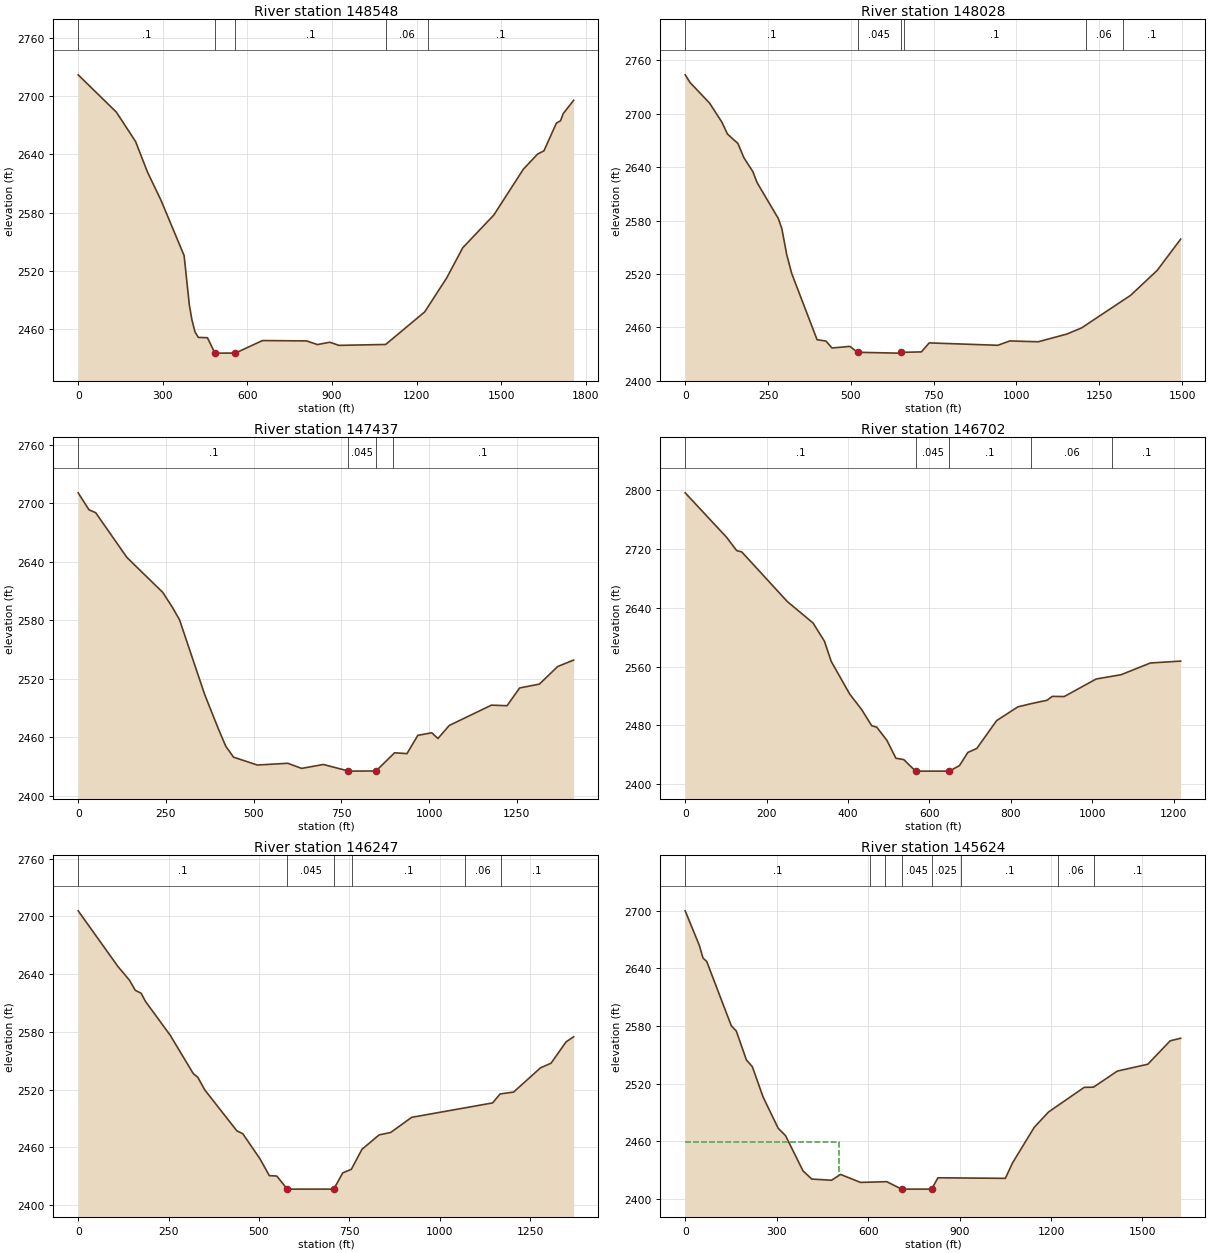
Type RM Length L Ch R = 1 ,148548  ,498.1,519.9,520.7
XS GIS Cut Line= 2
2328684.93337046672374.6825583332330232.91137129671543.197232172
#Sta/Elev= 30
       0 2722.19   135.4  2683.7   203.5  2653.4   245.7 2621.87   294.3 2592.31
   375.7 2535.61   394.2 2484.74   403.2  2469.5   414.1 2457.06   425.8 2451.17
   458.4 2450.84     485 2434.94   557.6 2434.99   653.4 2447.91   809.9 2447.56
   848.5 2443.78   892.6 2446.19   924.6 2442.95  1090.5 2443.88  1228.9 2477.47
  1306.8  2512.5  1364.1 2543.75    1474 2577.45  1579.2 2624.93  1629.2 2640.33
  1651.8 2643.72  1696.1 2672.39  1710.8 2674.75    1720 2682.09  1757.2 2695.88
#Mann= 5 ,-1,0
       0      .1       0     485    .045       0   557.6      .1       0
    1090     .06       0    1240      .1       0
Bank Sta=485,557.6
XS Rating Curve= 0 ,0
Exp/Cntr(USF)=0,0
Exp/Cntr=0.3,0.1

Type RM Length L Ch R = 1 ,148028  ,616.3,590.2,597
XS GIS Cut Line= 2
2328998.95176492672737.3516899572330325.79005134672047.395781015
#Sta/Elev= 30
       0 2743.74    14.9 2735.02    73.5 2712.01   110.8 2690.54   127.6 2677.19
   159.2 2666.57   177.2 2650.57   204.3 2634.92   217.1 2622.57   280.9 2582.37
   291.7 2570.93   306.5 2541.69   321.5 2520.51   398.1 2446.08   425.2 2444.47
     443 2436.77   497.3 2438.54   520.1 2431.91   641.7 2430.97   651.3 2431.84
   712.9 2432.36   736.6 2442.47   943.7 2439.78   979.8 2444.68  1065.4 2443.73
  1151.9 2452.37  1196.4 2459.29  1344.7 2495.98  1424.8 2523.99  1495.5 2559.06
#Mann= 6 ,-1,0
       0      .1       0   520.1    .045       0   651.3    .025       0
     660      .1       0    1210     .06       0    1320      .1       0
Bank Sta=520.1,651.3
XS Rating Curve= 0 ,0
Exp/Cntr(USF)=0,0
Exp/Cntr=0.3,0.1

Type RM Length L Ch R = 1 ,147437  ,734.1,735.5,746
XS GIS Cut Line= 4
2329286.43339364673219.4362673592329618.14296525673002.719347242
2330188.68342841672737.3516899572330573.46653148672768.311249973
#Sta/Elev= 30
       0 2710.55    30.7  2693.2    49.9 2690.17   138.7 2644.37     241  2608.5
   269.6 2592.53   288.8 2580.36   360.4 2503.85   398.9 2469.09   420.5 2450.81
   442.6 2439.67   510.3  2431.6     597 2433.37   636.7 2428.16   698.5 2432.15
   769.8 2425.45   773.4 2425.34   848.4 2425.49   901.4 2444.14   936.7 2443.29
   967.6    2462  1007.3 2464.65  1024.9 2458.79  1057.1 2472.14  1177.4 2492.97
  1221.7 2492.38  1257.7 2510.58  1313.9 2514.51  1366.1 2532.56  1411.5 2539.16
#Mann= 4 ,-1,0
       0      .1       0   769.8    .045       0   848.4    .025       0
  896.23      .1       0
Bank Sta=769.8,848.4
XS Rating Curve= 0 ,0
Exp/Cntr(USF)=0,0
Exp/Cntr=0.3,0.1

Type RM Length L Ch R = 1 ,146702  ,455.2,455,455.4
XS GIS Cut Line= 2
 2329450.0767823673719.2120219132330624.44853986 673397.96199588
#Sta/Elev= 30
       0 2796.63   101.7 2736.09   126.6  2717.9     139 2716.16   250.8 2648.61
   314.1 2619.37   342.2 2594.43   358.8 2567.09   404.4  2522.4   433.5 2501.49
   458.3 2479.37   470.8 2477.37   495.7 2459.44   517.8 2435.09   537.1 2433.21
   566.2 2417.52   649.1 2417.51     674 2425.07   694.7    2443   716.5 2448.34
   765.3 2486.33   817.4 2505.03     850 2509.42   889.1 2514.04     902 2519.33
   931.4 2519.11  1009.9 2543.01  1071.4 2548.88    1143 2564.81  1217.5  2567.4
#Mann= 5 ,-1,0
       0      .1       0   566.2    .045       0   649.1      .1       0
     850     .06       0    1050      .1       0
Bank Sta=566.2,649.1
XS Rating Curve= 0 ,0
Exp/Cntr(USF)=0,0
Exp/Cntr=0.3,0.1

Type RM Length L Ch R = 1 ,146247  ,621.1,623.3,625.5
XS GIS Cut Line= 3
 2329518.8688768674080.565434057  2330005.288962  674037.8093191
2330856.52536591673807.667907675
#Sta/Elev= 30
       0 2705.79   109.7 2648.09   141.9 2633.71   157.9 2623.23   174.1 2620.19
     186 2611.75   254.3 2576.66   318.5  2536.6   330.6 2532.99   349.9 2519.87
     439 2477.18   455.1 2474.35   502.9 2448.09   528.6 2430.74   549.3  2430.3
   578.3 2416.73   706.8 2416.73   731.6 2433.61   755.4 2437.33   784.7 2458.05
   832.2 2473.06   864.2 2475.59   922.2  2491.3    1146 2506.27  1166.7  2515.6
    1204 2517.52  1278.6 2542.75  1307.6 2547.49    1349  2569.6  1370.1 2574.98
#Mann= 6 ,-1,0
       0      .1       0   578.3    .045       0   706.8    .025       0
   758.3      .1       0  1068.3     .06       0  1168.3      .1       0
Bank Sta=578.3,706.8
XS Rating Curve= 0 ,0
Exp/Cntr(USF)=0,0
Exp/Cntr=0.3,0.1

Type RM Length L Ch R = 1 ,145624  ,558.3,572,596.9
XS GIS Cut Line= 4
2329578.33781666674639.1532338362329910.04738826674687.803971005
2330688.45918297674515.3149937692331082.08787461674218.987776467
#Sta/Elev= 30
       0 2700.01    46.3 2664.13    58.5 2650.86    70.6 2647.33   151.4 2580.26
   167.6 2574.94   200.8 2544.82   220.2 2537.84   255.6 2506.19   305.1 2473.71
   329.3 2465.98   386.6 2429.31   415.3 2420.83   480.1 2419.61   509.5 2425.67
   575.1 2417.36   661.1 2418.12   710.3 2410.36   808.6 2410.37   829.1 2422.16
  1050.3 2421.59  1073.7 2437.61  1145.3 2474.81  1192.3 2490.73    1309 2516.28
  1339.5  2516.5  1417.6 2533.21  1517.7 2540.36  1590.9 2564.71  1625.3 2567.39
#Mann= 8 ,-1,0
       0      .1       0  605.26     .05       0  655.26      .1       0
   710.3    .045       0   808.6    .025       0  905.26      .1       0
 1222.55     .06       0 1342.55      .1       0
#XS Ineff= 2 , 0
          502.96 2459.14
Permanent Ineff=
       F       F
Bank Sta=710.3,808.6
XS Rating Curve= 0 ,0
Exp/Cntr(USF)=0,0
Exp/Cntr=0.3,0.1

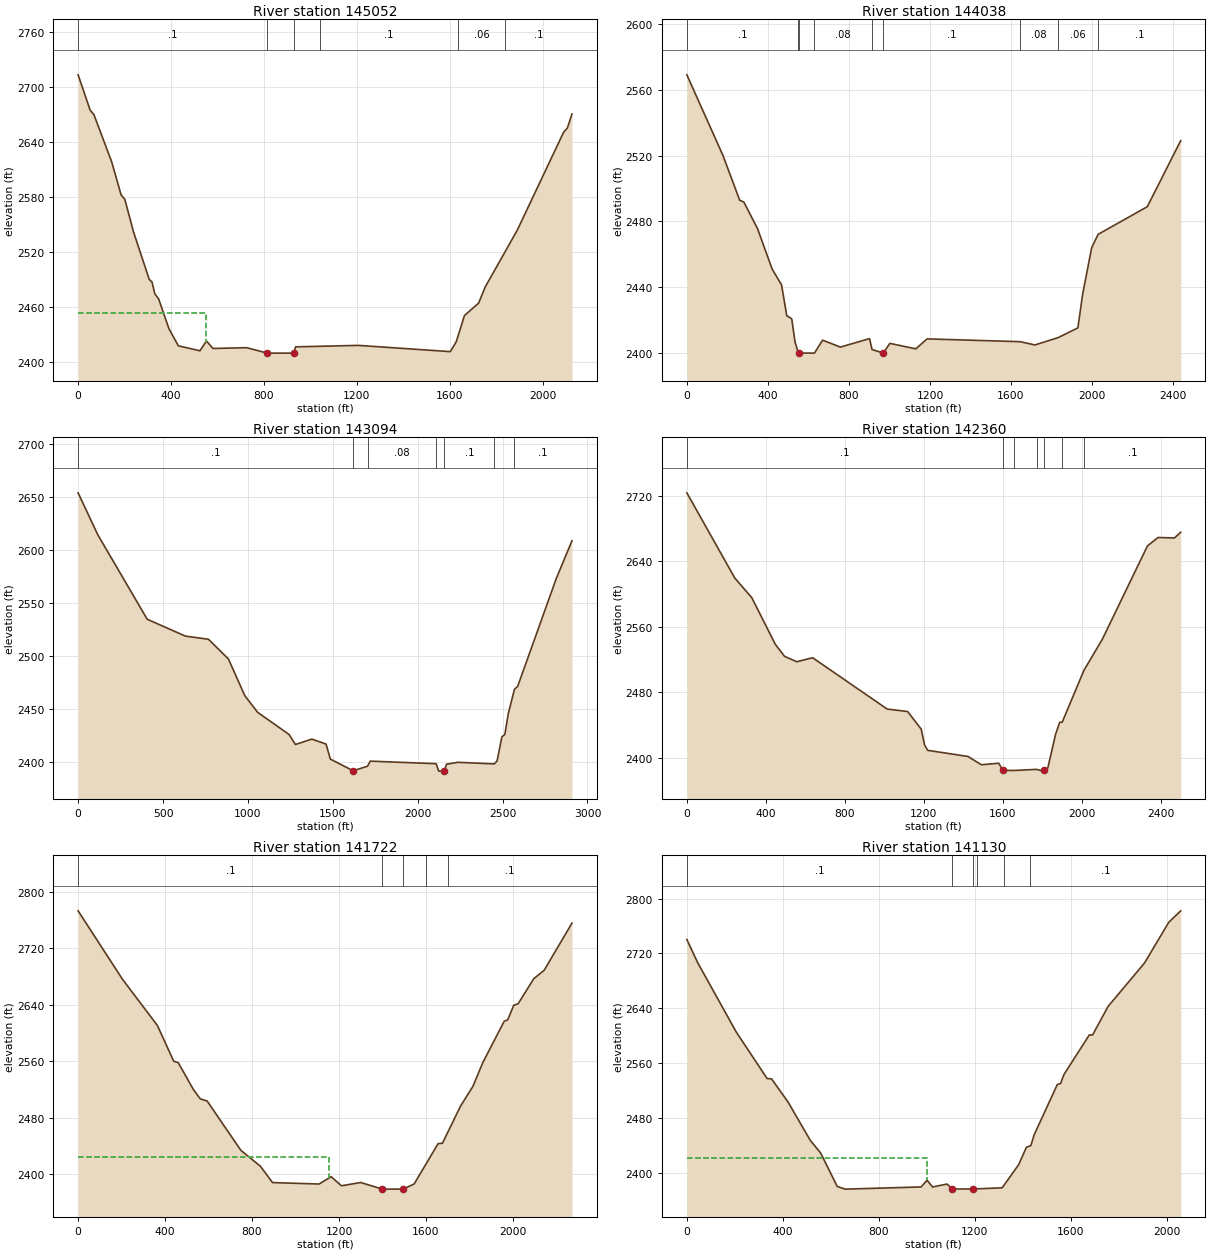
Type RM Length L Ch R = 1 ,145052  ,1022,1013.4,905.8
XS GIS Cut Line= 3
   2329532.80093675044.6906793372331134.09209995675264.676367222
2331635.45483048675172.589335084
#Sta/Elev= 30
       0 2713.35    51.9 2674.77      68 2669.94   144.7 2618.17   185.1 2582.22
   201.2 2577.26   238.7 2541.59   306.2 2489.86   318.3 2486.95   330.4 2473.95
   346.6 2468.64     391 2436.07   431.4 2417.31   524.3 2411.88   552.5 2422.57
   580.8  2414.4   726.1 2415.24     815 2409.31     928 2409.31   936.1 2416.16
  1206.3 2417.77  1602.3 2410.94    1628 2421.77  1663.2 2450.37  1724.3 2463.94
  1752.7 2481.62  1890.9  2543.8  2090.2 2650.69  2106.5 2655.38  2126.1 2670.56
#Mann= 6 ,-1,0
       0      .1       0     815    .045       0     928    .025       0
    1040      .1       0 1636.33     .06       0 1836.33      .1       0
#XS Ineff= 2 , 0
          550.54  2453.1
Permanent Ineff=
       F       F
Bank Sta=815,928
XS Rating Curve= 0 ,0
Exp/Cntr(USF)=0,0
Exp/Cntr=0.3,0.1

Type RM Length L Ch R = 1 ,144038  ,954.7,943.8,963.7
XS GIS Cut Line= 4
2329378.06121115675809.4771266232329821.18093801  676038.6394027
2331386.96932727676010.8700237842331699.23657546675807.028655368
#Sta/Elev= 30
       0 2569.12     178 2520.18   260.6 2492.92   281.6 2491.71   349.1 2475.52
   421.2 2450.98   467.4 2441.41   493.2  2422.7   517.9 2420.73   533.9 2406.77
   549.9 2400.08   553.9 2399.94   629.9 2399.94   669.9 2407.79   757.9 2403.58
   901.9 2408.75   913.9 2402.14   969.9 2399.91  1001.9 2405.85    1130 2402.52
    1186 2408.57    1646 2406.86  1718.1 2404.88  1832.3 2409.32  1930.1 2415.26
  1954.1    2436  1998.1 2463.93  2030.1 2472.13  2272.9 2488.96  2437.8 2529.11
#Mann= 9 ,-1,0
       0      .1       0   549.9    .025       0   553.9    .045       0
   629.9     .08       0   913.9    .045       0   969.9      .1       0
    1646     .08       0  1832.3     .06       0  2030.1      .1       0
Bank Sta=553.9,969.9
XS Rating Curve= 0 ,0
Exp/Cntr(USF)=0,0
Exp/Cntr=0.3,0.1

Type RM Length L Ch R = 1 ,143094  ,723.4,734.9,925.3
XS GIS Cut Line= 4
2328716.75178724677153.4658851832329092.82955423677259.895396873
2331072.70074519676630.634010598 2331451.2807662676855.735644713
#Sta/Elev= 30
       0 2654.15   115.9 2614.61   406.9 2534.92   631.8 2519.01   767.9 2516.02
   885.4 2497.42     982 2462.79  1057.5  2447.1  1242.2 2426.27    1280 2416.74
  1376.5 2421.85  1460.4 2417.17  1485.6 2403.02  1619.9 2391.96  1704.7 2396.26
  1720.7 2401.06  2109.2 2398.64  2123.6 2391.64  2157.6 2391.87  2169.7 2398.12
  2236.6 2399.96    2451 2398.46  2467.8 2401.25  2496.1 2424.03  2513.6 2426.25
    2534 2446.14  2570.1 2468.88  2588.7 2471.49  2816.7 2573.47  2908.8 2608.95
#Mann= 7 ,-1,0
       0      .1       0  1619.9    .045       0  1704.7     .08       0
  2109.2    .045       0  2157.6      .1       0    2451     .06       0
  2570.1      .1       0
Bank Sta=1619.9,2157.6
XS Rating Curve= 0 ,0
Exp/Cntr(USF)=0,0
Exp/Cntr=0.3,0.1

Type RM Length L Ch R = 1 ,142360  ,650.5,637.9,602.1
XS GIS Cut Line= 4
2329389.59901083678533.1407465482329988.12014446677577.084063125
2330729.93234779677587.3159555852331338.72994914677756.142181171
#Sta/Elev= 30
       0 2723.87   242.7 2619.74     329 2595.61   448.3 2538.54   494.8 2523.93
   556.8 2517.32     637 2522.24  1014.7 2459.46  1118.4 2456.43  1187.3 2434.84
    1204 2415.69    1220 2408.98    1424  2401.5    1492 2391.34    1580 2393.22
    1600  2384.6  1656.1 2384.34  1771.3 2385.71  1804.1 2383.56 1809.622384.645
  1828.1 2387.18  1868.1 2428.87  1888.8 2443.28  1901.2 2443.36  2011.5 2506.89
  2104.6 2544.81  2332.9 2658.86  2386.6 2669.25  2469.9  2668.7  2501.6 2675.67
#Mann= 7 ,-1,0
       0      .1       0    1600    .045       0  1656.1     .08       0
  1771.3    .045       0 1809.62      .1       0  1901.2     .06       0
  2011.5      .1       0
Bank Sta=1600,1809.62
XS Rating Curve= 0 ,0
Exp/Cntr(USF)=0,0
Exp/Cntr=0.3,0.1

Type RM Length L Ch R = 1 ,141722  ,596.9,591.4,584.7
XS GIS Cut Line= 4
2329317.93118834678825.3749432142330013.69987561678436.563029744
2330745.28018648678155.1859871012331435.93292751678144.954094641
#Sta/Elev= 30
       0 2773.08   204.6 2675.82   364.6 2610.57   439.8 2559.78   460.4 2557.85
   529.5 2520.11   561.6 2506.51   593.7 2503.31   748.4 2433.57   838.3 2410.95
   894.4 2387.72  1108.3 2385.66    1164 2396.09  1211.1 2383.18  1299.9 2387.83
  1399.7 2378.44  1494.9 2378.53  1545.4 2385.66  1655.8  2442.9  1675.8 2443.52
  1759.1 2496.19  1815.8  2524.1  1861.9 2558.13  1959.8  2616.5  1975.8 2618.42
  2003.8 2639.21  2023.8 2641.24  2095.8 2676.81  2143.8 2688.85  2271.6 2755.64
#Mann= 5 ,-1,0
       0      .1       0  1399.7    .045       0  1494.9      .1       0
 1600.86     .06       0 1700.86      .1       0
#XS Ineff= 2 , 0
         1153.43 2424.14
Permanent Ineff=
       F       F
Bank Sta=1399.7,1494.9
XS Rating Curve= 0 ,0
Exp/Cntr(USF)=0,0
Exp/Cntr=0.3,0.1

Type RM Length L Ch R = 1 ,141130  ,876.9,869.1,856.5
XS GIS Cut Line= 2
2329809.06202641679321.6217275122331599.64320687678308.664373997
#Sta/Elev= 30
       0 2740.39    44.9 2706.72   205.1 2605.73   334.3 2537.46   352.9 2536.96
   421.8 2503.02   513.7 2447.51   557.4  2428.7   626.4 2379.95   658.9 2376.03
   975.7 2379.23  1000.6 2388.94  1023.8 2379.19  1083.6 2383.46  1106.5 2376.25
  1193.9 2376.25  1313.4 2377.94  1382.3  2411.8  1414.4 2437.18  1432.8 2439.48
  1446.7 2455.31  1543.1 2528.63  1556.9 2530.16  1570.7 2543.26  1676.4 2601.08
  1690.2 2601.13  1754.9 2642.82  1906.2    2706  2007.4  2765.5  2057.2 2782.23
#Mann= 6 ,-1,0
       0      .1       0  1106.5    .045       0  1193.9    .025       0
    1210      .1       0    1320     .06       0    1430      .1       0
#XS Ineff= 2 , 0
            1000 2421.55
Permanent Ineff=
       F       F
Bank Sta=1106.5,1193.9
XS Rating Curve= 0 ,0
Exp/Cntr(USF)=0,0
Exp/Cntr=0.3,0.1

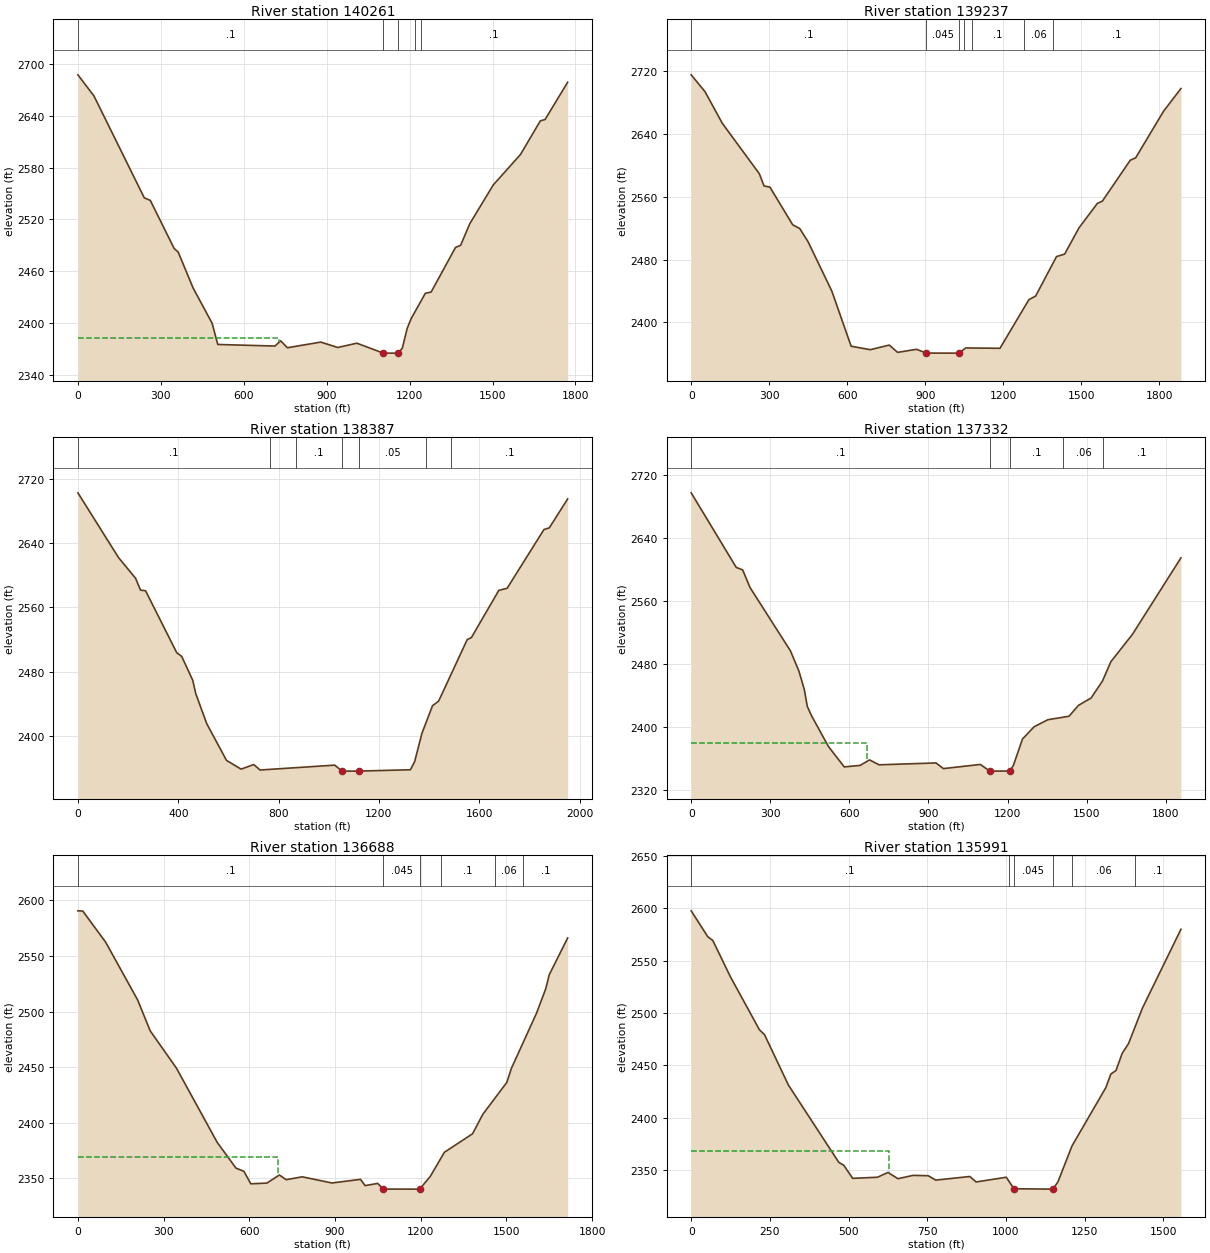
Type RM Length L Ch R = 1 ,140261  ,1022.5,1024.3,1027.6
XS GIS Cut Line= 2
2330540.64233728679950.8831137872331983.33917411678922.577921582
#Sta/Elev= 30
       0 2687.04    58.1 2662.65   240.1 2545.02   261.9 2542.06   348.2 2486.52
   362.9 2482.33   416.7 2440.97   485.6 2400.16     506 2375.68   712.8 2373.87
   733.4 2379.87     758 2371.92   878.5 2378.43   940.2  2372.2  1009.1 2377.18
    1105 2365.69  1159.5 2365.69  1173.9 2371.74  1191.1 2394.13  1205.4 2405.39
  1256.9 2434.78  1277.9 2436.24    1366 2487.66  1384.6 2490.22  1417.6 2515.04
  1502.5 2559.83  1601.2 2595.08  1672.9 2633.86  1690.1 2635.44  1771.7 2678.43
#Mann= 5 ,-1,0
       0      .1       0    1105    .045       0  1159.5     .07       0
    1220     .06       0    1240      .1       0
#XS Ineff= 2 , 0
          727.48  2383.3
Permanent Ineff=
       F       F
Bank Sta=1105,1159.5
XS Rating Curve= 0 ,0
Exp/Cntr(USF)=0,0
Exp/Cntr=0.3,0.1

Type RM Length L Ch R = 1 ,139237  ,843.2,850.4,860.4
XS GIS Cut Line= 2
2331123.86020749 680656.883693512332766.07894728679736.013372132
#Sta/Elev= 30
       0  2715.2    52.9 2693.87   119.6 2653.49   261.8 2589.36   280.1 2573.71
   302.7 2572.21   390.2 2524.24   417.3  2519.5   449.6 2502.51   540.7 2439.77
   614.9 2369.64   688.3 2365.22   761.6 2371.08   793.7 2361.79   866.3 2365.71
   903.8 2360.88  1029.9 2360.84  1055.1 2367.43  1187.1 2366.99  1298.2 2428.86
  1324.3 2433.54  1404.5 2483.78  1435.8 2486.95  1490.8 2520.28  1561.4 2551.44
  1580.8 2554.38    1688 2606.47  1708.7 2609.49  1815.9 2668.79  1882.8 2697.75
#Mann= 7 ,-1,0
       0      .1       0   903.8    .045       0  1029.9      .1       0
    1050    .025       0    1080      .1       0    1280     .06       0
    1390      .1       0
Bank Sta=903.8,1029.9
XS Rating Curve= 0 ,0
Exp/Cntr(USF)=0,0
Exp/Cntr=0.3,0.1

Type RM Length L Ch R = 1 ,138387  ,1044.8,1054.3,1067.9
XS GIS Cut Line= 3
2331282.45454062681091.7391230492331829.86078721681107.086961739
2333170.23869944680687.579370889
#Sta/Elev= 30
       0 2702.76   161.8 2622.08   229.8 2596.31   249.8 2581.48   269.8 2580.66
   393.9 2503.51   413.9 2498.82   457.9 2468.94   469.9 2452.33   513.9 2414.77
   592.5  2369.2   650.6 2358.34   700.9 2364.06   726.1 2357.25  1023.7 2363.31
    1053 2355.88  1055.4 2355.85  1120.1 2355.89  1325.4 2357.57  1342.2  2367.6
  1371.5 2403.13  1413.5 2437.43  1437.9 2443.12  1551.8  2519.8  1568.5 2522.31
  1677.9 2581.18    1711 2583.79  1857.7 2657.02    1879 2659.11  1952.1 2695.16
#Mann= 7 ,-1,0
       0      .1       0  767.62     .07       0  867.62      .1       0
    1053    .045       0  1120.1     .05       0 1387.62     .06       0
 1487.62      .1       0
Bank Sta=1053,1120.1
XS Rating Curve= 0 ,0
Exp/Cntr(USF)=0,0
Exp/Cntr=0.3,0.1

Type RM Length L Ch R = 1 ,137332  ,644.6,644.4,640.1
XS GIS Cut Line= 4
2331318.26616423682007.4934981972331737.77375507681961.449982128
2332847.93408696681987.0297132772333134.42707583682140.508100173
#Sta/Elev= 30
       0 2697.58   170.9 2602.65   195.1 2599.54   223.2 2577.04   376.2 2496.64
   408.3 2471.03   428.9 2447.55   440.4 2425.81   456.4 2413.95   520.5  2374.8
   580.5 2348.85   640.5 2350.71   676.5 2357.76   712.5  2351.5   928.6 2353.87
   956.6 2346.68  1096.8 2351.96  1132.6 2343.46  1208.6 2343.59  1221.9  2350.6
  1256.6 2384.34  1300.7 2399.93  1352.7 2408.88  1433.1 2413.29  1468.7 2427.12
  1516.7 2436.49    1560 2458.14  1591.7 2482.66  1673.4 2517.43  1857.5 2614.84
#Mann= 5 ,-1,0
       0      .1       0  1132.6    .045       0  1208.6      .1       0
 1412.03     .06       0 1562.48      .1       0
#XS Ineff= 2 , 0
          667.15 2379.31
Permanent Ineff=
       F       F
Bank Sta=1132.6,1208.6
XS Rating Curve= 0 ,0
Exp/Cntr(USF)=0,0
Exp/Cntr=0.3,0.1

Type RM Length L Ch R = 1 ,136688  ,690.4,696.9,690.9
XS GIS Cut Line= 2
2331267.10670193682580.4794759432332980.94868893682631.638938241
#Sta/Elev= 30
       0  2590.6    17.1  2590.4    97.1 2562.43   209.2  2510.4   253.2 2482.59
   345.2 2448.98   487.4 2382.39   553.3 2359.13   581.3 2356.21   605.3    2345
   661.4 2345.59   705.4  2352.9   729.4  2348.7   785.4 2351.26   889.5 2345.72
   989.5 2348.99  1005.5 2343.35  1049.5 2345.34  1069.5 2340.22  1196.6 2340.19
  1233.5 2351.55  1283.2 2373.37  1381.7 2389.98  1417.7 2407.54  1501.7 2436.23
  1517.7 2448.85  1605.8 2498.58    1638 2520.49  1650.3 2533.17  1714.6 2566.18
#Mann= 6 ,-1,0
       0      .1       0  1069.5    .045       0  1196.6    .025       0
    1270      .1       0    1460     .06       0    1560      .1       0
#XS Ineff= 2 , 0
          700.51 2369.31
Permanent Ineff=
       F       F
Bank Sta=1069.5,1196.6
XS Rating Curve= 0 ,0
Exp/Cntr(USF)=0,0
Exp/Cntr=0.3,0.1

Type RM Length L Ch R = 1 ,135991  ,521.7,520.6,519.6
XS GIS Cut Line= 2
2331323.38211046683260.9003245162332878.62976434683317.175733045
#Sta/Elev= 30
       0 2597.45    52.8 2572.72    68.8 2569.13   124.6 2534.56   216.9 2483.97
   233.1 2479.29     309 2431.22   469.1  2357.5   485.1 2354.67   513.1 2342.27
     592 2343.32   625.2 2347.89   657.2 2341.93   705.3 2345.11   753.3 2344.76
   777.3 2340.59   885.4 2344.03   905.4 2338.82  1001.4 2343.31  1025.5 2332.33
  1149.5 2331.98  1165.6 2338.98  1210.1 2373.16  1317.7 2428.84  1333.7 2441.83
  1349.7 2445.02  1369.7 2461.54  1389.7 2470.73  1433.7 2504.48  1556.3 2579.85
#Mann= 6 ,-1,0
       0      .1       0    1010    .025       0  1025.5    .045       0
  1149.5      .1       0    1210     .06       0    1410      .1       0
#XS Ineff= 2 , 0
          628.45 2368.79
Permanent Ineff=
       F       F
Bank Sta=1025.5,1149.5
XS Rating Curve= 0 ,0
Exp/Cntr(USF)=0,0
Exp/Cntr=0.3,0.1

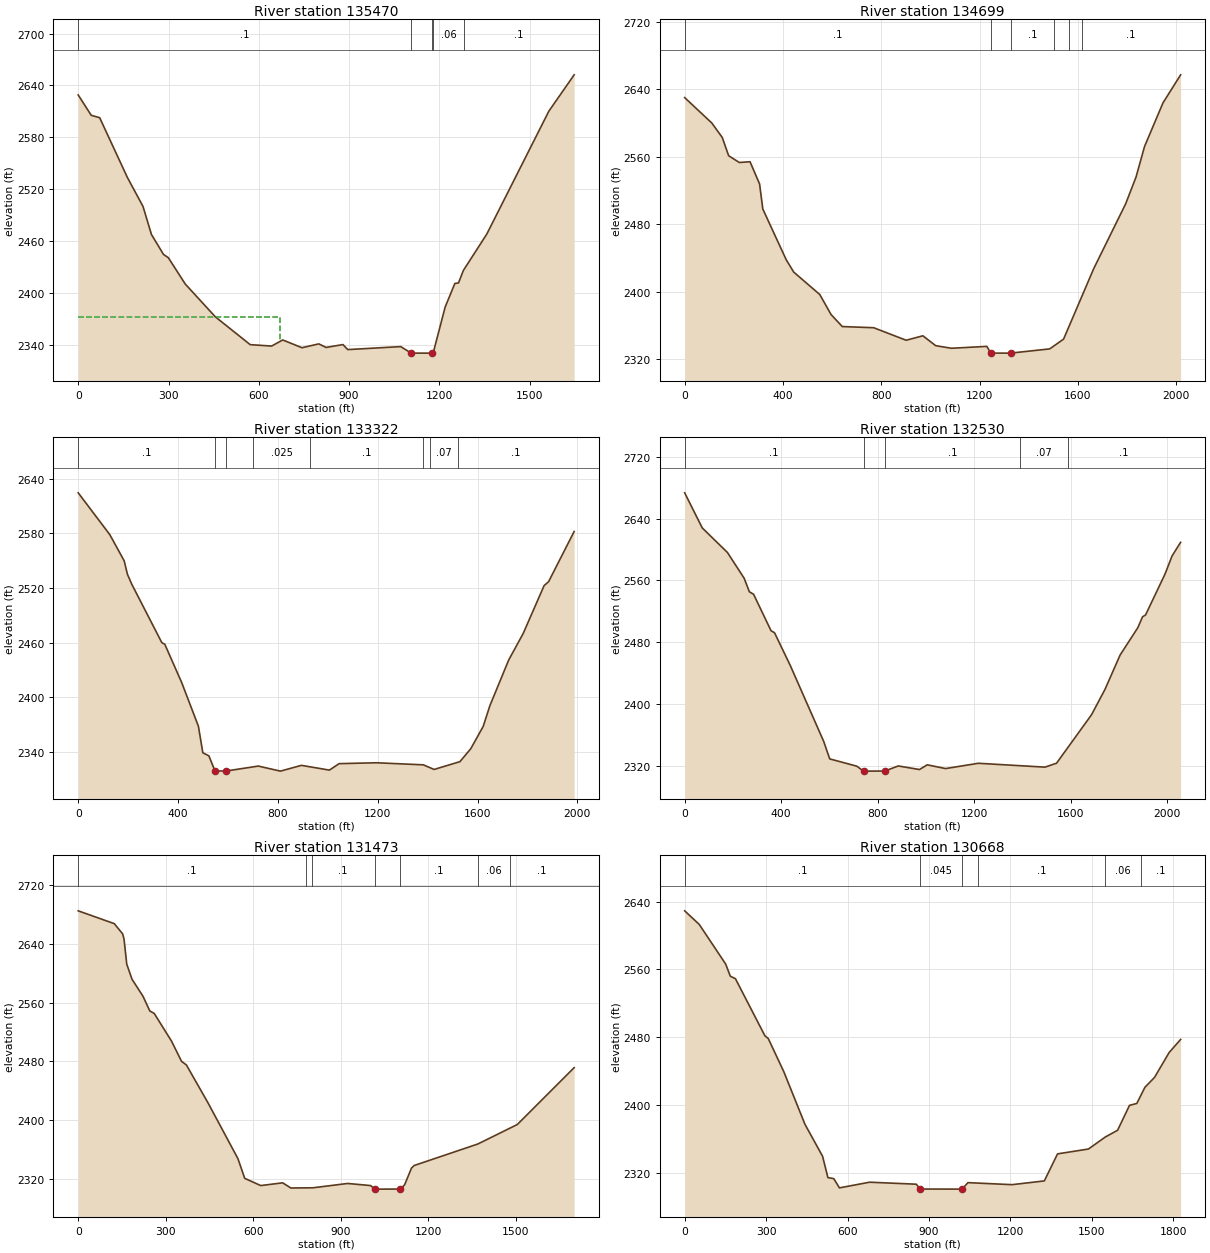
Type RM Length L Ch R = 1 ,135470  ,775.4,771.3,768.4
XS GIS Cut Line= 2
2331256.87480947683798.0746786532332904.20949549683828.770356032
#Sta/Elev= 30
       0 2629.07    43.3 2605.54    71.3 2602.82   163.3 2533.86   215.3 2500.36
   243.3 2467.96   283.3    2445   299.4 2441.16   355.8  2410.7   455.4 2372.97
   571.4 2340.78   642.5 2339.15   679.4 2346.21   743.4 2337.24   799.4 2341.67
   823.4 2337.56   879.5 2340.88   895.5 2335.08  1071.5 2338.53    1106 2331.06
  1109.1    2331  1174.4    2331  1179.5 2331.46  1219.1 2384.22  1251.3 2411.41
  1263.5  2412.1  1279.5 2426.41  1357.4 2468.44  1563.6 2610.36  1647.6  2652.3
#Mann= 5 ,-1,0
       0      .1       0    1106    .045       0  1174.4      .1       0
    1180     .06       0    1280      .1       0
#XS Ineff= 2 , 0
          671.91 2372.41
Permanent Ineff=
       F       F
Bank Sta=1106,1174.4
XS Rating Curve= 0 ,0
Exp/Cntr(USF)=0,0
Exp/Cntr=0.3,0.1

Type RM Length L Ch R = 1 ,134699  ,1406,1377.5,1348.9
XS GIS Cut Line= 4
2331420.58508882685210.0758380982331671.26645409684616.626075433
2332571.67299054684570.5825593642332955.36895779684294.321462951
#Sta/Elev= 30
       0 2630.36   110.3 2600.24     153 2583.04     179 2561.38   222.4 2553.35
     266 2554.25   304.9 2527.89     318 2498.19   413.5 2437.83   443.9 2423.31
   549.9 2396.71   595.9 2372.93   641.4 2358.69   769.3 2357.31   901.5 2342.45
   969.6 2347.73  1021.6 2336.02  1085.7 2332.93  1229.9 2335.17  1245.9 2327.19
    1326 2327.16  1326.6 2327.17  1485.8 2332.19  1542.3 2343.81  1664.6 2427.22
  1794.7 2504.17  1837.2 2536.15  1871.7 2572.29  1946.7    2624  2018.6 2657.37
#Mann= 6 ,-1,0
       0      .1       0  1245.9    .045       0  1326.6      .1       0
 1504.22     .06       0 1565.81     .07       0 1615.81      .1       0
Bank Sta=1245.9,1326.6
XS Rating Curve= 0 ,0
Exp/Cntr(USF)=0,0
Exp/Cntr=0.3,0.1

Type RM Length L Ch R = 1 ,133322  ,802.2,791.9,779.3
XS GIS Cut Line= 2
2332522.81380247686319.0573015222333384.74842328684528.885396765
#Sta/Elev= 30
       0 2624.28   126.4 2578.47   184.1 2549.71   197.2  2534.9   215.2 2523.65
     335 2459.85     347 2458.05     415 2415.79   481.6 2368.07   499.3 2338.95
   523.4 2335.64   548.1    2319   592.8 2318.98   721.6 2324.39   810.1 2318.84
   894.4 2325.18  1006.3 2319.96  1045.4 2327.06  1195.1 2328.01  1382.8 2325.75
  1425.8 2320.68  1529.3 2329.23  1572.7 2343.43  1622.5 2367.91  1649.1  2390.5
  1724.6 2440.76  1782.7 2469.89  1866.7 2522.54  1884.4  2526.7  1986.9 2581.83
#Mann= 8 ,-1,0
       0      .1       0   548.1    .045       0   592.8      .1       0
     700    .025       0     930      .1       0    1380     .06       0
    1410     .07       0    1520      .1       0
Bank Sta=548.1,592.8
XS Rating Curve= 0 ,0
Exp/Cntr(USF)=0,0
Exp/Cntr=0.3,0.1

Type RM Length L Ch R = 1 ,132530  ,1023.9,1056.3,1070.8
XS GIS Cut Line= 4
2333330.87750948686588.4118705252333558.79291402686045.558816073
2333546.36116468 685046.874952542333695.54215674684603.475892797
#Sta/Elev= 30
       0 2673.52    72.9 2628.04     177 2596.31   246.4 2562.93   268.1 2545.32
   285.5 2542.16   357.9  2494.9   372.3  2492.3   437.3  2450.1   576.2 2351.46
   601.1 2328.84   713.1 2319.43   741.1 2312.99   829.2 2313.08   885.2 2319.68
   973.2 2315.06  1005.2 2321.17  1081.2  2316.3  1217.2 2323.16  1493.2 2318.15
  1541.2 2323.27  1686.4 2386.19  1741.9 2418.89  1804.5 2463.37  1877.7 2498.68
  1897.4 2512.82  1910.1 2515.36  1990.2 2567.98  2019.8 2591.72  2055.3 2609.42
#Mann= 5 ,-1,0
       0      .1       0   741.1    .045       0   829.2      .1       0
 1388.76     .07       0 1587.52      .1       0
Bank Sta=741.1,829.2
XS Rating Curve= 0 ,0
Exp/Cntr(USF)=0,0
Exp/Cntr=0.3,0.1

Type RM Length L Ch R = 1 ,131473  ,794.8,805.5,807.5
XS GIS Cut Line= 2
2334002.19197376686816.3272750662334868.27051101685353.524769558
#Sta/Elev= 30
       0 2685.24   123.5 2667.78   152.4 2653.77   157.1 2646.56   166.4  2612.5
   184.5 2591.86   222.1 2568.66   245.4 2548.65   260.7 2545.19   319.8 2507.53
   354.1 2479.92   370.9 2474.93   445.3 2422.99   547.5 2347.13   570.8 2320.25
   625.7 2310.38   700.9 2314.12   728.8 2307.08   804.7 2307.35   923.5 2313.25
  1002.3 2310.39    1017 2305.62  1022.8 2305.53  1104.5 2305.62  1118.8 2311.43
  1142.5 2334.25  1151.8 2337.78    1370 2367.12  1505.1 2393.67    1700 2471.28
#Mann= 7 ,-1,0
       0      .1       0     780    .025       0     800      .1       0
    1017    .045       0  1104.5      .1       0    1370     .06       0
    1480      .1       0
Bank Sta=1017,1104.5
XS Rating Curve= 0 ,0
Exp/Cntr(USF)=0,0
Exp/Cntr=0.3,0.1

Type RM Length L Ch R = 1 ,130668  ,697.4,698.2,692.8
XS GIS Cut Line= 2
2334462.16669929687176.8480058852335692.90988381685825.931244425
#Sta/Elev= 30
       0 2629.19    53.7 2613.16   151.1 2566.39   168.2  2552.1   187.1 2549.12
   295.7  2481.8     308 2478.58   365.3 2439.48   443.3 2377.39   508.2 2339.71
   527.8 2314.55   549.4 2313.34   570.3 2302.44   681.4 2309.14   853.5 2306.78
   867.6 2301.08  1022.2 2300.97  1043.9 2308.62  1206.2 2306.23  1325.3 2310.65
    1374 2342.55  1487.8 2348.26    1550 2362.43  1595.3  2370.4  1639.1 2399.74
  1666.1 2402.03  1695.7 2420.93  1731.4 2432.76  1785.2 2462.06  1827.5 2477.52
#Mann= 6 ,-1,0
       0      .1       0   867.6    .045       0  1022.2    .025       0
    1080      .1       0    1550     .06       0    1680      .1       0
Bank Sta=867.6,1022.2
XS Rating Curve= 0 ,0
Exp/Cntr(USF)=0,0
Exp/Cntr=0.3,0.1