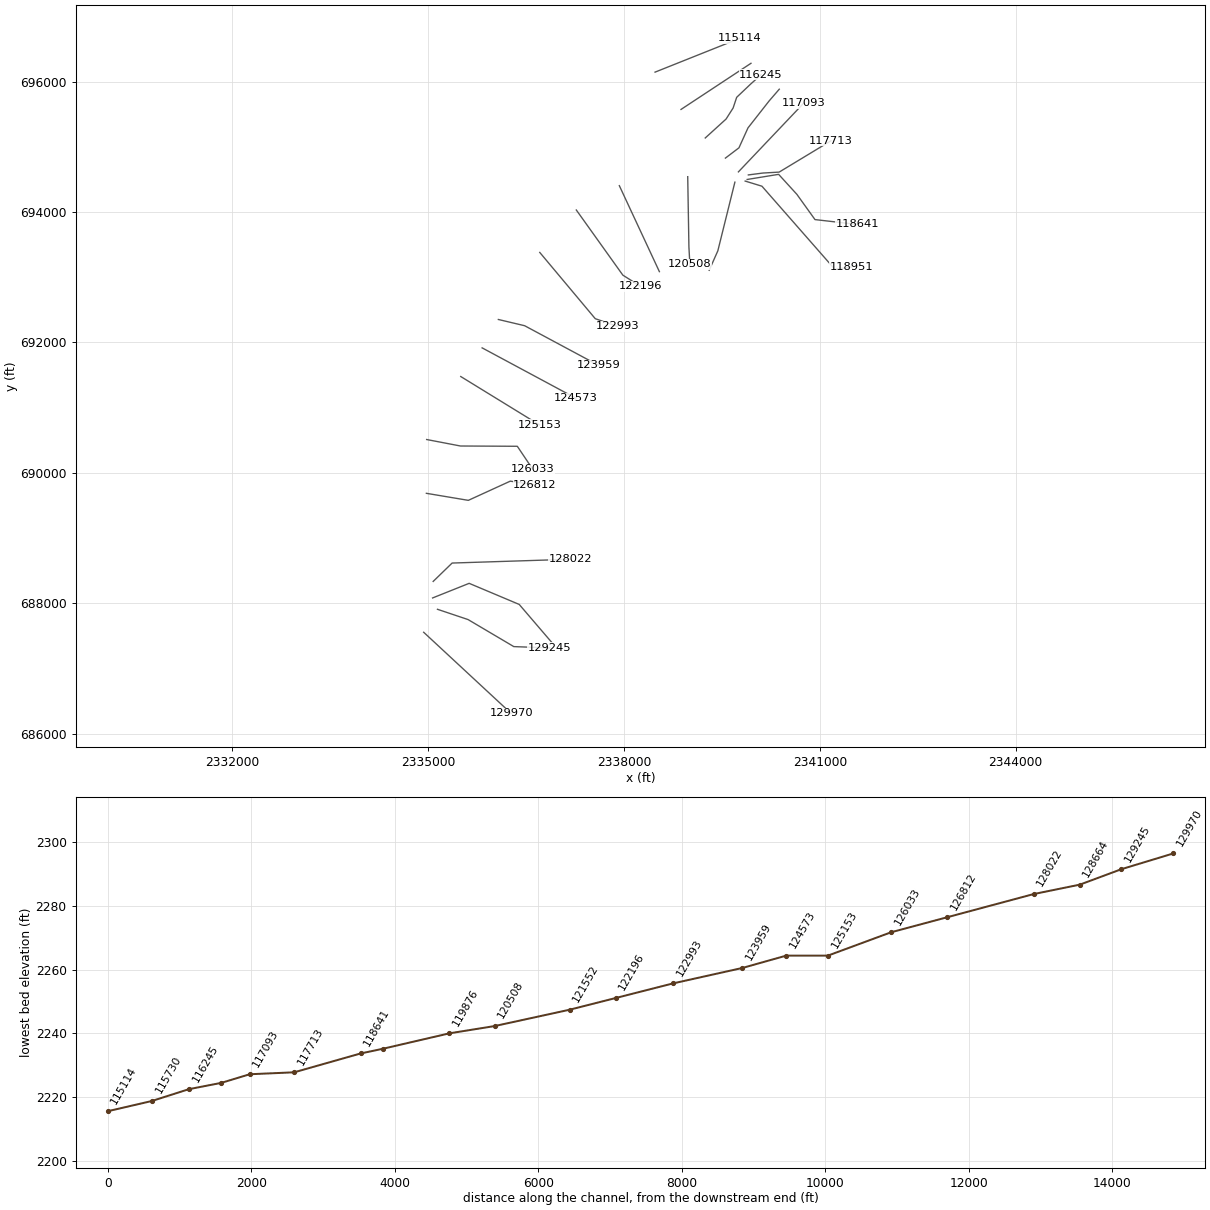
HEC-RAS study SHAVERSFK.prj: SHAVERSFK

--- SHAVERSFK.g01 (geometry) --- (continued)

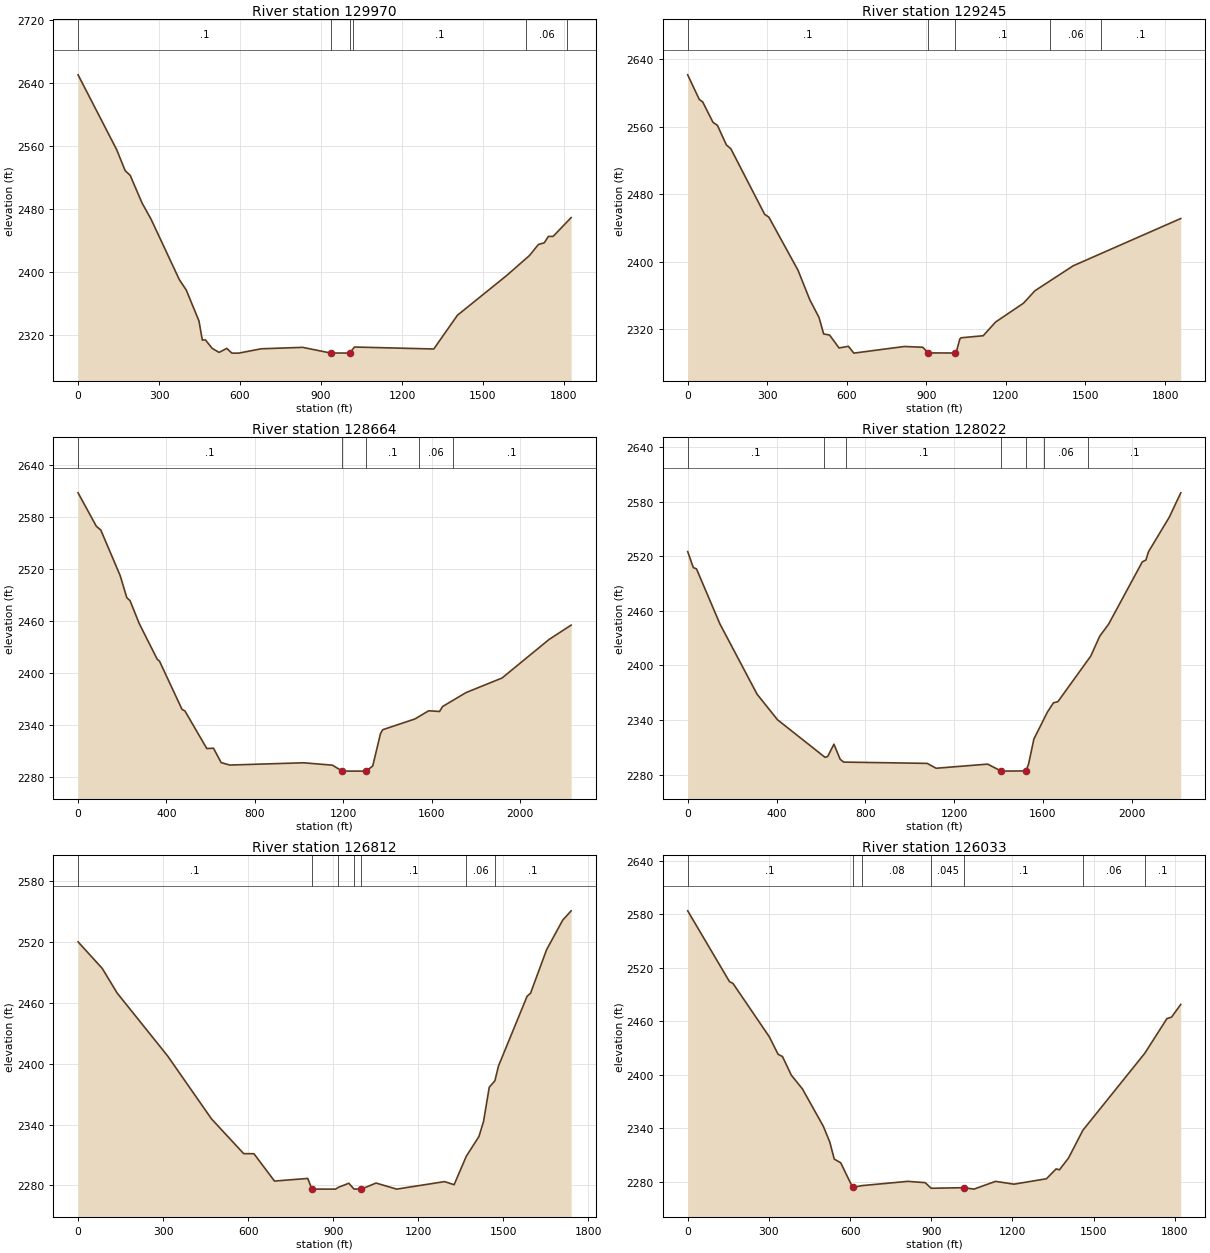
Type RM Length L Ch R = 1 ,129970  ,715.2,724.5,729.5
XS GIS Cut Line= 2
2334934.57317415687558.0883189362336273.05818628686314.913385076
#Sta/Elev= 30
       0 2650.06   143.3 2554.79   174.4 2528.37   193.3 2522.29   236.4 2487.66
   270.7 2466.48   375.4 2389.69   400.9 2376.59     448 2337.32   460.3 2313.12
   471.7  2313.3   497.1 2302.46   522.6 2297.43   550.9  2302.5   569.9 2296.49
     595 2296.47   679.1    2302     832 2303.81   935.7 2296.61  1006.6 2296.57
  1024.1 2304.22  1317.9 2301.73  1405.6 2344.62  1588.3 2395.19  1672.7 2420.56
  1705.4 2434.48  1727.3 2436.66  1742.4 2444.73    1760 2444.79  1826.8 2468.68
#Mann= 6 ,-1,0
       0      .1       0   935.7    .045       0  1006.6    .025       0
    1020      .1       0    1660     .06       0    1810      .1       0
Bank Sta=935.7,1006.6
XS Rating Curve= 0 ,0
Exp/Cntr(USF)=0,0
Exp/Cntr=0.3,0.1

Type RM Length L Ch R = 1 ,129245  ,575.5,580.9,588.8
XS GIS Cut Line= 4
2335145.91291291687910.3212168632335614.17547133687752.852391907
2336314.49735074687338.4607472872336865.63823808687317.741165056
#Sta/Elev= 30
       0 2621.34    43.7 2592.18    56.4 2589.32    95.2 2565.18   112.1 2561.46
   145.9 2538.29   162.8 2533.69   290.1 2456.08   306.2 2452.61     416 2389.76
   460.6 2354.68   495.3 2333.77   512.8  2314.2   534.8 2313.02   570.7  2297.7
   606.2  2299.6   626.5 2291.53   817.1  2299.4   886.5 2298.47     907 2291.77
  1007.6  2291.7  1012.3 2292.09  1026.2 2308.25  1030.9 2309.71  1114.3 2312.13
    1161 2328.38  1266.1 2350.67  1309.4 2365.46  1453.8 2395.05  1859.3 2451.06
#Mann= 5 ,-1,0
       0      .1       0     907    .045       0  1007.6      .1       0
 1367.77     .06       0 1557.77      .1       0
Bank Sta=907,1007.6
XS Rating Curve= 0 ,0
Exp/Cntr(USF)=0,0
Exp/Cntr=0.3,0.1

Type RM Length L Ch R = 1 ,128664  ,620.5,642.6,669.1
XS GIS Cut Line= 4
2335071.32241688688084.3657076032335630.75113711688308.137195698
2336397.37567966687984.9117128942336915.36523544687379.899911749
#Sta/Elev= 30
       0 2607.92    82.8 2569.28   102.8 2564.99   190.5  2512.4   220.6 2486.86
   235.2 2483.45   276.6 2457.12   358.2  2415.8   368.4 2413.65   470.5  2357.9
   483.4  2356.2   582.5 2312.74   612.8 2313.11   647.5 2296.51   686.5 2293.69
  1020.8  2296.3    1151 2293.53  1195.2 2286.72    1303 2286.67  1333.4 2292.67
  1368.1 2329.76  1378.4 2334.46  1524.2 2346.88  1586.4 2356.33  1635.6 2355.53
  1649.1 2361.22  1755.4 2377.33  1918.6 2394.19  2131.3 2438.69    2231 2455.22
#Mann= 5 ,-1,0
       0      .1       0  1195.2    .045       0    1303      .1       0
  1544.5     .06       0  1694.5      .1       0
Bank Sta=1195.2,1303
XS Rating Curve= 0 ,0
Exp/Cntr(USF)=0,0
Exp/Cntr=0.3,0.1

Type RM Length L Ch R = 1 ,128022  ,1192.4,1210.1,1227.5
XS GIS Cut Line= 3
2335080.07651755688337.5058913792335370.15066879 688619.29220972
2337185.18607222688677.307039967
#Sta/Elev= 30
       0 2525.18    25.3 2507.64    39.7 2506.12   145.1 2445.64   312.4 2368.35
   404.3 2340.27   618.5  2298.9   630.5 2299.84   658.6 2313.36   686.6 2296.76
   702.6 2293.66  1078.4 2292.24  1118.8 2286.88  1350.9 2291.44 1409.79 2284.01
  1410.9 2283.72  1523.42283.966    1535 2291.42    1559 2319.01    1620 2348.71
  1647.1 2358.84  1667.1  2360.1  1815.2 2410.32  1855.2 2431.99  1895.2 2445.25
  2047.3 2513.95  2063.3 2515.81  2075.3  2525.1  2168.9 2563.09  2220.4 2589.81
#Mann= 7 ,-1,0
       0      .1       0  614.41     .08       0  714.41      .1       0
 1409.79    .045       0  1523.4      .1       0 1604.41     .06       0
 1804.41      .1       0
Bank Sta=1409.79,1523.4
XS Rating Curve= 0 ,0
Exp/Cntr(USF)=0,0
Exp/Cntr=0.3,0.1

Type RM Length L Ch R = 1 ,126812  ,791.3,778.3,695.6
XS GIS Cut Line= 4
2334976.01233862689688.0613722812335618.31938778 689580.31954468
2336260.62643694 689874.537612362336637.72283354689816.522782114
#Sta/Elev= 30
       0 2520.15    85.3 2493.97     138 2469.65   316.5 2407.47   470.6 2345.67
   584.2 2311.41   620.5  2311.3   692.9 2284.36   810.2 2286.97   824.9 2276.45
   908.5 2276.42   917.3 2278.07   955.1 2282.22   973.2 2276.51   999.1 2276.44
  1051.1 2282.41    1124 2276.44    1293 2283.85  1326.5 2280.77  1369.5 2308.85
    1414 2328.25  1430.2 2342.96  1450.4  2376.8  1470.4 2383.25  1482.8 2397.62
  1583.9  2466.5  1596.1 2469.52  1652.7 2512.41  1709.5 2541.55  1739.3 2550.73
#Mann= 7 ,-1,0
       0      .1       0   824.9    .045       0   917.3     .08       0
   973.2    .045       0   999.1      .1       0  1369.5     .06       0
  1470.4      .1       0
Bank Sta=824.9,999.1
XS Rating Curve= 0 ,0
Exp/Cntr(USF)=0,0
Exp/Cntr=0.3,0.1

Type RM Length L Ch R = 1 ,126033  ,892.3,880.6,683.8
XS GIS Cut Line= 4
2334980.15625506690512.7007450752335498.14581084690413.246750366
2336368.36826454 690409.102833922336604.57150197690056.869935993
#Sta/Elev= 30
       0 2584.08   154.8 2504.46     167 2502.76   301.4 2442.78     334 2423.12
   350.3 2420.49   382.9 2399.65   424.1 2384.14     501 2342.36   524.9 2324.71
   541.5 2305.47   565.4  2301.3   609.2 2273.82   645.5 2275.71   813.5 2280.46
   877.5    2279   899.8 2272.69  1021.5 2273.36  1057.5 2271.73  1137.5 2280.45
  1205.5 2277.29  1325.5 2283.36  1361.4 2294.46  1373.5 2293.41  1407.2 2306.68
  1460.2 2337.84  1688.7 2424.14  1770.8 2463.16  1787.7 2464.77  1821.8 2479.04
#Mann= 7 ,-1,0
       0      .1       0   609.2    .045       0   645.5     .08       0
   899.8    .045       0  1021.5      .1       0  1460.2     .06       0
  1688.7      .1       0
Bank Sta=609.2,1021.5
XS Rating Curve= 0 ,0
Exp/Cntr(USF)=0,0
Exp/Cntr=0.3,0.1

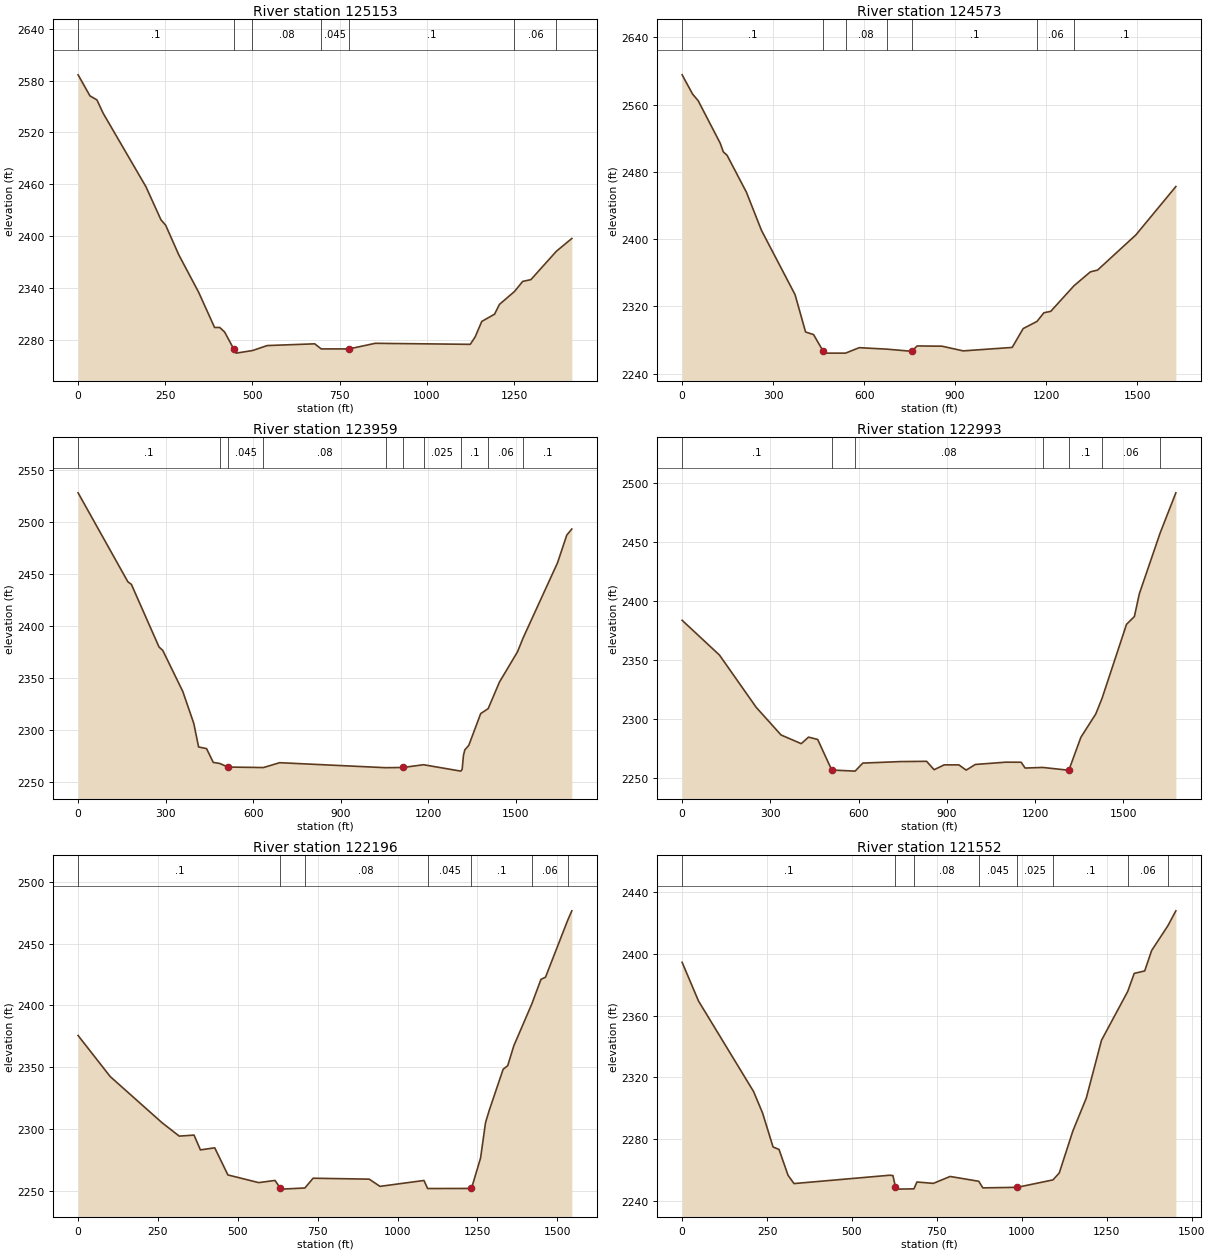
Type RM Length L Ch R = 1 ,125153  ,577,579.8,590.3
XS GIS Cut Line= 2
2335502.28972728691478.2332770392336708.16941313690736.472233169
#Sta/Elev= 30
       0 2586.81    34.1  2562.4    53.9 2557.81    71.9 2542.28   194.8    2457
   237.7 2418.78   251.1 2412.62   288.7 2378.32   345.6 2335.02   391.4 2294.11
   406.1 2294.16   420.2 2288.86  445.822269.593     453 2264.41     500 2267.39
   542.3 2273.17   678.5 2275.19   697.2 2269.28   777.1 2269.31   852.2 2275.79
  1124.5  2274.6  1138.7 2283.27  1157.5 2301.11  1194.3 2309.56  1208.3 2320.89
  1251.4 2335.81  1274.9  2347.5  1298.4 2349.54  1371.6 2382.47  1415.8 2397.22
#Mann= 7 ,-1,0
       0      .1       0  445.82    .045       0     500     .08       0
   697.2    .045       0   777.1      .1       0  1251.4     .06       0
  1371.6      .1       0
Bank Sta=445.82,777.1
XS Rating Curve= 0 ,0
Exp/Cntr(USF)=0,0
Exp/Cntr=0.3,0.1

Type RM Length L Ch R = 1 ,124573  ,609.8,613.7,705.1
XS GIS Cut Line= 2
2335829.65912653691917.4884203362337263.45421692691146.719961343
#Sta/Elev= 30
       0  2595.5    34.6 2572.55    52.8  2564.8   125.5 2514.21   135.8 2503.86
   148.2  2499.8   211.9 2455.89   261.7 2410.38   372.4 2333.95     407 2289.55
   433.3 2286.49  465.532266.402   474.7 2264.41   538.7 2264.41   584.1  2270.9
     675 2269.15   756.7 2266.59   774.9 2272.96   856.6 2272.67   926.6 2267.08
  1088.2 2271.19  1124.4 2293.62    1170 2302.14  1192.7 2312.43  1215.4 2314.14
  1291.9 2344.54    1346 2361.11  1369.6 2363.18  1495.9 2405.02  1627.8 2462.58
#Mann= 7 ,-1,0
       0      .1       0  465.53    .045       0   538.7     .08       0
     675    .045       0   756.7      .1       0    1170     .06       0
  1291.9      .1       0
Bank Sta=465.53,756.7
XS Rating Curve= 0 ,0
Exp/Cntr(USF)=0,0
Exp/Cntr=0.3,0.1

Type RM Length L Ch R = 1 ,123959  ,971,966,640.2
XS GIS Cut Line= 3
 2336078.2941133692352.5996471872336480.25400859692257.289568924
2337607.39928195691652.277767779
#Sta/Elev= 30
       0 2528.27   170.5 2442.73   182.8 2440.12   277.4 2379.95   290.2  2376.7
     359 2337.09   396.6 2306.38     413 2283.79   440.3  2282.2   463.3 2268.93
   485.7 2267.89   513.6 2264.44   635.5 2263.98   690.8 2268.64  1054.2 2263.83
 1113.212264.031  1184.2 2266.68  1311.9 2260.53  1316.4 2262.16    1321  2275.7
  1325.5 2280.93  1339.1 2285.26    1380 2315.89  1405.7 2320.68  1444.1 2346.09
  1506.2 2375.32  1525.3 2388.58  1643.3  2460.9  1675.1 2487.59  1692.4 2493.46
#Mann= 10 ,-1,0
       0      .1       0   485.7    .025       0   513.6    .045       0
   635.5     .08       0  1054.2    .045       0 1113.21      .1       0
  1184.2    .025       0  1311.9      .1       0  1405.7     .06       0
  1525.3      .1       0
Bank Sta=513.6,1113.21
XS Rating Curve= 0 ,0
Exp/Cntr(USF)=0,0
Exp/Cntr=0.3,0.1

Type RM Length L Ch R = 1 ,122993  ,799.2,796.8,789.6
XS GIS Cut Line= 3
2336712.31332957693380.2909258442337561.81620104692365.031396525
2337897.47343319692249.001736032
#Sta/Elev= 30
       0 2383.71   127.1 2354.17     252  2309.8   336.4 2286.37   404.9 2279.01
   429.9 2284.56     461 2282.56  508.732256.621   588.2 2255.69   614.3 2262.52
   743.2  2263.8   831.3 2264.01   856.8 2256.89   891.1    2261     941 2260.99
   965.9 2256.55   997.1 2261.35    1101 2263.29  1152.9 2263.24  1166.3  2258.3
    1226 2258.83    1315 2256.43  1355.9 2284.37  1406.7 2304.27  1427.9 2317.45
  1511.1 2380.27  1537.9 2386.92  1554.8  2406.3  1625.4 2457.77  1678.9  2491.9
#Mann= 7 ,-1,0
       0      .1       0  508.73    .045       0   588.2     .08       0
    1226    .045       0    1315      .1       0  1427.9     .06       0
  1625.4      .1       0
Bank Sta=508.73,1315
XS Rating Curve= 0 ,0
Exp/Cntr(USF)=0,0
Exp/Cntr=0.3,0.1

Type RM Length L Ch R = 1 ,122196  ,649.8,643.9,599.7
XS GIS Cut Line= 3
2337271.74204981694030.8858078972337984.49567856693032.201944363
2338253.85024756692862.301370069
#Sta/Elev= 30
       0 2375.65   100.4 2342.41   262.6 2304.99   316.6  2294.1   362.9 2294.92
   382.9 2282.93   427.7 2284.61   468.9 2262.63   565.4  2256.4   616.4 2258.17
  633.31 2251.66     636 2251.12   709.8 2252.04   735.6 2259.96   911.2 2259.22
     945 2253.36  1082.6 2258.14  1094.1 2251.61  1231.3 2251.68  1259.7 2276.28
  1275.3 2305.05  1286.9    2315  1330.4 2348.28  1344.8 2351.25  1363.7 2367.24
    1420 2401.14  1448.8 2421.18    1463 2422.92  1532.5 2469.12  1545.4 2476.74
#Mann= 7 ,-1,0
       0      .1       0  633.31    .045       0   709.8     .08       0
  1094.1    .045       0  1231.3      .1       0    1420     .06       0
  1532.5      .1       0
Bank Sta=633.31,1231.3
XS Rating Curve= 0 ,0
Exp/Cntr(USF)=0,0
Exp/Cntr=0.3,0.1

Type RM Length L Ch R = 1 ,121552  ,1045,1044,747.9
XS GIS Cut Line= 2
2337930.62476476694403.8382880552338543.92439879693086.072858164
#Sta/Elev= 30
       0  2394.5    48.3 2369.39   210.3 2310.74   236.8 2296.79   267.7 2274.78
   285.3 2273.16   311.8 2256.42   329.4 2251.04   611.3 2256.45   620.6 2256.23
  627.99 2248.96   629.4 2247.44   682.4 2247.62   691.2 2252.06   739.7 2251.18
     789 2255.65   873.3 2252.53   885.3 2248.25   986.8 2248.62  1091.7 2253.42
  1110.3 2257.93  1150.3 2285.15  1189.8 2306.45  1234.6 2343.96  1311.9 2375.67
  1330.9 2387.32  1361.8 2388.91  1382.1 2402.12  1430.1 2418.24  1453.5 2427.89
#Mann= 8 ,-1,0
       0      .1       0  627.99    .045       0   682.4     .08       0
   873.3    .045       0   986.8    .025       0  1091.7      .1       0
  1311.9     .06       0  1430.1      .1       0
Bank Sta=627.99,986.8
XS Rating Curve= 0 ,0
Exp/Cntr(USF)=0,0
Exp/Cntr=0.3,0.1

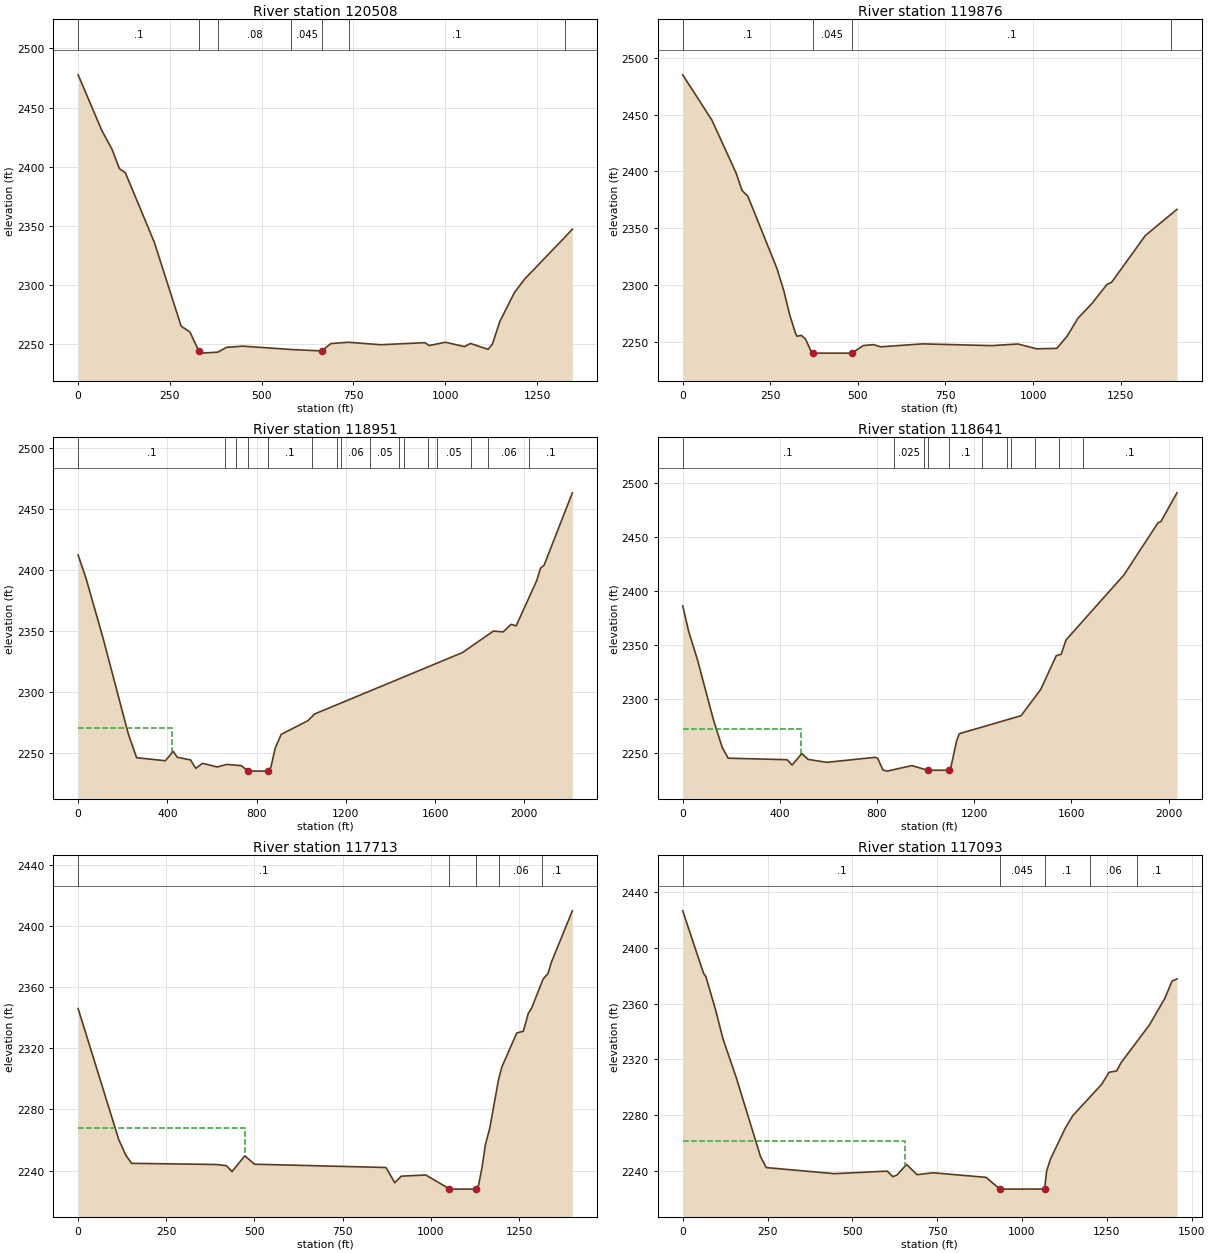
Type RM Length L Ch R = 1 ,120508  ,639,632.6,646.4
XS GIS Cut Line= 3
2338977.80587368694541.6897409012338995.96124337693465.988550995
2339010.86233699693195.796695912
#Sta/Elev= 30
       0 2477.67    64.5 2430.64    92.5 2414.59   112.5 2398.35   128.5 2394.96
   207.4 2336.24   280.6 2265.17   304.6 2260.18   328.6 2244.25   336.6 2242.32
   380.6 2243.16   404.6 2247.24   448.6 2248.22   580.6 2245.38   663.8 2244.17
   688.6  2250.4   736.6  2251.5   824.6 2249.42   944.6 2251.16   956.6 2248.74
  1000.7 2251.51  1052.7 2247.83  1068.7 2250.51  1116.7  2245.5  1128.7 2249.97
  1148.8 2269.05  1188.8 2293.62  1216.9  2305.1  1326.6 2340.55  1346.5 2347.21
#Mann= 7 ,-1,0
       0      .1       0   328.6    .045       0   380.6     .08       0
   580.6    .045       0   663.8    .025       0   736.6      .1       0
  1326.6     .06       0
Bank Sta=328.6,663.8
XS Rating Curve= 0 ,0
Exp/Cntr(USF)=0,0
Exp/Cntr=0.3,0.1

Type RM Length L Ch R = 1 ,119876  ,874.3,925.2,962.8
XS GIS Cut Line= 3
2339700.07708728694457.7092018552339439.01035117693405.154424521
2339306.40502489693106.792440395
#Sta/Elev= 30
       0 2485.07      83 2445.34   152.3 2398.69   169.5 2383.12     186 2378.11
   269.4 2314.22     289 2294.52   305.5 2273.54     322 2257.48   326.1 2254.89
   338.5 2255.66   350.4 2252.47   367.3 2241.02   371.5 2240.03   482.7 2240.03
   515.7 2246.72   544.5  2247.5   565.2 2245.59   684.7 2248.18   882.5 2246.64
   956.7 2248.07  1010.2 2243.85  1067.9 2244.19  1097.6 2255.06  1128.2 2270.74
  1167.6 2283.51  1211.4 2300.61  1224.5 2302.44  1320.8 2343.63    1411 2366.63
#Mann= 4 ,-1,0
       0      .1       0   371.5    .045       0   482.7      .1       0
 1394.45     .06       0
Bank Sta=371.5,482.7
XS Rating Curve= 0 ,0
Exp/Cntr(USF)=0,0
Exp/Cntr=0.3,0.1

Type RM Length L Ch R = 1 ,118951  ,315.1,309.7,306.5
XS GIS Cut Line= 4
2339857.54591224 694474.28486764 2340114.4687319694395.550455162
2341229.18225593693123.3681061792341481.96115915693156.519437749
#Sta/Elev= 30
       0 2412.42    36.2 2392.82   111.5 2344.39   224.5 2265.98   262.1 2246.18
   390.7 2243.71   426.1 2251.41   444.5 2246.53     504 2244.36   527.1 2237.47
   557.9 2241.61   623.1 2238.61   665.4 2240.69   730.8 2239.69     762 2235.26
   851.6  2235.2     864 2238.49   883.5 2254.23   910.1 2265.36    1030 2276.56
  1060.3 2282.09  1721.9 2332.35  1861.5 2350.07  1904.6 2349.34  1940.4 2355.56
  1963.2 2354.34    2056 2391.73  2072.1 2401.52  2088.3 2404.03  2215.1 2463.39
#Mann= 16 ,-1,0
       0      .1       0  658.72    .025       0  708.72      .1       0
     762    .045       0   851.6      .1       0 1048.72     .06       0
 1158.72     .07       0 1178.72     .06       0 1308.72     .05       0
 1438.72      .1       0 1458.72     .05       0 1568.72      .1       0
 1608.72     .05       0 1758.72     .07       0 1838.72     .06       0
 2020.18      .1       0
#XS Ineff= 2 , 0
          420.58 2270.34
Permanent Ineff=
       F       F
Bank Sta=762,851.6
XS Rating Curve= 0 ,0
Exp/Cntr(USF)=0,0
Exp/Cntr=0.3,0.1

Type RM Length L Ch R = 1 ,118641  ,867.9,928.1,991.5
XS GIS Cut Line= 5
2339887.87940388694498.8475363632340369.71802307694577.517654138
2340649.22793493694270.9818159012340926.55898737693883.944209494
2341577.97801915693809.259224959
#Sta/Elev= 30
       0 2386.15    24.6 2362.51    61.1  2336.1   125.9 2281.46   162.4 2255.69
   186.9 2245.67   429.9 2244.27   450.2 2239.34   490.2 2249.93   515.7 2244.59
   592.8 2241.84   791.8 2246.46   802.6 2245.52   824.3 2234.78   841.3 2233.73
   943.7 2238.841007.9012234.569 1097.98 2234.57  1102.1 2235.46  1127.9 2261.81
  1138.7 2268.26  1392.9 2284.87  1473.5 2308.95  1537.8 2340.21    1558 2341.51
  1578.1 2354.77  1816.6 2414.78  1956.6 2462.85  1968.6 2463.97  2034.9  2490.5
#Mann= 11 ,-1,0
       0      .1       0  868.22    .025       0  993.06      .1       0
1007.901    .045       0 1097.98      .1       0 1233.06     .07       0
 1333.06     .05       0 1353.06     .08       0  1449.2      .1       0
  1549.2     .06       0  1649.2      .1       0
#XS Ineff= 2 , 0
          487.36 2272.41
Permanent Ineff=
       F       F
Bank Sta=1007.901,1097.98
XS Rating Curve= 0 ,0
Exp/Cntr(USF)=0,0
Exp/Cntr=0.3,0.1

Type RM Length L Ch R = 1 ,117713  ,615.3,619.9,632.7
XS GIS Cut Line= 4
2339905.94828937694568.5352497272340131.08691164694597.627692744
2340378.04732625694611.8713964432341171.16742568695091.728418123
#Sta/Elev= 30
       0 2346.03   115.2 2260.26   135.3 2249.98   151.5  2244.7   392.4 2243.94
   420.4 2243.14   436.4 2239.29   472.5 2249.61   500.2 2244.13     873 2241.97
   897.6    2232   916.3  2236.3   985.8 2237.081052.5892227.985  1056.5 2227.81
1128.8872227.861  1135.2 2230.19  1145.4 2242.18  1154.8 2256.96  1167.2 2267.79
  1192.2 2299.73  1201.5 2307.78  1243.6 2330.05  1262.3 2331.19  1276.3 2342.79
  1285.7 2346.26  1318.4 2365.35  1332.4 2369.04  1341.8 2376.33  1401.4 2410.03
#Mann= 5 ,-1,0
       0      .1       01052.589    .045       01128.887      .1       0
 1194.38     .06       0 1314.38      .1       0
#XS Ineff= 2 , 0
          473.65 2267.67
Permanent Ineff=
       F       F
Bank Sta=1052.589,1128.887
XS Rating Curve= 0 ,0
Exp/Cntr(USF)=0,0
Exp/Cntr=0.3,0.1

Type RM Length L Ch R = 1 ,117093  ,415.3,395.2,401.2
XS GIS Cut Line= 2
2339753.94800108694615.1780268112340756.77578106695671.876720591
#Sta/Elev= 30
       0 2426.36    61.3 2381.67    68.1 2379.32    96.4 2355.86   118.6 2334.76
   158.6 2306.37   229.3 2250.47   246.3 2242.61   447.2 2238.27   602.8 2240.08
   619.2 2236.12   631.1 2237.23   659.9 2244.87   690.5 2237.56   738.6 2238.89
   894.2 2235.62   934.7  2227.2  1066.6 2227.28  1072.6 2240.22    1084 2248.78
  1127.7 2270.94  1149.8 2279.82  1235.1 2302.28  1256.4  2310.8    1279 2311.77
  1291.9 2317.65  1375.9 2344.82  1421.1  2363.8  1442.1 2376.07  1456.8 2377.68
#Mann= 5 ,-1,0
       0      .1       0   934.7    .045       0  1066.6      .1       0
    1200     .06       0    1340      .1       0
#XS Ineff= 2 , 0
          653.86 2261.64
Permanent Ineff=
       F       F
Bank Sta=934.7,1066.6
XS Rating Curve= 0 ,0
Exp/Cntr(USF)=0,0
Exp/Cntr=0.3,0.1

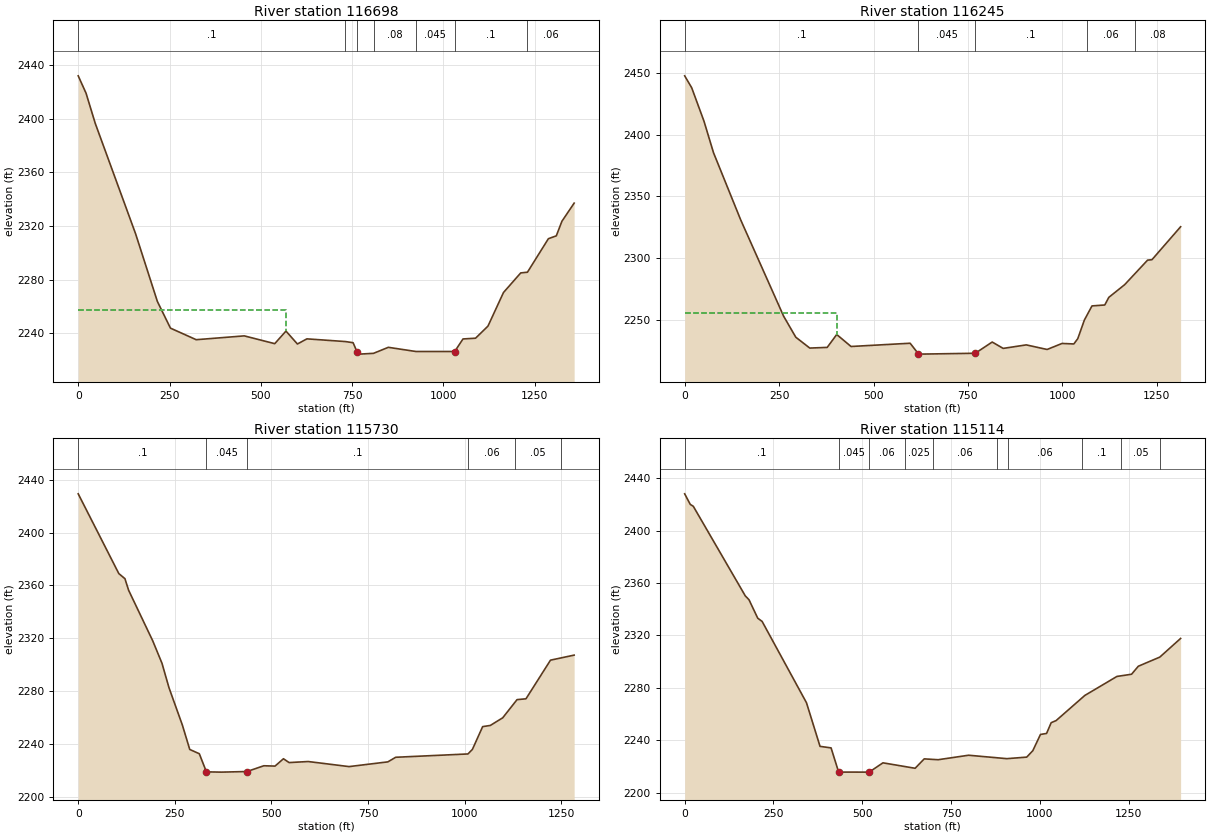
Type RM Length L Ch R = 1 ,116698  ,378.4,452.7,470.4
XS GIS Cut Line= 5
2339555.04001167694826.5177655672339762.23583398694983.986590522
2339900.96817931695289.9534343342340224.27759754 695702.43116603
2340379.76441235695882.559069419
#Sta/Elev= 30
       0  2431.9    21.5 2418.92    46.6 2396.52   157.2 2314.15   216.8 2263.75
   252.6 2243.88   323.1 2235.25   454.8  2238.1   538.2  2232.3     569 2241.67
   600.3 2232.05   626.4 2235.88   731.8 2233.86   752.8 2233.02   763.5 2226.25
     770  2224.5   808.8  2225.1   849.3 2229.57   925.4 2226.44    1031 2226.44
  1053.8  2235.8  1088.2 2236.37  1122.2 2245.38  1164.7 2270.43  1211.9 2285.02
  1230.3 2285.55  1287.7 2310.53  1309.3 2312.64  1324.7 2323.51  1358.2 2337.03
#Mann= 7 ,-1,0
       0      .1       0   731.8    .025       0   763.5    .045       0
   808.8     .08       0   925.4    .045       0    1031      .1       0
  1230.3     .06       0
#XS Ineff= 2 , 0
          568.09 2257.33
Permanent Ineff=
       F       F
Bank Sta=763.5,1031
XS Rating Curve= 0 ,0
Exp/Cntr(USF)=0,0
Exp/Cntr=0.3,0.1

Type RM Length L Ch R = 1 ,116245  ,548,514.6,490.3
XS GIS Cut Line= 6
2339246.40864038695135.1273337642339565.43640637695425.513715396
2339672.84020503695594.1240667022339727.59091886 695758.37620818
2339936.86320252695957.0525171362340100.60569257696104.241321408
#Sta/Elev= 30
       0 2447.54    18.6  2437.9    51.1 2410.88    76.3 2385.42   148.4 2331.02
     262 2253.21   294.2  2236.2   331.2 2227.42   377.4 2227.96   402.6 2238.38
   440.5 2228.69     597 2231.33   618.6 2222.85   620.7 2222.52   769.42223.219
   814.3 2232.29   843.4 2227.15   904.5 2229.99   959.7 2226.28   999.2 2231.15
  1030.4 2230.74  1040.9 2235.04  1058.3 2250.02  1078.5  2261.5  1112.4 2262.25
  1123.1 2268.43    1165 2278.67  1225.7 2298.51  1237.3 2298.86  1313.2 2325.51
#Mann= 5 ,-1,0
       0      .1       0   618.6    .045       0   769.4      .1       0
 1064.45     .06       0 1193.01     .08       0
#XS Ineff= 2 , 0
          404.33 2256.03
Permanent Ineff=
       F       F
Bank Sta=618.6,769.4
XS Rating Curve= 0 ,0
Exp/Cntr(USF)=0,0
Exp/Cntr=0.3,0.1

Type RM Length L Ch R = 1 ,115730  ,624.4,616.1,607.9
XS GIS Cut Line= 2
2338875.24126444695572.5416330612339946.49109991696279.604315044
#Sta/Elev= 30
       0 2429.28   105.1 2368.97   120.9 2365.12   130.5 2356.35   192.8 2318.17
   216.8 2301.17     235 2282.62   269.5 2254.49   288.7 2235.96   313.4 2232.74
   331.8 2219.03   370.2 2218.82   436.8 2219.27   480.4 2223.63   509.5 2223.39
   531.2 2228.94   545.8 2226.05   595.4 2226.83   700.9    2223   801.5 2226.58
   821.7 2230.05  1008.7 2232.56  1020.3 2236.02  1046.8 2253.24  1066.5 2254.11
  1098.7 2259.89  1135.8 2273.64  1158.9 2274.27  1222.4 2303.49  1283.6 2307.31
#Mann= 6 ,-1,0
       0      .1       0   331.8    .045       0   436.8      .1       0
    1010     .06       0    1130     .05       0    1250     .03       0
Bank Sta=331.8,436.8
XS Rating Curve= 0 ,0
Exp/Cntr(USF)=0,0
Exp/Cntr=0.3,0.1

Type RM Length L Ch R = 1 ,115114  ,541.5,539.5,540
XS GIS Cut Line= 2
2338477.62173565696144.2831954582339774.66758331696662.272751232
#Sta/Elev= 30
       0 2428.07    15.7    2420    24.3 2418.55   170.7 2350.16   181.2 2347.18
   205.8  2333.1   218.1 2330.66     343 2268.59   381.2 2235.27   412.3  2234.1
   433.6 2215.63   519.6  2215.6   558.4  2222.7     649 2218.54   674.7 2225.72
   713.7 2225.07   799.6  2228.5   907.3 2225.88   963.3 2227.06   980.5 2231.99
    1002 2244.36  1019.2 2245.14  1032.2 2253.34  1046.1 2254.96  1126.9 2274.14
  1217.4 2288.66  1258.5 2290.33  1277.7 2296.46    1338  2303.4  1396.7 2317.66
#Mann= 10 ,-1,0
       0      .1       0   433.6    .045       0   519.6     .06       0
     620    .025       0     700     .06       0     880     .07       0
     910     .06       0    1120      .1       0    1230     .05       0
    1340     .03       0
Bank Sta=433.6,519.6
XS Rating Curve= 0 ,0
Exp/Cntr(USF)=0,0
Exp/Cntr=0.3,0.1