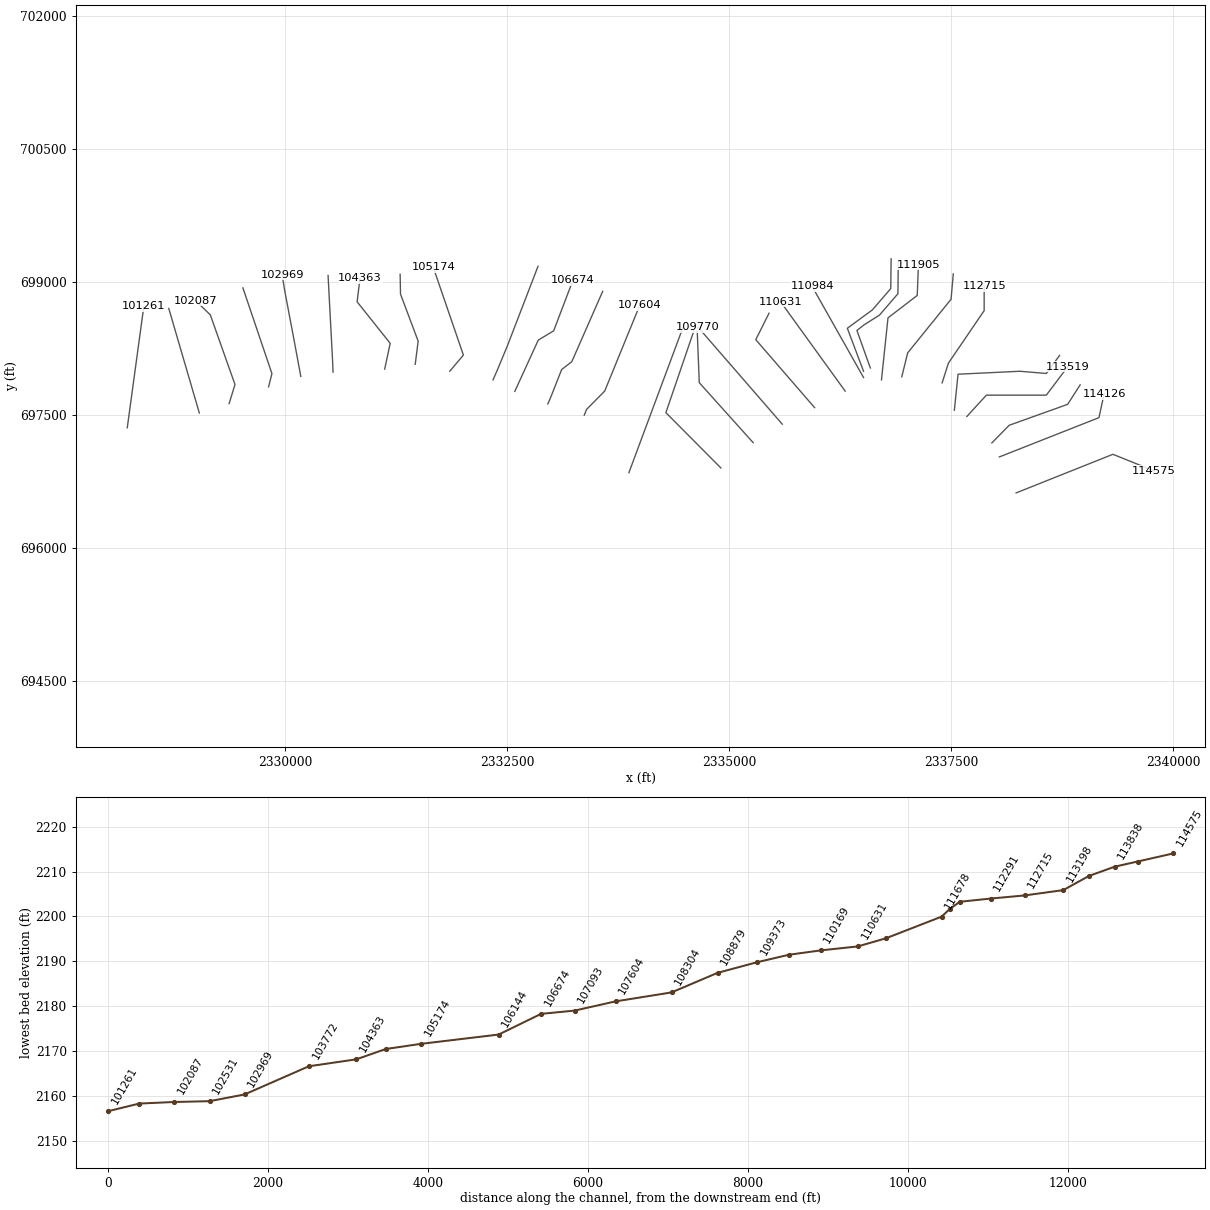
HEC-RAS study SHAVERSFK.prj: SHAVERSFK

--- SHAVERSFK.g01 (geometry) --- (continued)

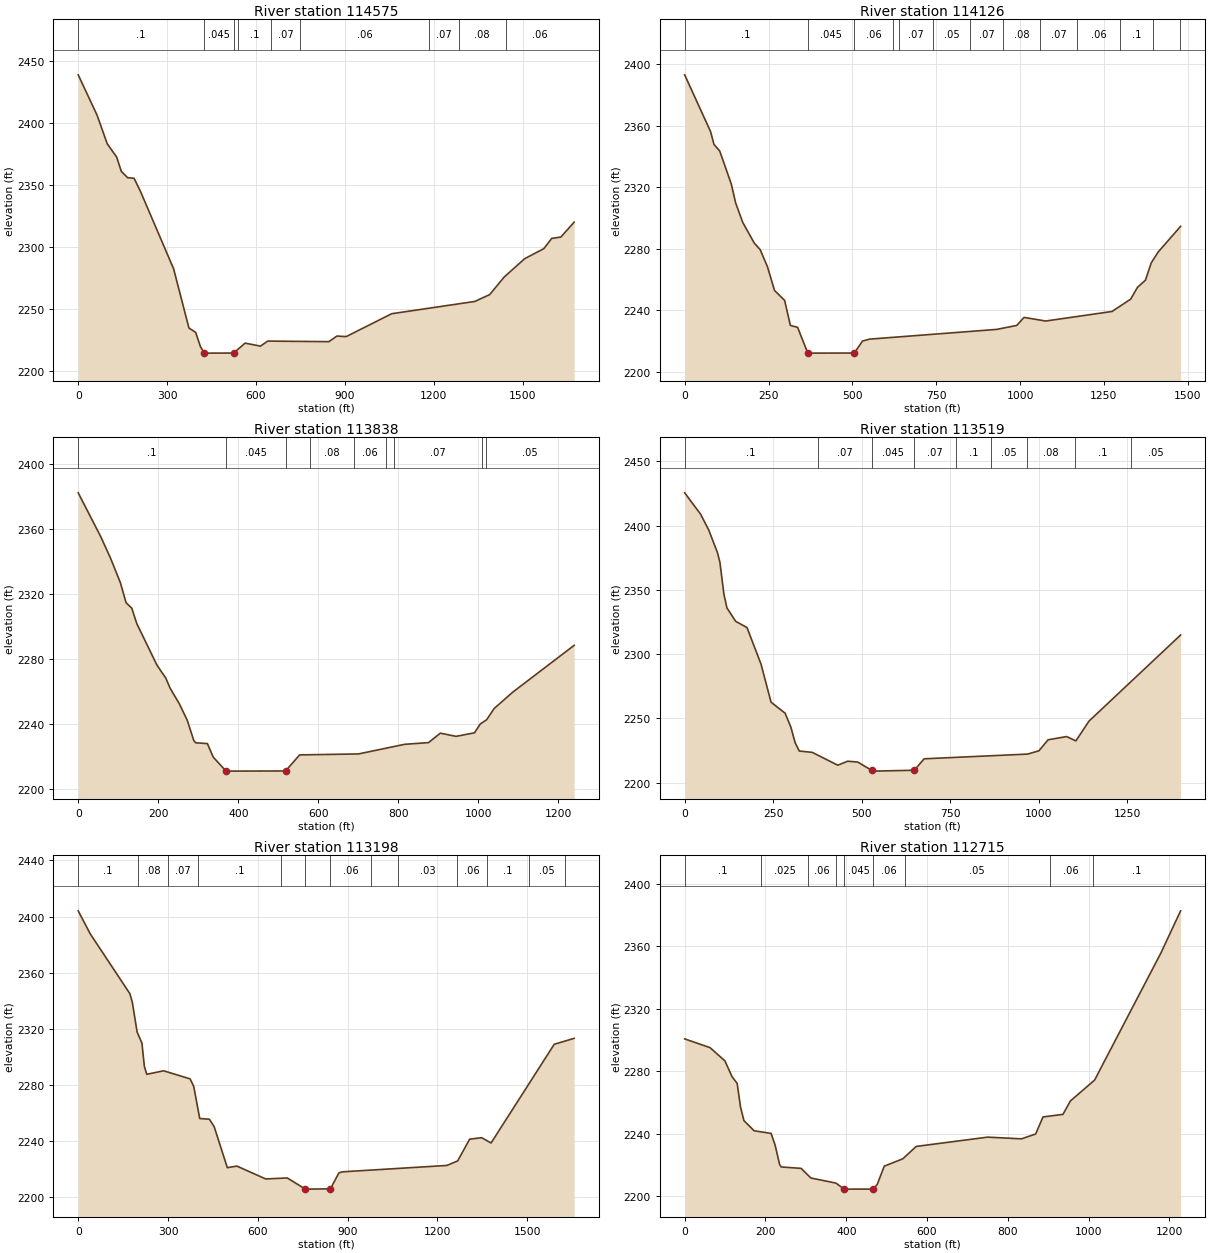
Type RM Length L Ch R = 1 ,114575  ,453.4,448.6,447.1
XS GIS Cut Line= 3
2338233.13066533696624.9775032172339322.98069068697060.088730067
2339787.09933265696873.612489989
#Sta/Elev= 30
       0 2438.96    63.6 2406.41      98 2383.23     130 2372.43   145.4 2360.96
   166.9 2355.83   188.5 2355.35     210 2344.82     322  2282.2   373.7 2234.36
   396.5 2230.81   412.4 2219.35   425.4 2214.24   430.4 2214.06   524.4 2214.12
   563.2 2222.14     615 2219.72   639.7 2223.78   845.9 2223.33   873.3 2227.86
   904.4 2227.41  1057.8  2245.9  1338.6 2255.83  1388.8  2261.4  1437.7 2275.58
  1506.7 2290.37  1571.4 2298.51    1598 2306.78  1628.7 2307.85  1673.7  2319.9
#Mann= 9 ,-1,0
       0      .1       0   425.4    .045       0   524.4     .08       0
     540      .1       0     650     .07       0     750     .06       0
  1183.5     .07       0  1283.5     .08       0  1443.5     .06       0
Bank Sta=425.4,524.4
XS Rating Curve= 0 ,0
Exp/Cntr(USF)=0,0
Exp/Cntr=0.3,0.1

Type RM Length L Ch R = 1 ,114126  ,291.5,287.9,285.5
XS GIS Cut Line= 3
2338042.98877407697030.1247844072339165.99013099 697473.52384415
2339223.56681371697738.694378962
#Sta/Elev= 30
       0 2393.03    77.3 2356.12    87.3 2347.89   104.5 2343.55   138.9 2322.19
   151.8 2309.94   173.3 2297.07   207.7 2283.68   224.9 2279.56   246.8 2268.38
   267.9 2252.96     298 2246.51   315.2 2230.25   336.7    2229   367.1  2212.3
   367.8 2212.25   505.8 2212.31   530.2 2220.09   551.7 2221.35   930.2 2227.66
   989.9 2230.22  1011.9 2235.45  1076.4  2233.1  1274.2 2239.31  1329.8 2247.32
  1350.3 2255.06  1373.7 2259.58  1391.2 2270.89  1411.7 2277.92  1478.7 2294.63
#Mann= 13 ,-1,0
       0      .1       0   367.1    .045       0   505.8     .06       0
     620      .1       0     640     .07       0     740     .05       0
     850     .07       0     950     .08       0    1060     .07       0
    1170     .06       0 1297.37      .1       0 1397.37     .05       0
 1477.37      .1       0
Bank Sta=367.1,505.8
XS Rating Curve= 0 ,0
Exp/Cntr(USF)=0,0
Exp/Cntr=0.3,0.1

Type RM Length L Ch R = 1 ,113838  ,339.5,319.4,304.3
BEGIN DESCRIPTION:
Structure XS 4
END DESCRIPTION:
XS GIS Cut Line= 4
2337959.63217988  697188.55013992338154.39625285697387.458129317
 2338813.2789678 697623.661366752338954.17212697697843.288938399
#Sta/Elev= 30
       0 2382.11    56.9 2354.89    80.8 2341.92   105.5 2326.82   119.6 2314.57
   133.8 2311.25   146.4 2301.74   196.8 2276.21   218.6 2268.37   229.9 2261.97
   252.6 2252.52   272.4 2242.39   288.8 2229.92   293.6 2228.51   322.8 2228.01
   337.4 2219.71   369.5 2211.09   518.2 2211.19   553.3 2221.06   700.3 2221.65
   815.7 2227.57   875.4 2228.62   904.9 2234.42   944.2 2232.46   990.2 2234.63
  1004.7 2240.07  1020.7 2242.67  1039.4 2249.57  1085.7 2259.58  1239.3 2288.39
#Mann= 9 ,-1,0
       0      .1       0   369.5    .045       0   518.2      .1       0
  578.38     .08       0  688.38     .06       0  768.38     .05       0
  788.38     .07       0 1008.33     .08       0 1018.33     .05       0
Bank Sta=369.5,518.2
XS Rating Curve= 0 ,0
Exp/Cntr(USF)=0,0
Exp/Cntr=0.3,0.1

Type RM Length L Ch R = 1 ,113519  ,306.7,321.3,331.6
BEGIN DESCRIPTION:
Structure XS 3
END DESCRIPTION:
XS GIS Cut Line= 4
2337677.84586154697486.9121240262337897.47343319697727.259277905
2338572.93181392697727.259277905 2338813.2789678698046.340844263
#Sta/Elev= 30
       0 2425.48      45 2408.86    68.1 2396.47    92.4 2379.11    99.5 2371.51
   110.8 2346.64   119.3    2336     144 2325.54     176  2320.7   215.6 2292.26
   243.9 2262.64   283.6 2254.09   299.9 2243.25   311.9 2231.16   323.7 2224.65
   360.3 2223.62   432.3 2213.64   460.3 2216.73   488.3 2216.12  528.142209.658
   532.3 2209.03   648.3  2209.7   676.3 2218.62   968.3 2222.28  1000.3 2224.84
  1026.4 2233.42  1078.6 2235.91  1104.7 2232.55  1141.8 2247.94  1400.5 2314.92
#Mann= 9 ,-1,0
       0      .1       0  375.58     .07       0  528.14    .045       0
   648.3     .07       0  765.58      .1       0  865.58     .05       0
  965.58     .08       0 1101.04      .1       0 1261.04     .05       0
Bank Sta=528.14,648.3
XS Rating Curve= 0 ,0
Exp/Cntr(USF)=0,0
Exp/Cntr=0.3,0.1

Type RM Length L Ch R = 1 ,113198  ,444.7,483.1,513
BEGIN DESCRIPTION:
Structure XS 2
END DESCRIPTION:
XS GIS Cut Line= 5
2337536.95270237697557.3587036112337578.39186683697963.462515339
2338274.56982979697996.6138469082338572.93181392697971.750348231
2338722.11280598698174.802254095
#Sta/Elev= 30
       0 2404.06      40 2387.74   172.7 2345.01   180.8 2338.87   196.8  2317.7
   212.9 2309.84     221 2293.24     229 2287.65   285.3 2290.15   373.8 2284.38
   385.9 2279.04   405.9 2256.16     438 2255.67     454 2250.46   498.1 2221.16
   530.1 2222.28   626.2 2213.13   698.4 2213.83   758.4 2205.94   762.4 2205.88
   842.5  2206.1   870.5 2217.38   882.5  2218.2  1231.2 2222.74  1267.3 2225.93
  1307.5 2241.46  1347.6  2242.5    1379 2238.73    1590 2309.03  1656.5 2313.25
#Mann= 13 ,-1,0
       0      .1       0     200     .08       0     300     .07       0
     400      .1       0  678.21    .025       0   758.4    .045       0
   842.5     .06       0  978.21      .1       0 1068.21     .03       0
 1265.18     .06       0 1365.18      .1       0 1504.58     .05       0
 1624.58      .1       0
Bank Sta=758.4,842.5
XS Rating Curve= 0 ,0
Exp/Cntr(USF)=0,0
Exp/Cntr=0.3,0.1

Type RM Length L Ch R = 1 ,112715  ,429.5,423.3,418.2
BEGIN DESCRIPTION:
Structure XS 1
END DESCRIPTION:
XS GIS Cut Line= 4
2337398.78872271697865.4031986932337469.93221392698088.503298462
2337872.60993451698680.3600605312337872.60993451698958.002462426
#Sta/Elev= 30
       0 2300.78    62.7 2295.19    99.6 2286.72   117.3  2276.6   129.9 2272.34
   138.3 2257.12   146.7 2248.49   171.9 2242.02   213.9 2240.32   223.8 2232.94
     235 2220.43   239.1 2218.86   288.2 2217.97   312.4 2211.81   374.5 2208.55
   394.6 2204.69   467.2 2204.72   476.9 2207.87   494.1 2219.39   539.8 2224.05
   573.1 2231.99   750.1 2237.94   833.7 2236.85   868.8 2239.94     887 2250.86
   936.5  2252.5   954.8 2261.07  1014.8 2274.44  1179.3  2355.9  1227.7 2382.67
#Mann= 9 ,-1,0
       0      .1       0     190    .025       0  304.17     .06       0
  374.17     .07       0   394.6    .045       0   467.2     .06       0
  544.17     .05       0  904.17     .06       0 1010.02      .1       0
Bank Sta=394.6,467.2
XS Rating Curve= 0 ,0
Exp/Cntr(USF)=0,0
Exp/Cntr=0.3,0.1

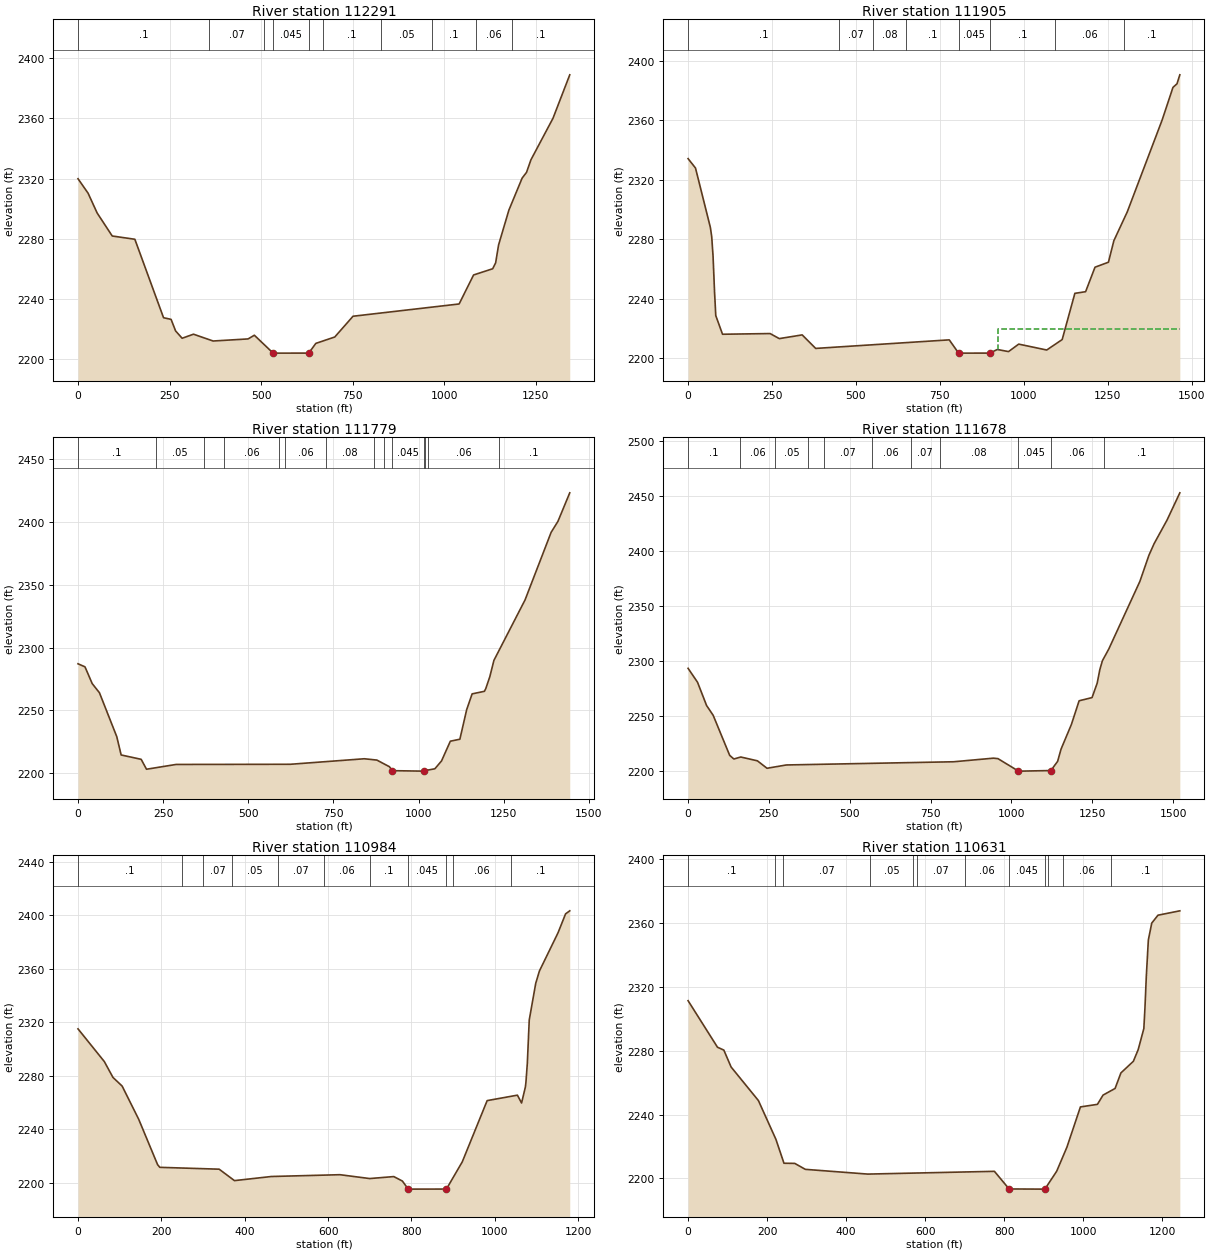
Type RM Length L Ch R = 1 ,112291  ,398.9,386.2,377.2
XS GIS Cut Line= 4
2336944.37265056697934.455100215 2337010.6753137698203.809669218
2337499.65745435698808.8214703632337524.52095303699094.751705151
#Sta/Elev= 30
       0 2319.89    27.5 2310.28    52.2 2297.14    93.4 2281.83   155.2 2279.65
   233.5 2227.53   254.1 2226.43   266.4 2218.75   284.3 2213.88   315.2 2216.58
   368.9 2212.05   464.3 2213.44   481.4 2215.89   532.6 2204.02   534.3    2204
   629.8 2204.01   649.2 2210.47   700.9 2214.72   750.7 2228.51  1040.3 2236.66
  1079.8 2255.94  1131.9 2260.06    1140 2263.99    1148 2275.86  1176.1 2298.99
  1212.3 2320.28  1224.3 2324.11  1236.3 2332.43  1296.6 2360.09  1342.3 2388.92
#Mann= 10 ,-1,0
       0      .1       0  357.39     .07       0  507.39      .1       0
   532.6    .045       0   629.8    .025       0  667.39      .1       0
  827.39     .05       0  967.39      .1       0  1085.3     .06       0
  1185.3      .1       0
Bank Sta=532.6,629.8
XS Rating Curve= 0 ,0
Exp/Cntr(USF)=0,0
Exp/Cntr=0.3,0.1

Type RM Length L Ch R = 1 ,111905  ,116.9,126.6,135.4
BEGIN DESCRIPTION:
Structure XS 4
END DESCRIPTION:
XS GIS Cut Line= 4
2336715.56073998697899.1679488662336789.06196751698598.790744248
2337118.45635755698851.9616390752337132.06769598699197.689635237
#Sta/Elev= 30
       0 2334.19    22.1 2327.86    66.4 2287.89    70.4 2281.67    74.4 2268.52
    78.8 2244.63    82.5 2228.53   102.6 2215.99   244.3 2216.45   271.7 2213.05
   339.9 2215.55   380.1 2206.45     778 2212.21   805.9 2203.28   898.5 2203.29
   921.3 2205.73   954.6 2204.31   984.9 2209.34  1068.4 2205.38  1114.4 2212.41
  1152.2 2243.52  1184.2 2244.63  1212.2 2261.11  1252.2 2264.47  1268.4 2278.97
  1308.3 2298.35  1412.4 2360.32  1444.4 2382.12  1456.4 2384.57  1464.9  2390.6
#Mann= 8 ,-1,0
       0      .1       0     450     .07       0     550     .08       0
     650      .1       0   805.9    .045       0   898.5      .1       0
 1093.47     .06       0 1298.92      .1       0
#XS Ineff= 2 , 0
                          921.88         2219.31
Permanent Ineff=
       F       F
Bank Sta=805.9,898.5
XS Rating Curve= 0 ,0
Exp/Cntr(USF)=0,0
Exp/Cntr=0.3,0.1

Type RM Length L Ch R = 1 ,111779  ,102.2,100.6,100.3
BEGIN DESCRIPTION:
Structure XS 3
END DESCRIPTION:
XS GIS Cut Line= 6
2336590.06779441698033.9090949242336438.81484413698456.588572436
 2336517.5492566698518.7473191292336693.66570557698630.633063177
2336900.86152788698870.9802170562336905.00544432699239.788780768
#Sta/Elev= 30
       0 2287.14    20.5 2284.69    41.7 2271.36      63 2264.06   113.9 2229.05
   126.7 2214.51   185.5 2211.04   201.2 2203.15   288.1 2206.96   623.4 2207.09
   840.9 2211.49   877.8 2210.43   914.6 2205.14   923.1    2202  1012.9 2201.64
  1014.7 2201.84  1047.9  2203.5  1067.6 2209.77  1093.4 2225.47  1121.4 2227.05
  1141.4  2250.6  1157.4 2263.17  1193.4  2265.2  1197.4  2267.3  1209.4  2276.9
  1221.4 2289.86  1312.8 2337.98  1389.4 2391.82  1409.4 2400.57  1444.1 2423.29
#Mann= 14 ,-1,0
       0      .1       0     230     .05       0     370     .08       0
     430     .06       0  589.24     .07       0  609.24     .06       0
  729.24     .08       0  867.89      .1       0  897.89     .07       0
   923.1    .045       0  1014.7     .07       0 1017.89      .1       0
 1027.89     .06       0 1235.22      .1       0
Bank Sta=923.1,1014.7
XS Rating Curve= 0 ,0
Exp/Cntr(USF)=0,0
Exp/Cntr=0.3,0.1

Type RM Length L Ch R = 1 ,111678  ,626.1,694.3,743.7
BEGIN DESCRIPTION:
Structure XS 2
END DESCRIPTION:
XS GIS Cut Line= 5
2336513.40534016697996.6138469082336331.07301652698481.452071114
2336612.85933487698688.6478934232336820.05515717698928.995047303
2336824.19907362699264.652279445
#Sta/Elev= 30
       0 2293.54    29.3 2280.82    57.3 2259.64    77.5 2250.85   128.7 2214.29
   141.6 2211.01     163 2212.81   214.3 2209.36   244.2 2202.57     304 2205.58
   821.4 2208.49   944.2 2211.76   958.2 2211.36 1019.582200.373    1026 2199.97
  1121.9 2200.48  1142.8 2208.84  1153.6 2220.12  1185.3 2242.33  1209.3 2263.99
  1249.3  2266.9  1265.3 2280.14  1273.3 2292.26  1281.3 2300.39  1301.3 2311.25
  1397.3  2372.7  1425.3  2396.5  1441.3 2407.03  1481.3  2428.5  1520.8 2453.26
#Mann= 11 ,-1,0
       0      .1       0     160     .06       0     270     .05       0
     370     .08       0     420     .07       0  567.99     .06       0
  687.99     .07       0  777.99     .08       0 1019.58    .045       0
  1121.9     .06       0 1285.08      .1       0
Bank Sta=1019.58,1121.9
XS Rating Curve= 0 ,0
Exp/Cntr(USF)=0,0
Exp/Cntr=0.3,0.1

Type RM Length L Ch R = 1 ,110984  ,346.7,352.5,356.9
BEGIN DESCRIPTION:
Structure XS 1
END DESCRIPTION:
XS GIS Cut Line= 2
2336513.40534016697926.1672673232335933.73530295698953.818428236
#Sta/Elev= 30
       0 2314.96    63.2 2290.49    83.9 2278.66   105.9  2272.2   145.8 2247.26
     191 2213.44   196.3 2211.44   338.7 2210.06   375.4 2201.51   464.1 2204.59
   628.5 2205.93     700 2203.05   757.7 2204.53   778.3 2201.19   792.2 2195.23
   793.4 2195.15     884  2195.2     922 2215.54   981.7 2261.32  1054.3  2265.4
  1064.3 2259.53  1073.5  2271.6  1074.8 2275.21  1078.1  2289.2  1082.7 2321.61
  1098.3 2349.05  1107.1  2358.2  1151.6 2386.67  1169.9 2400.95  1179.9  2403.2
#Mann= 11 ,-1,0
       0      .1       0     250     .06       0     300     .07       0
     370     .05       0     480     .07       0     590     .06       0
     700      .1       0   792.2    .045       0     884      .1       0
     900     .06       0    1040      .1       0
Bank Sta=792.2,884
XS Rating Curve= 0 ,0
Exp/Cntr(USF)=0,0
Exp/Cntr=0.3,0.1

Type RM Length L Ch R = 1 ,110631  ,456.7,462.5,467.8
XS GIS Cut Line= 2
2336306.20951785697772.8423588142335577.81669499698782.085028354
#Sta/Elev= 30
       0 2311.36    74.4 2282.22    90.5 2280.41   108.9 2269.82     178 2248.81
   222.3 2224.52   242.7 2209.54     270 2209.45   296.8 2205.72   454.6 2202.75
   775.3 2204.48   812.5 2193.44   895.6 2193.33   903.1 2193.36   932.9 2204.53
   958.7 2219.54     993 2244.82    1036 2246.43  1050.3 2252.23  1080.7 2256.39
  1095.5 2266.13    1127 2273.41  1139.2 2280.71  1153.5  2293.9  1156.3 2306.73
  1159.7 2326.34  1164.9 2349.37  1173.5 2359.96  1189.3 2364.91  1244.6 2367.65
#Mann= 12 ,-1,0
       0      .1       0     220     .06       0     240     .07       0
     460     .05       0     570     .06       0     580     .07       0
     700     .06       0   812.5    .045       0   903.1    .025       0
     910      .1       0     950     .06       0    1070      .1       0
Bank Sta=812.5,903.1
XS Rating Curve= 0 ,0
Exp/Cntr(USF)=0,0
Exp/Cntr=0.3,0.1

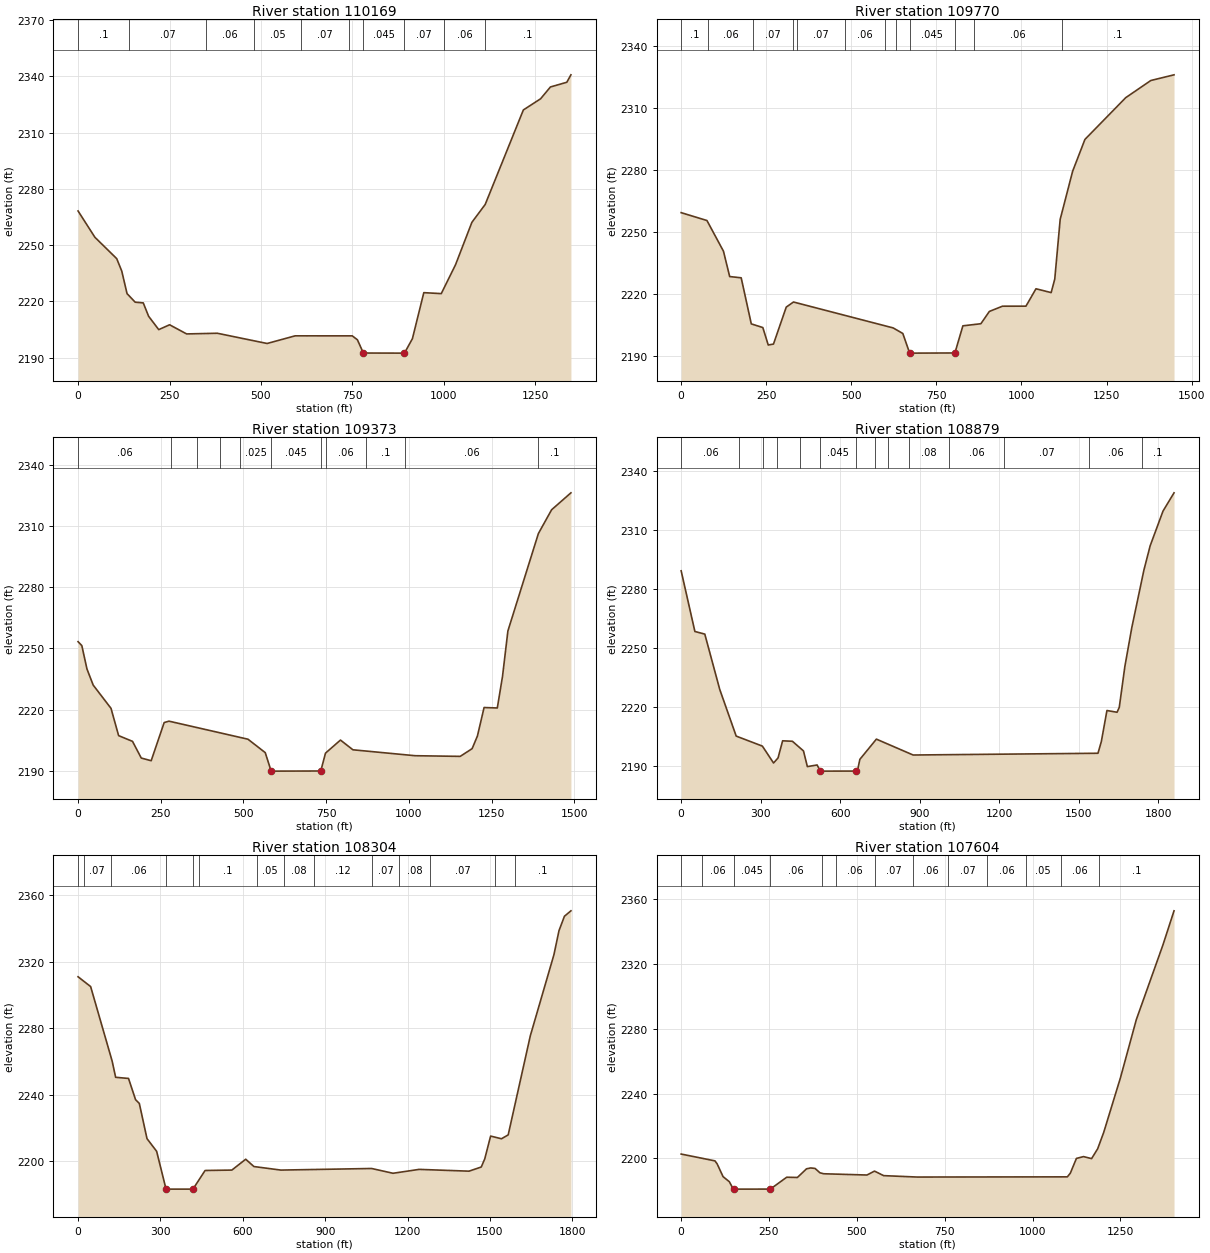
Type RM Length L Ch R = 1 ,110169  ,399,399.2,399.2
XS GIS Cut Line= 3
2335962.26445281697586.3661187352335299.23782142698352.990661281
2335448.41881348698651.352645408
#Sta/Elev= 30
       0 2268.27      46 2254.25   105.6 2242.86   119.4 2236.24   133.9 2224.19
   156.1 2219.62   178.2 2219.24   192.8 2212.12   220.5 2204.99   250.2 2207.57
   296.7 2202.69   380.6 2203.05   516.7 2197.59   593.3 2201.67   749.4 2201.66
   763.5 2199.57   779.8  2192.5   889.8 2192.45   892.2 2192.49   913.8 2200.13
     945  2224.7   992.7 2224.19  1031.7 2239.59  1076.4  2262.2  1112.8 2271.75
  1217.1 2322.15  1264.2  2328.1    1291  2334.4  1335.8 2336.91  1347.1 2340.88
#Mann= 10 ,-1,0
       0      .1       0     140     .07       0     350     .06       0
     480     .05       0     610     .07       0     740      .1       0
   779.8    .045       0   892.2     .07       0    1000     .06       0
 1113.57      .1       0
Bank Sta=779.8,892.2
XS Rating Curve= 0 ,0
Exp/Cntr(USF)=0,0
Exp/Cntr=0.3,0.1

Type RM Length L Ch R = 1 ,109770  ,395.4,396.8,397.1
XS GIS Cut Line= 2
2335597.59980555697399.8898786562334648.64293937698493.883820452
#Sta/Elev= 30
       0 2259.51    75.8  2255.7   124.3 2240.85   142.6 2228.56   176.4 2227.95
   206.1 2205.63     240 2203.86   255.9  2195.4   271.3 2195.86   308.8 2213.76
     330 2216.23   622.9 2203.68   651.3 2200.99   671.1 2191.63   679.5 2191.47
   804.4 2191.55   827.8 2204.69   880.7 2205.71   905.6 2211.66   944.2  2214.2
  1013.1 2214.22  1042.6 2222.64  1087.2 2220.79  1097.8 2227.36  1113.7 2256.27
  1150.3 2279.57  1186.4 2294.98  1306.3 2315.21    1380 2323.52  1448.2 2326.27
#Mann= 12 ,-1,0
       0      .1       0      80     .06       0     210     .07       0
     330     .06       0     340     .07       0     480     .06       0
     600     .08       0     630    .025       0   671.1    .045       0
   804.4     .07       0     860     .06       0    1120      .1       0
Bank Sta=671.1,804.4
XS Rating Curve= 0 ,0
Exp/Cntr(USF)=0,0
Exp/Cntr=0.3,0.1

Type RM Length L Ch R = 1 ,109373  ,488.7,493.7,496.6
XS GIS Cut Line= 3
 2335270.1174948697191.0893440082334662.63727948697867.601401981
2334639.62666526698447.468880244
#Sta/Elev= 30
       0 2253.23    11.4 2251.31    26.9 2239.86    45.8 2231.95    99.6 2220.56
   122.6  2207.2   164.6 2204.39     191 2196.22     221 2194.91   260.3 2213.62
   274.8 2214.29   513.5 2205.45   565.7 2198.88   583.4 2189.92   586.4 2189.81
   733.6 2189.88   747.8 2198.62   793.1 2205.03   830.7 2200.26  1018.9 2197.36
    1155 2197.04    1191 2200.82    1207 2207.02  1227.1 2220.97  1267.1 2220.75
  1282.8  2236.2  1299.1 2258.49  1391.2 2306.19  1431.2 2317.86  1489.6 2326.16
#Mann= 11 ,-1,0
       0     .06       0     280     .08       0     360     .07       0
     430     .06       0     490    .025       0   583.4    .045       0
   733.6      .1       0     750     .06       0     870      .1       0
  989.23     .06       0 1389.23      .1       0
Bank Sta=583.4,733.6
XS Rating Curve= 0 ,0
Exp/Cntr(USF)=0,0
Exp/Cntr=0.3,0.1

Type RM Length L Ch R = 1 ,108879  ,631.6,575.2,499.4
XS GIS Cut Line= 3
2334906.14431866696905.9276442512334286.34955958697529.806143167
2334603.05985846698456.588572436
#Sta/Elev= 30
       0 2289.26    51.8 2258.42    89.2 2257.08   145.5 2228.98   207.6 2205.24
   306.3 2200.16   348.5 2191.57   365.4 2194.14   382.7 2202.85   419.5 2202.62
   461.3 2197.72     476 2189.74   512.8 2190.57   524.9 2187.44   658.6 2187.47
   665.5 2187.99     674 2193.43   736.3  2203.7   874.9 2195.63    1572 2196.52
  1584.7 2202.49  1605.8 2218.25  1643.9 2217.36  1652.3 2219.84  1673.4 2240.62
  1699.5 2260.35  1745.3 2289.66  1768.8 2301.97  1817.2 2319.59  1858.8 2328.89
#Mann= 14 ,-1,0
       0     .06       0     220     .07       0     310      .1       0
     360     .07       0     450     .06       0   524.9    .045       0
   658.6      .1       0     730     .05       0     780      .1       0
     860     .08       0 1009.41     .06       0 1219.41     .07       0
 1539.41     .06       0 1739.41      .1       0
Bank Sta=524.9,658.6
XS Rating Curve= 0 ,0
Exp/Cntr(USF)=0,0
Exp/Cntr=0.3,0.1

Type RM Length L Ch R = 1 ,108304  ,718,699.9,676.5
XS GIS Cut Line= 2
2333869.58664748696852.8929077572334495.31803086698535.322984914
#Sta/Elev= 30
       0 2310.89    45.8 2304.98   124.1 2260.17   136.9 2250.38   183.8 2249.69
   209.4 2236.92   223.1 2234.66   251.1 2213.45   286.2 2205.85   320.4 2183.09
   418.5 2183.08   462.6  2194.3   560.1 2194.54   610.6 2201.07   640.5 2196.67
   738.6 2194.54  1069.2  2195.5    1147 2192.62  1242.2 2194.96  1423.8 2193.89
  1468.4 2196.39  1481.2 2201.32  1502.5 2215.01  1542.1 2213.39  1566.5 2215.72
  1647.2 2275.43    1733 2324.11  1751.6 2338.68  1771.4 2347.32    1795 2350.57
#Mann= 14 ,-1,0
       0     .08       0      20     .07       0     120     .06       0
   320.4    .045       0   418.5     .06       0     440      .1       0
     650     .05       0     750     .08       0     860     .12       0
    1070     .07       0    1170     .08       0    1280     .07       0
    1520     .06       0    1590      .1       0
Bank Sta=320.4,418.5
XS Rating Curve= 0 ,0
Exp/Cntr(USF)=0,0
Exp/Cntr=0.3,0.1

Type RM Length L Ch R = 1 ,107604  ,516.2,511.3,504.4
XS GIS Cut Line= 4
2333366.36080313697501.8033772922333393.03625617697566.483822582
2333597.10534427697773.4147208482333990.77740665698738.374890778
#Sta/Elev= 30
       0 2202.74    96.2 2198.53   102.4  2196.7   119.3 2188.79   137.1 2185.67
   148.5 2181.08150.2975 2181.08253.8788  2181.1   300.4 2188.43   330.8 2188.27
   356.9 2193.63   368.9 2194.16   381.2 2193.86   394.9 2191.18   405.7 2190.57
   528.8 2189.79   550.4 2192.21   576.3 2189.41   671.4 2188.54  1099.2 2188.66
  1107.7 2190.95    1125 2200.05  1145.2 2201.17  1168.2 2199.92  1185.5 2206.01
  1202.8 2216.21  1250.3 2249.84  1295.5 2285.77  1371.2 2331.86  1402.8 2352.96
#Mann= 13 ,-1,0
       0     .07       0      60     .06       0150.2975    .045       0
253.8788     .06       0  400.59      .1       0  440.59     .06       0
  550.59     .07       0  660.59     .06       0  760.59     .07       0
  870.59     .06       0  980.59     .05       0 1080.59     .06       0
 1190.59      .1       0
Bank Sta=150.2975,253.8788
XS Rating Curve= 0 ,0
Exp/Cntr(USF)=0,0
Exp/Cntr=0.3,0.1

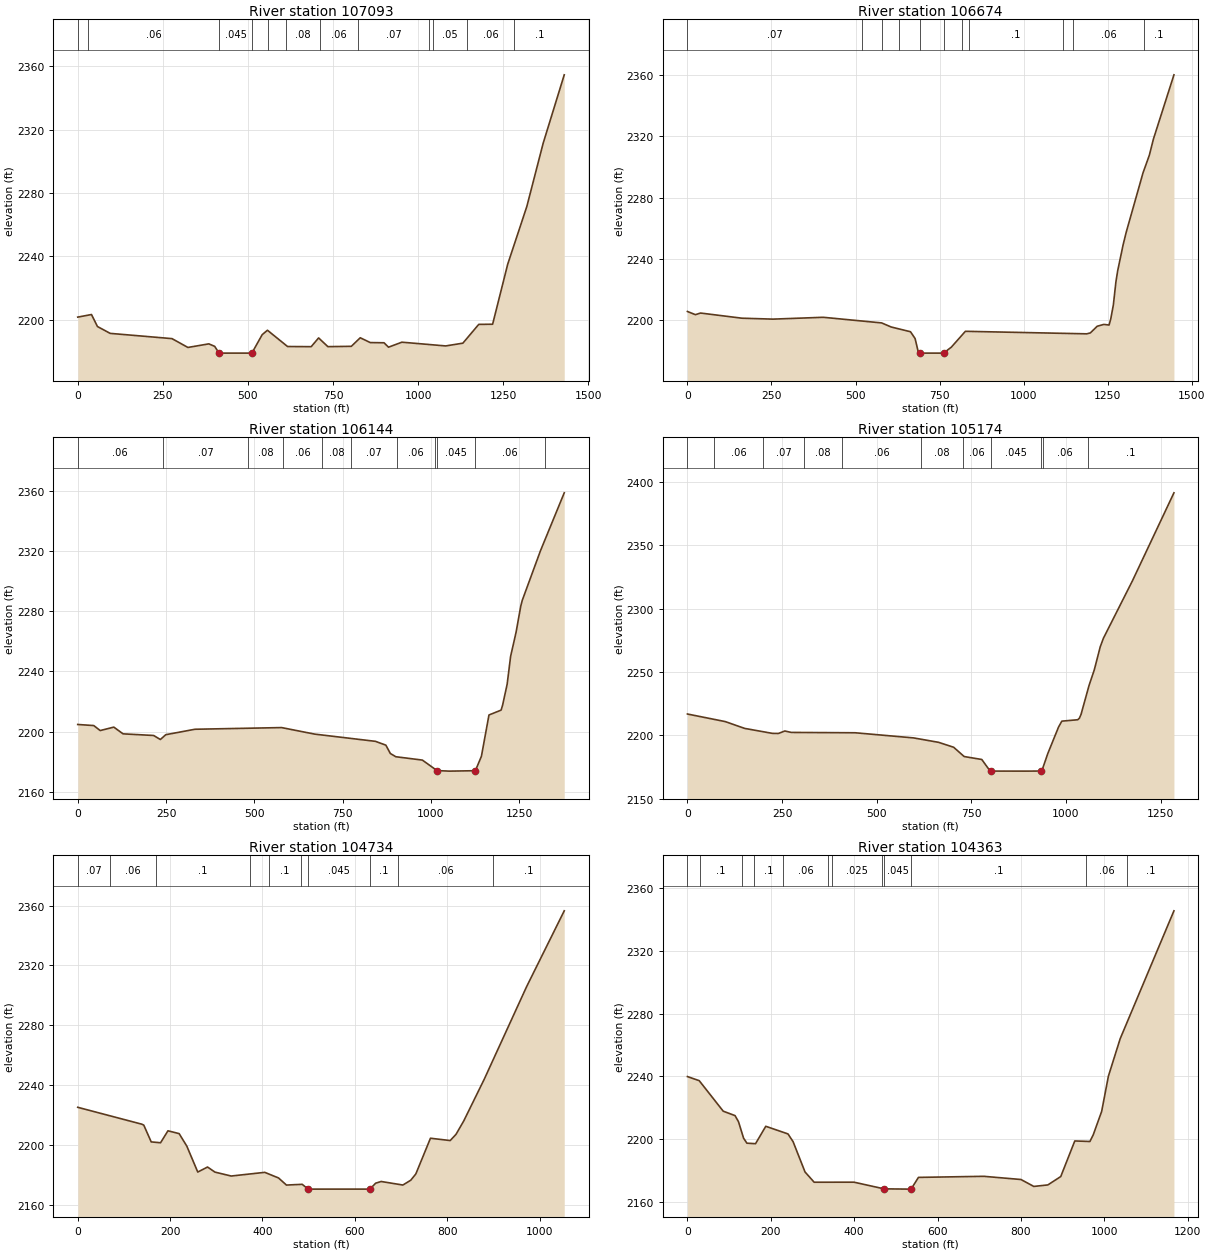
Type RM Length L Ch R = 1 ,107093  ,425.8,419,413.5
XS GIS Cut Line= 5
2332956.06072065697628.0603668792332991.68139651697710.323819821
2333111.90732776 698016.008808922333226.05968672698104.408028818
2333574.27621004698897.825725882
#Sta/Elev= 30
       0 2201.75    40.4 2203.38    57.9 2195.82    95.3 2191.49   276.8 2188.18
   323.6 2182.61     385 2184.88   402.2 2183.31   415.1 2179.03   511.5 2179.04
   541.7 2190.66   557.2 2193.47   616.3  2183.2   685.7  2183.1   707.5 2188.62
   734.7 2183.12   803.6 2183.32   829.8 2188.72   859.2 2185.69   899.7 2185.56
   912.8 2182.78   952.1 2185.93  1080.8 2183.57  1131.2 2185.31  1177.9 2197.17
  1218.6 2197.26  1262.9 2235.12  1319.1 2271.55  1367.1 2311.47    1429 2354.61
#Mann= 12 ,-1,0
       0     .07       0      30     .06       0   415.1    .045       0
   511.5     .06       0  558.12     .07       0   612.5     .08       0
   712.5     .06       0   822.5     .07       0  1032.5     .06       0
  1042.5     .05       0  1142.5     .06       0  1282.5      .1       0
Bank Sta=415.1,511.5
XS Rating Curve= 0 ,0
Exp/Cntr(USF)=0,0
Exp/Cntr=0.3,0.1

Type RM Length L Ch R = 1 ,106674  ,504.3,529.7,576.2
XS GIS Cut Line= 4
2332584.16793667697769.7156245962332848.45627525698348.189354906
2333021.58829238698452.0521901052333238.43908175699021.528343286
#Sta/Elev= 30
       0 2205.52    23.7 2203.44      39  2204.5   162.1 2201.13   254.5 2200.52
   404.1 2201.72   577.6 2198.05   606.3 2195.37   663.6 2192.28   677.3 2187.81
   686.1 2179.64   691.6 2178.31   761.9  2178.3   784.9 2182.17   826.9 2192.56
  1187.9 2190.91  1198.6  2191.5  1218.9 2195.86  1238.6 2197.07  1254.3 2196.66
  1259.2  2200.5  1267.1 2209.82  1274.7 2224.92  1279.9 2232.07  1296.4  2249.4
  1305.7 2257.61  1355.3 2296.11  1374.1 2307.64  1386.3 2318.23  1447.3 2360.19
#Mann= 11 ,-1,0
       0     .07       0     520     .08       0     580     .06       0
     630    .025       0   691.6    .045       0   761.9      .1       0
  815.99    .025       0  837.88      .1       0 1117.88     .05       0
 1147.88     .06       0 1357.88      .1       0
Bank Sta=691.6,761.9
XS Rating Curve= 0 ,0
Exp/Cntr(USF)=0,0
Exp/Cntr=0.3,0.1

Type RM Length L Ch R = 1 ,106144  ,940.2,969.9,1011.5
XS GIS Cut Line= 4
2332338.66952448697899.6717104352332391.09138406698019.398490996
2332502.66658228698288.8924183872332845.53227041699180.056864417
#Sta/Elev= 30
       0  2204.7    45.3 2203.99    63.6 2200.66   102.1 2202.95   128.3 2198.48
   214.9 2197.39   233.9 2194.71   249.2 2197.91   331.9 2201.53     577 2202.64
     671 2198.29   842.7  2193.5   872.2 2190.96   884.9 2185.42   900.4 2183.26
   975.6 2181.03    1017 2174.05  1052.1 2173.69  1125.6 2173.97  1142.7 2183.53
  1164.1 2211.02  1198.4 2214.25  1202.7 2217.55  1215.6 2231.54  1225.4 2250.03
  1240.9 2266.11  1254.1  2283.4  1258.4 2287.28  1309.9 2320.23  1377.2 2358.73
#Mann= 11 ,-1,0
       0     .06       0   240.7     .07       0  482.38     .08       0
  582.38     .06       0  692.38     .08       0  772.38     .07       0
  902.38     .06       0 1012.38     .07       0    1017    .045       0
  1125.6     .06       0 1322.38      .1       0
Bank Sta=1017,1125.6
XS Rating Curve= 0 ,0
Exp/Cntr(USF)=0,0
Exp/Cntr=0.3,0.1

Type RM Length L Ch R = 1 ,105174  ,438.4,440.4,442
XS GIS Cut Line= 3
2331851.31944204697997.0063127932332004.82424669698178.946170541
 2331665.0230981699169.342201182
#Sta/Elev= 30
       0 2216.73    99.7 2210.76   151.2 2205.36   224.6 2201.43   240.4 2201.37
   257.3 2203.32   274.2 2202.19   443.4 2201.91   597.5 2197.85   663.3 2194.37
   703.2 2190.48     731 2183.14   777.5 2180.82   798.6  2172.1802.8916 2171.66
   893.3 2171.62933.99162171.692   938.2 2173.63   951.9  2185.5   980.2 2206.36
   988.9 2211.09  1031.2 2212.21  1035.4 2213.47  1039.7 2216.43  1060.8 2239.22
  1074.7 2251.59  1090.4 2269.79  1098.9 2276.63  1175.5 2321.94  1285.1 2391.42
#Mann= 11 ,-1,0
       0     .07       0      70     .06       0     200     .07       0
  308.05     .08       0  408.05     .06       0  618.05     .08       0
  728.05     .06       0802.8916    .045       0933.9916    .025       0
  938.05     .06       0 1058.05      .1       0
Bank Sta=802.8916,933.9916
XS Rating Curve= 0 ,0
Exp/Cntr(USF)=0,0
Exp/Cntr=0.3,0.1

Type RM Length L Ch R = 1 ,104734  ,359,370.3,382.1
XS GIS Cut Line= 4
2331461.97119224698075.3482593862331495.12252381698336.414995496
2331296.21453439 698866.836300612331292.07061795699090.607788704
#Sta/Elev= 30
       0 2225.18   138.9 2213.88     143 2213.26   159.1 2202.05   179.3 2201.47
   195.4 2209.47   219.6 2207.58   236.2 2199.22   259.9 2181.89   281.1 2185.25
   297.1 2181.85   332.3 2179.23     405 2181.69   434.9 2177.92   451.9 2173.19
   486.1 2173.68   498.9 2170.47   632.7 2170.48   645.1 2174.44     657 2175.58
     704 2173.21   721.1 2176.41   732.1 2180.62   763.8  2204.5   806.5 2202.94
   819.1  2207.1   835.9 2216.09     880 2243.79     972 2305.85  1053.5 2356.55
#Mann= 10 ,-1,0
       0     .07       0      70     .06       0     170      .1       0
  373.16     .06       0  413.16      .1       0  483.16    .025       0
   498.9    .045       0   632.7      .1       0  693.16     .06       0
  899.65      .1       0
Bank Sta=498.9,632.7
XS Rating Curve= 0 ,0
Exp/Cntr(USF)=0,0
Exp/Cntr=0.3,0.1

Type RM Length L Ch R = 1 ,104363  ,619.9,591.3,574.9
XS GIS Cut Line= 4
2331118.02612721698021.477345585 2331180.1848739698311.551496819
2330807.23239374 698779.814055242330840.38372531699049.168624243
#Sta/Elev= 30
       0 2239.91    28.3  2237.3    85.8 2217.86   114.2 2215.02   122.4 2211.18
   134.7 2200.62   142.6 2197.45   163.3 2197.13   187.9 2208.22   241.1 2203.36
   253.3 2198.47     282 2179.11   303.9 2172.56   399.4 2172.59   471.5 2168.34
   534.1 2168.16   536.9 2168.38     554 2175.64   710.6 2176.33   799.9 2174.29
   830.6 2169.88   864.3 2170.84   895.3 2176.19   928.9 2198.87   965.2 2198.53
   973.2 2202.79   993.4 2217.75  1009.5 2240.14  1037.7 2263.99  1166.7 2345.58
#Mann= 12 ,-1,0
       0     .06       0      30      .1       0     130     .06       0
     160      .1       0     230     .06       0  336.66      .1       0
  346.66    .025       0  466.66      .1       0   471.5    .045       0
   536.9      .1       0  955.29     .06       0 1055.29      .1       0
Bank Sta=471.5,536.9
XS Rating Curve= 0 ,0
Exp/Cntr(USF)=0,0
Exp/Cntr=0.3,0.1

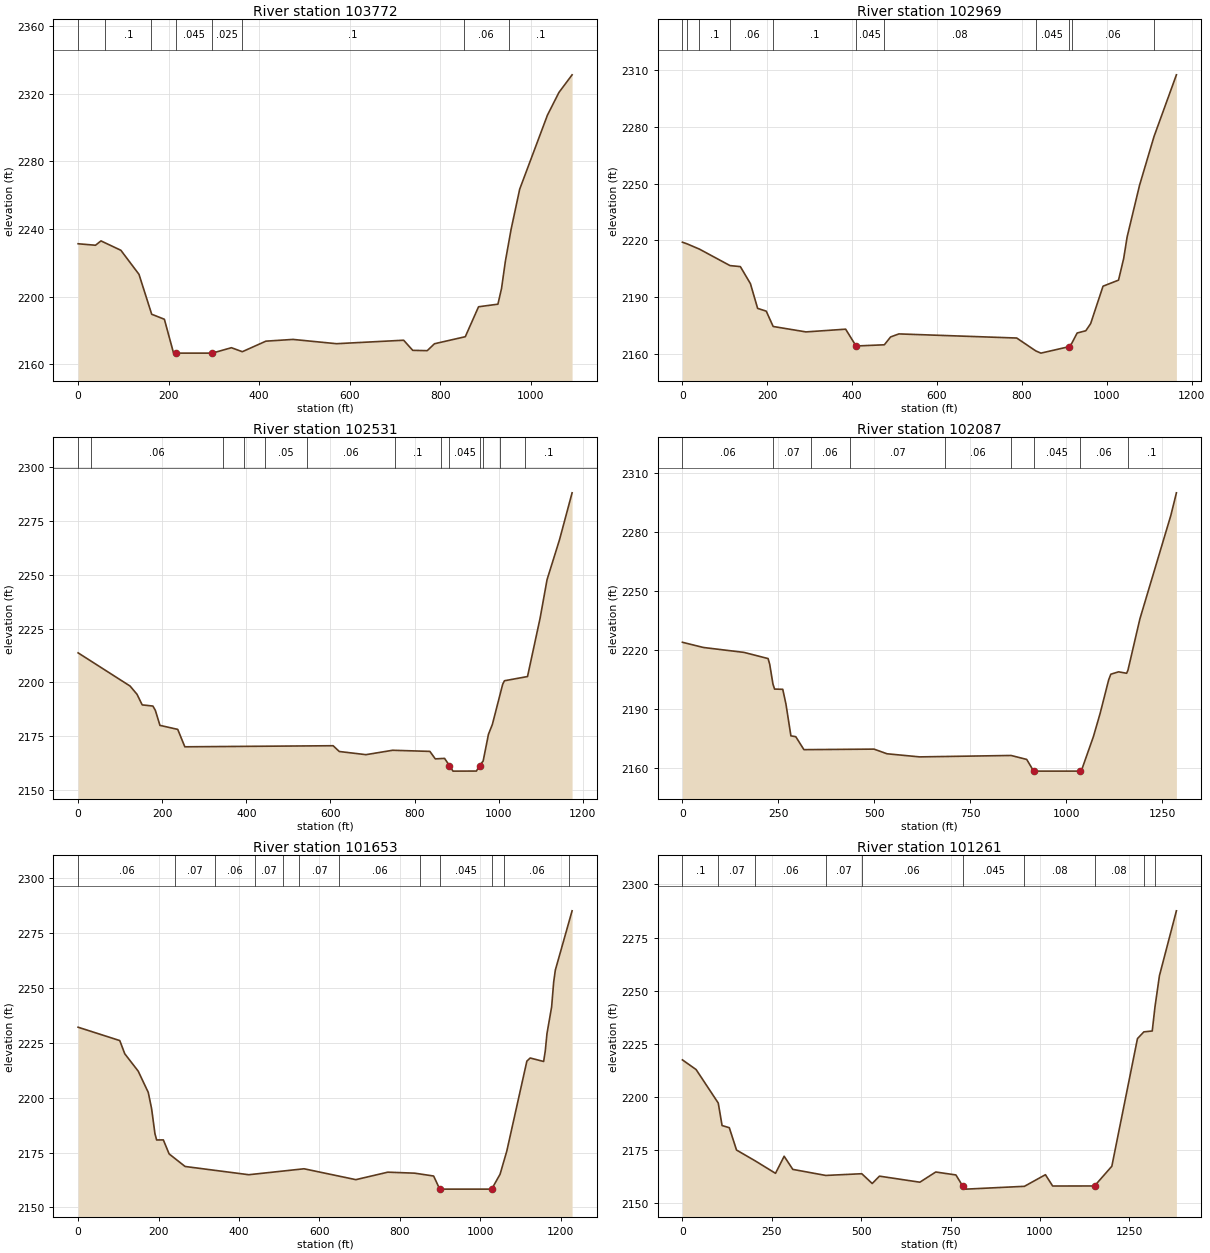
Type RM Length L Ch R = 1 ,103772  ,451.6,803.3,826.4
XS GIS Cut Line= 3
2330536.06590867697986.7691816242330531.14682424698108.499590956
2330480.03635593699076.844884429
#Sta/Elev= 30
       0 2231.24    38.4 2230.36    50.5 2232.93    94.5 2227.38   134.5 2213.18
   162.6 2189.59   190.6 2186.64   210.6 2166.94   214.6 2166.62216.7636 2166.62
296.3047 2166.62   338.8 2169.82   362.8 2167.46   414.9 2173.69   474.6 2174.72
   571.1 2172.19   719.3 2174.24   739.4 2168.26   771.4 2168.08   787.4 2172.16
   855.5 2176.32   884.8 2194.01   927.6 2195.54   935.6 2204.85     944 2220.79
   956.7 2239.73   975.7 2263.48    1037 2307.23  1062.4 2320.64  1091.5 2331.06
#Mann= 8 ,-1,0
       0     .06       0      60      .1       0  161.83    .025       0
216.7636    .045       0296.3047    .025       0  361.83      .1       0
  851.83     .06       0  951.83      .1       0
Bank Sta=216.7636,296.3047
XS Rating Curve= 0 ,0
Exp/Cntr(USF)=0,0
Exp/Cntr=0.3,0.1

Type RM Length L Ch R = 1 ,102969  ,586.4,437.3,439.3
BEGIN DESCRIPTION:
IFA needed to wet channel
END DESCRIPTION:
XS GIS Cut Line= 4
2330172.58846114697938.9522359582330097.05625116698347.099550021
2329993.75792716698892.6490914492329961.90189774699083.726336567
#Sta/Elev= 30
       0 2218.98    10.4 2218.16      40 2215.34   112.1 2206.62   136.5 2206.08
   160.2 2197.09   177.2    2184   197.5 2182.53   213.8 2174.43   291.1 2171.56
   384.6    2173   409.1 2164.11   475.8 2164.75   490.5 2168.89     510  2170.5
   787.7 2168.32   832.4 2161.55   844.7 2160.34   910.82163.738   917.4 2165.51
   930.1 2170.98   950.5 2172.17   961.9 2175.93   991.1 2195.73  1027.6 2198.93
  1039.8 2210.43  1047.9 2221.79  1077.2 2249.14  1111.2 2274.83    1164 2307.48
#Mann= 11 ,-1,0
       0      .1       0    10.4     .06       0      40      .1       0
   112.1     .06       0   213.8      .1       0   409.1    .045       0
   475.8     .08       0   832.4    .045       0   910.8      .1       0
   917.4     .06       0  1111.2      .1       0
Bank Sta=409.1,910.8
XS Rating Curve= 0 ,0
Exp/Cntr(USF)=0,0
Exp/Cntr=0.3,0.1

Type RM Length L Ch R = 1 ,102531  ,444.1,444.6,446
XS GIS Cut Line= 3
2329809.97513424697821.2817500842329847.28081046697970.504454988
2329520.13872664698937.582369459
#Sta/Elev= 30
       0 2213.74   123.6 2198.33   140.1  2194.5   152.4 2189.59   177.8 2189.05
   183.6 2187.09   194.6 2180.08   236.9 2178.22   253.8 2170.13   606.4 2170.63
   621.1 2167.95   684.5 2166.48   747.8 2168.52   836.5    2168   849.4 2164.53
   871.5 2164.75   882.9 2161.42   891.4 2158.84   947.2 2158.87   954.7 2161.42
   963.2 2163.53   975.8 2175.94   985.1 2180.51  1009.6 2199.13  1013.8 2200.79
  1068.7 2202.75  1098.7 2229.92  1115.2 2247.76  1144.7  2266.2  1174.7 2288.03
#Mann= 13 ,-1,0
       0      .1       0      30     .06       0  343.82     .07       0
  393.82     .06       0  443.82     .05       0  543.82     .06       0
  753.82      .1       0  863.82     .06       0   882.9    .045       0
   954.7     .06       0  963.82      .1       0 1003.82     .06       0
 1063.82      .1       0
Bank Sta=882.9,954.7
XS Rating Curve= 0 ,0
Exp/Cntr(USF)=0,0
Exp/Cntr=0.3,0.1

Type RM Length L Ch R = 1 ,102087  ,437.6,433.4,431.4
XS GIS Cut Line= 4
2329365.17668693697631.8837015532329431.17903717697847.108756702
2329152.82129918698633.3976248482328989.25025727698791.229331957
#Sta/Elev= 30
       0    2224    54.7 2221.36   160.4 2218.87   223.1 2215.74   227.3 2212.86
   235.8  2202.8     240 2200.27   261.3 2200.15   269.6 2192.69   282.5 2176.55
   295.2 2176.13   316.4 2169.55   498.9 2169.82   532.8 2167.46   617.7 2165.88
   855.9  2166.6   896.6  2164.6   914.7 2158.66  1034.5 2158.67  1040.8 2159.86
  1070.4  2176.2  1087.7 2187.84  1110.1 2204.95  1115.7 2207.81  1135.9 2209.01
  1156.8 2208.29  1160.2 2209.77  1191.4 2235.86  1272.1 2288.41  1286.5 2299.79
#Mann= 9 ,-1,0
       0     .06       0  235.12     .07       0  335.12     .06       0
  435.12     .07       0  685.12     .06       0  855.12    .025       0
   914.7    .045       0  1034.5     .06       0 1159.22      .1       0
Bank Sta=914.7,1034.5
XS Rating Curve= 0 ,0
Exp/Cntr(USF)=0,0
Exp/Cntr=0.3,0.1

Type RM Length L Ch R = 1 ,101653  ,523.7,392.3,369.6
XS GIS Cut Line= 2
 2329029.4256009697525.7060076792328685.06551266698705.139309898
#Sta/Elev= 30
       0 2232.16   103.6 2226.07   116.1 2220.03   149.5 2212.12   174.5 2202.42
   182.8 2195.02   191.1 2183.62   195.3 2180.74     212 2180.76   226.4 2174.37
   266.1 2168.64   424.5 2164.88     562 2167.59   690.8 2162.63   770.3 2166.04
     837 2165.59   884.3 2164.29   899.5 2158.31  1028.7 2158.31  1049.5 2165.09
  1066.2  2175.6  1116.2 2216.69  1124.5 2218.12  1157.9 2216.53    1162 2221.36
  1166.2 2229.21  1177.8 2241.45  1182.9 2252.77    1187 2258.21  1228.7 2285.25
#Mann= 12 ,-1,0
       0     .06       0     240     .07       0     340     .06       0
     440     .07       0     510     .08       0     550     .07       0
     650     .06       0     850    .025       0   899.5    .045       0
  1028.7      .1       0    1060     .06       0    1220      .1       0
Bank Sta=899.5,1028.7
XS Rating Curve= 0 ,0
Exp/Cntr(USF)=0,0
Exp/Cntr=0.3,0.1

Type RM Length L Ch R = 1 ,101261  ,1035.7,388.7,362.1
XS GIS Cut Line= 2
2328217.30972613697359.2652983642328403.83810726698728.096649114
#Sta/Elev= 30
       0 2217.44    38.3 2212.88   100.2 2197.12   110.9 2186.53   131.1 2185.51
   151.3    2175   203.8 2169.88   260.3 2164.04   284.5 2172.07   308.7 2165.89
   400.8 2163.04   501.6 2163.85   530.8 2159.24     551 2162.71     664 2159.86
   708.4 2164.66   764.9 2163.27   784.1 2157.96   793.2  2156.6   956.4 2157.92
  1015.2 2163.39  1035.4 2158.06  1152.5 2158.09  1200.9 2167.37  1272.6 2227.45
  1290.4 2230.62  1313.9 2231.04  1321.6 2242.42  1334.1 2257.12  1381.5  2287.6
#Mann= 10 ,-1,0
       0      .1       0   100.2     .07       0   203.8     .06       0
   400.8     .07       0   501.6     .06       0   784.1    .045       0
   956.4     .08       0  1152.5     .08       0  1290.4     .06       0
  1321.6      .1       0
Bank Sta=784.1,1152.5
XS Rating Curve= 0 ,0
Exp/Cntr(USF)=0,0
Exp/Cntr=0.3,0.1