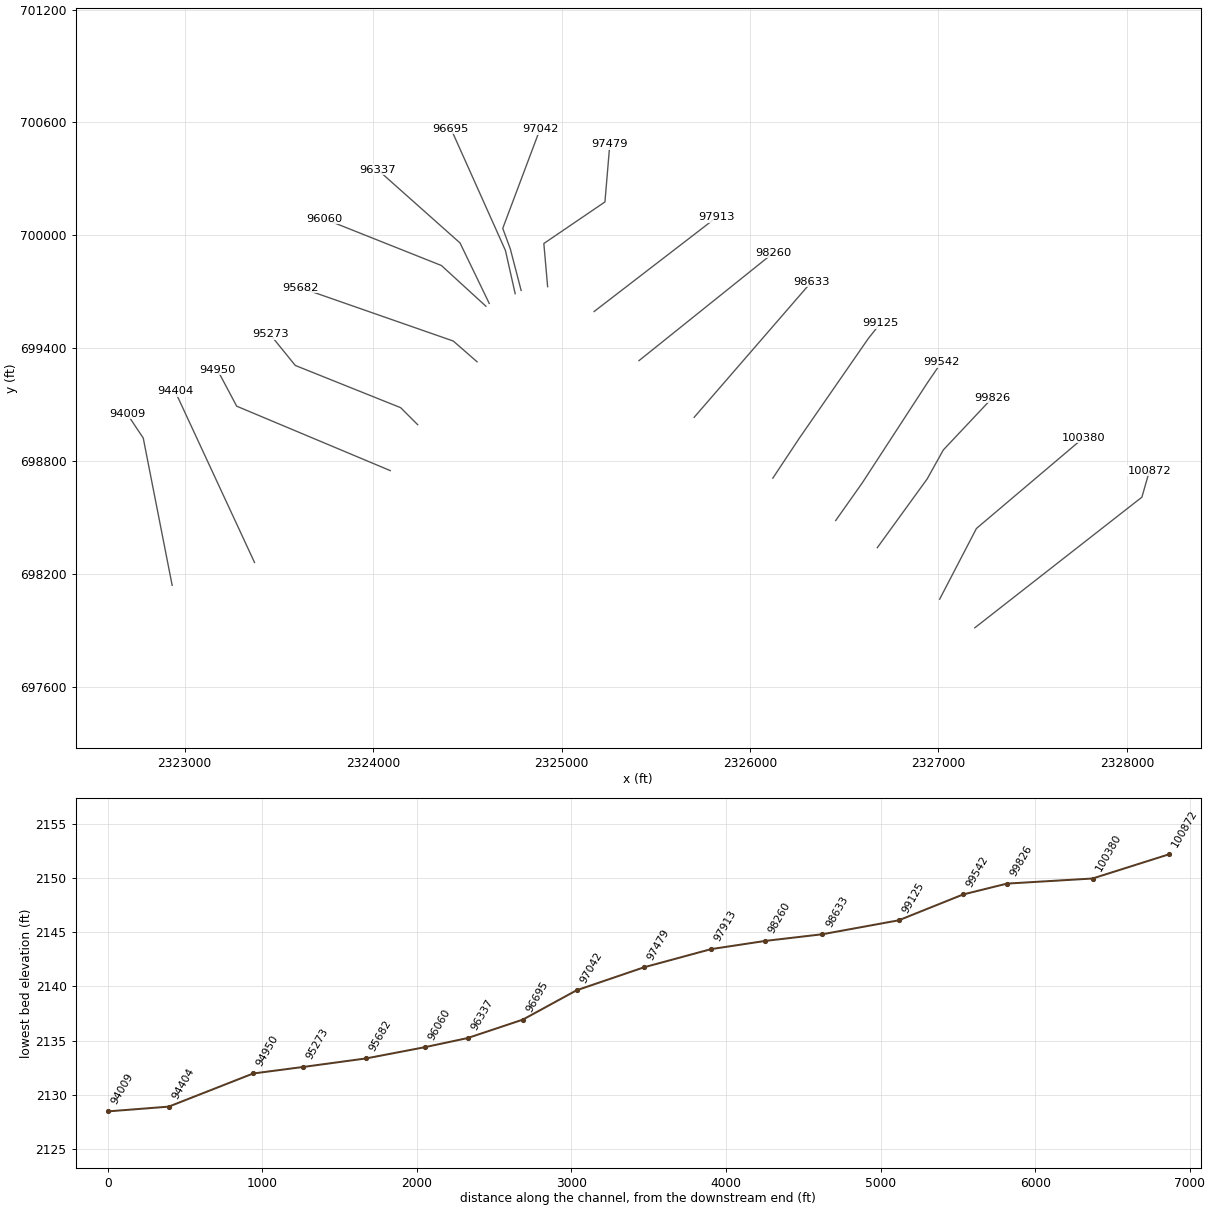
HEC-RAS study SHAVERSFK.prj: SHAVERSFK

--- SHAVERSFK.g01 (geometry) --- (continued)

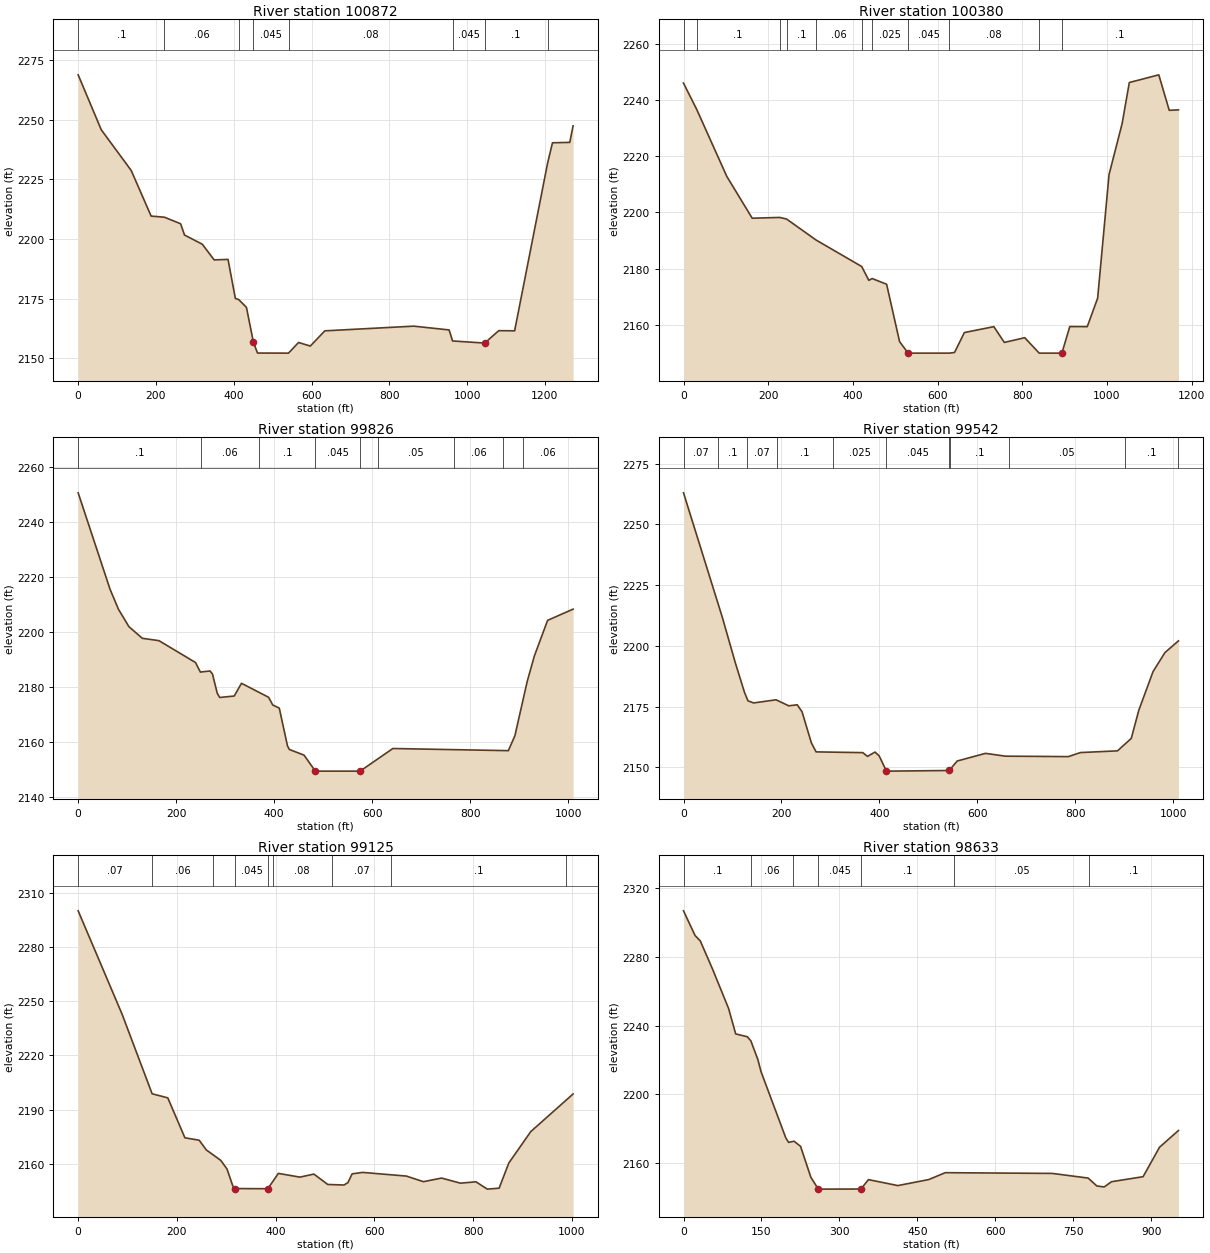
Type RM Length L Ch R = 1 ,100872  ,414.7,492.8,493.8
XS GIS Cut Line= 3
2327192.83846362697913.1111069482328079.56569084 698607.57061823
2328119.74103446698748.184320927
#Sta/Elev= 30
       0 2268.83    59.4  2245.8   136.3 2228.76   187.6 2209.61   221.8 2209.14
   263.4  2206.4   273.5 2201.67   319.2 2197.81   349.7 2191.24   385.3 2191.45
   404.2 2175.09   412.7 2174.62   432.7 2171.35  450.692156.617   461.2 2152.19
   537.7 2152.16   540.9 2152.17   566.6 2156.62   596.9 2155.13   634.2  2161.5
   862.9 2163.47   953.8 2161.88   962.6 2157.26  1045.3 2156.38  1081.4 2161.58
  1122.2 2161.51    1207 2231.84  1219.5 2240.34    1264 2240.51  1272.5 2247.45
#Mann= 8 ,-1,0
       0      .1       0   221.8     .06       0   412.7    .025       0
  450.69    .045       0   540.9     .08       0   962.6    .045       0
  1045.3      .1       0    1207     .06       0
Bank Sta=450.69,1045.3
XS Rating Curve= 0 ,0
Exp/Cntr(USF)=0,0
Exp/Cntr=0.3,0.1

Type RM Length L Ch R = 1 ,100380  ,396.2,553.3,564.5
XS GIS Cut Line= 3
2327006.31008249698065.2034792532327201.44746583698441.129908914
2327769.64161142698923.234032449
#Sta/Elev= 30
       0 2245.95    31.5 2236.49   102.2 2212.79   162.2 2197.91   226.8 2198.19
   243.3 2197.63   312.9 2190.17   420.8 2180.73   437.6 2175.82   445.4 2176.47
   479.6 2174.43   510.2 2154.02   530.5 2149.94   627.7 2149.94     640 2150.17
   663.2 2157.26   732.8 2159.35   757.5 2153.75   805.8 2155.42   839.9 2149.94
   893.5 2149.94   912.1 2159.38   953.4 2159.36   977.9 2169.48  1004.8 2213.41
  1035.7 2231.55  1052.7 2246.16  1122.3  2248.9    1147 2236.27  1168.7 2236.44
#Mann= 11 ,-1,0
       0     .07       0    31.5      .1       0   226.8     .06       0
   243.3      .1       0   312.9     .06       0   420.8      .1       0
   445.4    .025       0   530.5    .045       0   627.7     .08       0
   839.9    .045       0   893.5      .1       0
Bank Sta=530.5,893.5
XS Rating Curve= 0 ,0
Exp/Cntr(USF)=0,0
Exp/Cntr=0.3,0.1

Type RM Length L Ch R = 1 ,99826   ,284,284.3,272.3
XS GIS Cut Line= 4
 2326675.4865607698339.1818904992326940.11127913698704.714364658
 2327025.9064577698858.8055815092327287.79372188699137.476494379
#Sta/Elev= 30
       0 2250.62    64.9 2215.66    82.1 2208.35   103.5    2202   130.9 2197.75
   164.9 2196.89   239.5 2188.94   249.4 2185.47   269.1 2185.88   274.1 2184.78
   283.9 2177.74   288.9 2176.24   318.5 2176.77   333.3  2181.4   388.6 2176.31
   397.2 2173.49   410.4 2172.38   427.1 2158.69   430.9 2157.35     461 2155.28
483.86612149.507   486.9 2149.47   575.4 2149.47   642.2 2157.69   877.9 2156.91
   891.3 2162.36   916.3 2182.02   930.9 2191.28     958 2204.27    1010 2208.35
#Mann= 9 ,-1,0
       0      .1       0     250     .06       0     370      .1       0
483.8661    .045       0   575.4      .1       0  611.27     .05       0
  767.63     .06       0  867.63      .1       0  907.63     .06       0
Bank Sta=483.8661,575.4
XS Rating Curve= 0 ,0
Exp/Cntr(USF)=0,0
Exp/Cntr=0.3,0.1

Type RM Length L Ch R = 1 ,99542   ,417.3,416.5,433.9
XS GIS Cut Line= 4
2326454.57911163698483.3631493842326595.51328829698683.399626521
2326942.21597779699216.9584701892327015.17531869699323.976405066
#Sta/Elev= 30
       0 2262.99    79.2 2211.79   105.8 2193.03   124.5 2180.89   131.6  2177.4
   143.1 2176.53     189 2177.82   214.9 2175.34   232.2 2175.77     242 2172.89
   261.1 2160.07   270.7 2156.39   366.1 2156.08   375.6 2154.53     391 2156.31
   399.5 2154.74   413.8 2148.69   422.8 2148.47   542.6 2148.73   558.7 2152.63
   616.6 2155.78     657 2154.63   785.9 2154.44   810.3 2156.11   886.1 2156.81
   914.2 2161.94   929.7 2173.58   958.7 2189.43   982.9 2197.24  1010.5 2202.07
#Mann= 11 ,-1,0
       0     .07       0      70      .1       0     130     .07       0
     190      .1       0   304.7    .025       0   413.8    .045       0
   542.6    .025       0   544.7      .1       0   664.7     .05       0
  901.01      .1       0 1010.53     .06       0
Bank Sta=413.8,542.6
XS Rating Curve= 0 ,0
Exp/Cntr(USF)=0,0
Exp/Cntr=0.3,0.1

Type RM Length L Ch R = 1 ,99125   ,495.7,492.7,486.4
XS GIS Cut Line= 4
2326120.94286333698708.7638069722326260.97985809698920.307424161
2326627.71327854699451.1674230852326692.09208766699532.301410458
#Sta/Elev= 30
       0 2299.89    89.2 2242.62   149.8 2198.79   181.6 2196.52   216.2 2174.46
   245.1 2173.13   259.6 2167.76   288.8    2162   301.5 2157.21   313.1 2147.94
318.32642146.405 384.1482146.309   405.5 2154.78   449.2 2152.72   477.5  2154.4
   505.6 2148.66   538.4 2148.37   546.5 2149.68   554.9 2154.53     576 2155.33
   664.9  2153.3   699.4  2150.2   736.1  2152.2   774.2 2149.39   805.8 2150.13
   828.8 2146.09   852.7 2146.62   872.2 2160.47   916.8 2177.89  1002.5 2198.68
#Mann= 9 ,-1,0
       0     .07       0     150     .06       0  273.69    .025       0
318.3264    .045       0 384.148      .1       0  393.69     .08       0
  513.69     .07       0  633.69      .1       0  988.91     .07       0
Bank Sta=318.3264,384.148
XS Rating Curve= 0 ,0
Exp/Cntr(USF)=0,0
Exp/Cntr=0.3,0.1

Type RM Length L Ch R = 1 ,98633   ,379.5,372.2,362.9
XS GIS Cut Line= 2
2325703.48108199699032.2813937252326326.19890822699752.567911625
#Sta/Elev= 30
       0 2306.76    22.3 2292.36    32.3 2289.24    56.1 2272.67    86.7 2249.95
   100.4 2235.13   122.8 2233.48   129.5 2231.11   142.9 2220.35   149.2 2213.12
   196.8 2174.61   202.1 2172.02   212.7 2172.69   225.2 2169.69     245 2151.72
   259.2 2144.85   260.3 2144.81   341.4 2144.87   355.8 2150.35   412.3 2146.87
   471.9 2150.38   503.5 2154.38   709.7 2153.95   778.5 2151.24   795.2 2146.64
   809.4 2146.08   823.5 2149.13   884.2 2152.05   915.9 2169.23   952.2 2178.91
#Mann= 7 ,-1,0
       0      .1       0     130     .06       0     210      .1       0
   259.2    .045       0   341.4      .1       0     520     .05       0
     780      .1       0
Bank Sta=259.2,341.4
XS Rating Curve= 0 ,0
Exp/Cntr(USF)=0,0
Exp/Cntr=0.3,0.1

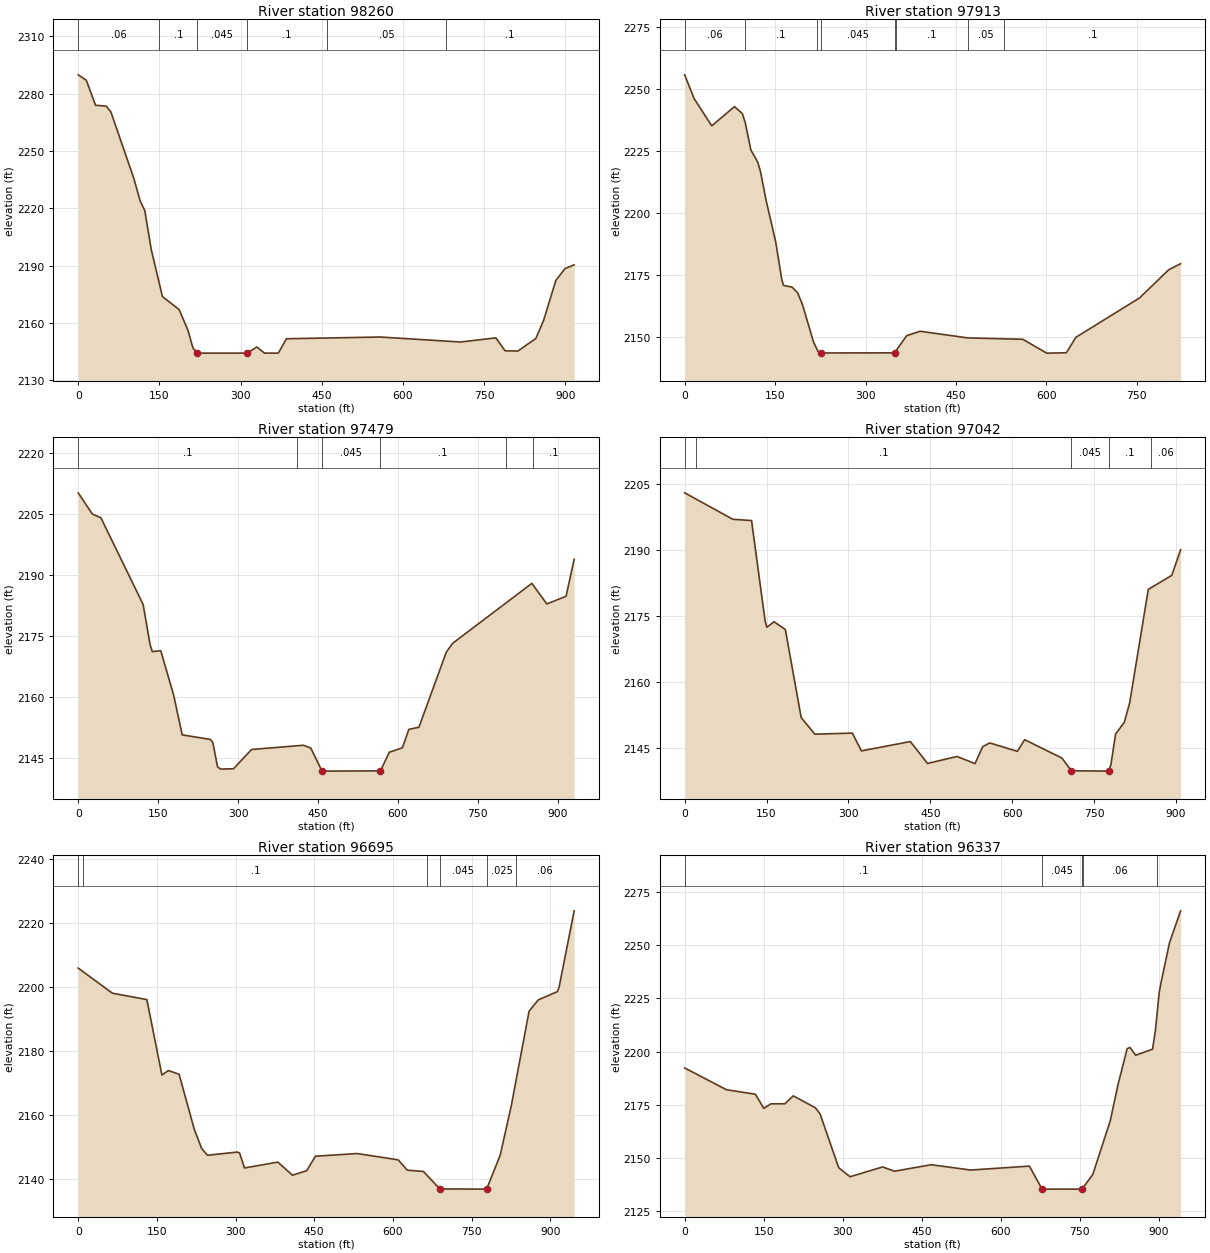
Type RM Length L Ch R = 1 ,98260   ,348.9,347.9,346.6
XS GIS Cut Line= 2
2325410.77500698699333.5964709342326125.32219008699907.529951332
#Sta/Elev= 30
       0 2289.77    14.9 2286.96      32 2273.85    51.9 2273.39    60.4 2270.37
   103.1 2235.32   114.5 2223.77     123 2218.83   135.2  2198.1   155.7 2173.77
   186.5 2166.96   202.7 2156.23   212.1 2146.86   219.8 2144.23   222.4 2144.19
   312.3 2144.19   330.1 2147.39   344.3  2144.2   369.8 2144.19   384.8 2151.71
   558.4 2152.62   706.3 2150.01   771.8 2152.17   788.8 2145.43   812.4 2145.25
   845.7 2151.85     860 2161.29   882.7 2182.25   899.6 2188.39   916.5 2190.39
#Mann= 6 ,-1,0
       0     .06       0     150      .1       0   219.8    .045       0
   312.3      .1       0     460     .05       0     680      .1       0
Bank Sta=219.8,312.3
XS Rating Curve= 0 ,0
Exp/Cntr(USF)=0,0
Exp/Cntr=0.3,0.1

Type RM Length L Ch R = 1 ,97913   ,436.2,433.4,429.6
XS GIS Cut Line= 2
2325172.59261262699594.7362045152325824.00711287700096.927999864
#Sta/Elev= 30
       0 2255.76    15.7 2246.16    44.9 2235.17    82.6 2242.92    95.6 2240.13
   100.5  2236.4   109.8 2225.41   121.2 2220.48   125.7 2216.75     135 2205.16
     151 2188.27   161.2 2172.89     164 2170.77   178.3 2170.06   187.4 2167.74
   195.4    2163   213.6 2147.99     221 2144.15   226.8  2143.5     348 2143.56
   368.2 2150.49   390.5 2152.27   469.2 2149.59   560.9 2149.02   600.4 2143.44
   632.9 2143.58   648.8 2149.81   754.4 2165.72   802.5 2177.03   822.5 2179.54
#Mann= 8 ,-1,0
       0     .06       0     100      .1       0     220    .025       0
   226.8    .045       0     348    .025       0     350      .1       0
     470     .05       0     530      .1       0
Bank Sta=226.8,348
XS Rating Curve= 0 ,0
Exp/Cntr(USF)=0,0
Exp/Cntr=0.3,0.1

Type RM Length L Ch R = 1 ,97479   ,408.1,436.9,458.7
XS GIS Cut Line= 4
2324925.80121605699726.7409050072324905.71354423699956.314297166
2325229.98596066700177.2786871192325255.81296728700484.333099133
#Sta/Elev= 30
       0 2210.31    26.5 2205.09    42.6 2204.16   121.9 2182.81     135 2172.89
     139 2171.22     155 2171.41   179.1 2160.53   195.2  2150.7     248 2149.58
   252.8 2148.77   261.6 2142.82   267.4 2142.28   291.5 2142.35   325.4  2147.1
   422.8 2148.14   436.7 2147.44   457.4 2141.85   460.9 2141.77   567.4 2141.84
   584.1 2146.43   608.5  2147.5   620.7 2152.05   639.6 2152.58     691 2171.07
     703 2173.26   851.6 2188.01   879.7 2182.94   915.8 2184.83     931 2193.93
#Mann= 6 ,-1,0
       0      .1       0  410.45    .025       0   457.4    .045       0
   567.4      .1       0  802.85     .06       0  852.85      .1       0
Bank Sta=457.4,567.4
XS Rating Curve= 0 ,0
Exp/Cntr(USF)=0,0
Exp/Cntr=0.3,0.1

Type RM Length L Ch R = 1 ,97042   ,309.4,347.7,369.2
XS GIS Cut Line= 4
2324785.18751335699706.6532331932324727.79416531699927.617623146
2324687.61882168700036.6649844222324885.62587242700564.683786388
#Sta/Elev= 30
       0 2203.08    88.2 2197.05   122.5 2196.76   147.3 2173.91   150.5 2172.44
   163.8 2173.69   184.4 2171.93   213.4 2151.85   238.5 2148.07   307.1 2148.32
   323.7 2144.26   413.4 2146.39   444.8  2141.4   498.9 2142.99   531.8 2141.36
   545.8 2145.21   558.7 2146.08   609.4 2144.16   622.7 2146.82   691.1 2142.62
   708.2 2139.74   776.5 2139.65  776.762139.726   780.8 2141.16   789.3 2148.11
   805.2 2150.76     815 2155.16   849.2 2181.08   892.2 2184.27   908.4 2190.11
#Mann= 5 ,-1,0
       0     .06       0      20      .1       0   708.2    .045       0
  776.76      .1       0  854.51     .06       0
Bank Sta=708.2,776.76
XS Rating Curve= 0 ,0
Exp/Cntr(USF)=0,0
Exp/Cntr=0.3,0.1

Type RM Length L Ch R = 1 ,96695   ,340.3,357.6,373.7
XS GIS Cut Line= 3
2324753.62117193699689.4352287812324701.96715869 699919.00862094
2324412.13075109 700567.55345379
#Sta/Elev= 30
       0 2206.03    65.3 2198.18   130.9 2196.19   159.6 2172.61   171.9 2174.01
   192.4 2172.85   221.1 2155.78   235.3 2149.66   246.5 2147.54   303.4 2148.53
   307.8 2148.23     317 2143.56   380.6  2145.4   408.6 2141.29   435.8 2142.73
   452.4 2147.24     532 2148.07   610.1  2146.1   627.6 2142.88   658.3 2142.47
   689.5 2137.01   777.3 2136.95   778.9 2136.99   804.6 2147.51   825.8    2163
   859.8 2192.56   877.2 2196.09   913.6 2198.67   916.8 2199.92   945.7 2223.93
#Mann= 6 ,-1,0
       0     .06       0      10      .1       0  665.31    .025       0
   689.5    .045       0   778.9    .025       0  835.31     .06       0
Bank Sta=689.5,778.9
XS Rating Curve= 0 ,0
Exp/Cntr(USF)=0,0
Exp/Cntr=0.3,0.1

Type RM Length L Ch R = 1 ,96337   ,262.3,277.1,291.6
XS GIS Cut Line= 3
2324615.87713663699637.7812155452324460.91509692699959.183964568
2324024.40679989700348.183323505
#Sta/Elev= 30
       0 2192.29    79.3 2182.04   134.2 2179.93   150.3 2173.24   163.6 2175.39
   190.3 2175.43   206.1 2179.16     248 2173.56   256.9 2170.75   292.4 2145.35
   313.9 2141.08   375.7 2145.69   398.4 2143.69     468 2146.74   542.9 2144.23
   654.4 2146.09   678.5 2135.25   754.3 2135.25   774.7 2142.09   807.9 2167.38
   822.7 2184.48     840 2201.36   845.4 2201.94   856.1 2198.25   888.2 2201.12
   893.6 2209.84   900.9 2227.85   904.3 2232.43   920.4 2251.25   941.5 2266.25
#Mann= 5 ,-1,0
       0      .1       0   678.5    .045       0   754.3      .1       0
  756.81     .06       0  896.81      .1       0
Bank Sta=678.5,754.3
XS Rating Curve= 0 ,0
Exp/Cntr(USF)=0,0
Exp/Cntr=0.3,0.1

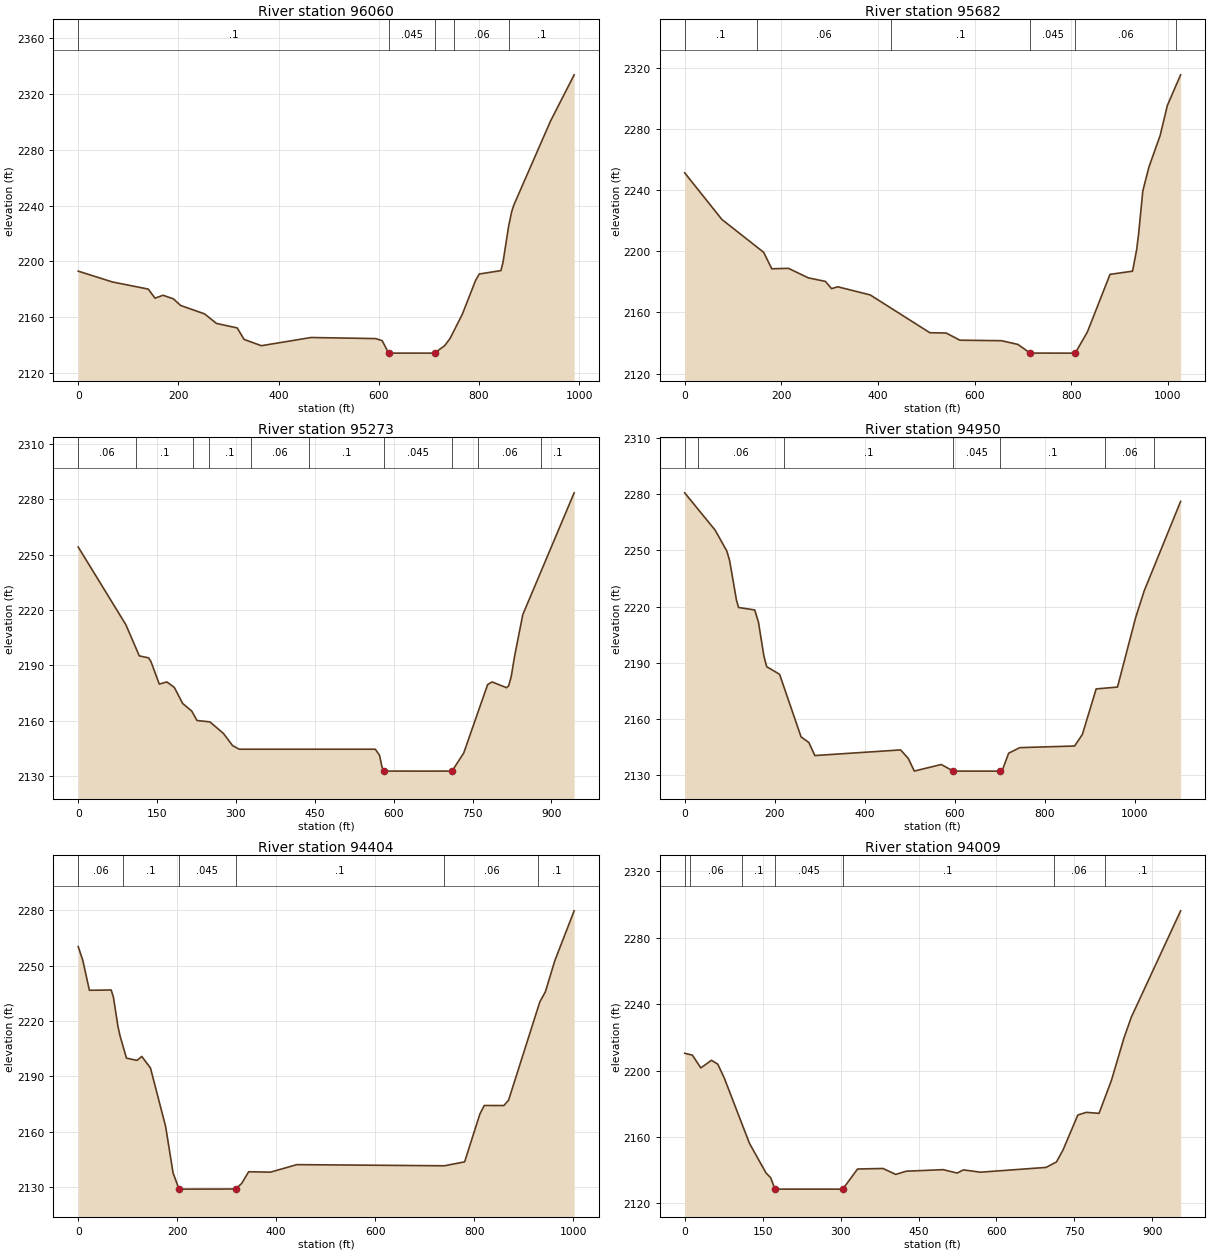
Type RM Length L Ch R = 1 ,96060   ,375.6,377.9,379.8
XS GIS Cut Line= 3
2324598.37727728699622.7250768242324362.19065983699839.229476151
2323740.23256722700087.225424472
#Sta/Elev= 30
       0 2193.09    68.1 2185.36   139.8 2180.24   153.3 2173.75   169.4 2175.83
   190.1 2173.26   204.3 2168.54   252.3 2162.49   275.9 2155.68   317.4 2152.45
   331.2  2144.2   365.6 2139.72   464.7 2145.59   593.9 2144.81   606.8 2143.31
   619.7 2134.44   641.2 2134.41   711.4 2134.43   731.7 2139.81   742.2 2144.84
   766.8 2162.27   793.2 2186.42   800.6 2191.05   843.8 2193.47   847.9 2199.22
   859.1 2225.02   865.2 2235.52   869.5 2240.32   942.7 2300.39     990  2333.6
#Mann= 5 ,-1,0
       0      .1       0   619.7    .045       0   711.4      .1       0
   750.4     .06       0   860.4      .1       0
Bank Sta=619.7,711.4
XS Rating Curve= 0 ,0
Exp/Cntr(USF)=0,0
Exp/Cntr=0.3,0.1

Type RM Length L Ch R = 1 ,95682   ,409.6,409.3,410.2
XS GIS Cut Line= 3
2324551.13995379699327.4918050142324425.17375782 699437.71222649
2323614.26637124699721.136167427
#Sta/Elev= 30
       0 2251.22      77 2220.74   163.4 2199.28   180.3 2188.51   214.8 2188.79
   255.7 2182.59   291.3 2180.24     304 2175.51   316.7 2176.74     384 2171.41
   507.4 2146.72   541.2 2146.52   569.6 2141.83   655.7 2141.51   689.6 2139.07
     715 2133.41   798.9 2133.38   808.3 2133.41   808.3 2133.42   833.4 2147.16
   880.3 2184.85   926.9 2186.93   935.4 2200.95   939.6  2211.7   948.1 2239.18
   949.6 2241.15   960.8 2254.95   984.1 2275.68   998.9 2295.19  1026.4 2315.25
#Mann= 6 ,-1,0
       0      .1       0     150     .06       0  427.38      .1       0
     715    .045       0   808.3     .06       0 1017.38      .1       0
Bank Sta=715,808.3
XS Rating Curve= 0 ,0
Exp/Cntr(USF)=0,0
Exp/Cntr=0.3,0.1

Type RM Length L Ch R = 1 ,95273   ,328.9,322.5,322.9
XS GIS Cut Line= 4
2324236.22446386698992.894096963 2324145.6862605699083.432300318
2323586.71126588699307.8095868942323452.87218266699473.140219107
#Sta/Elev= 30
       0 2254.18    90.6 2212.05   116.2 2195.11     134 2194.02   138.3 2192.05
   154.2 2179.81   168.5 2180.99   182.8 2178.01   198.6  2169.3   215.9 2165.18
   225.9 2160.05   250.4 2159.31   276.2 2153.03   293.6 2146.42   306.4 2144.47
     565 2144.47     573 2141.19   577.9 2134.54   582.2 2132.62   668.4 2132.59
   710.9 2132.62   733.1 2142.42   778.6 2179.57   787.2 2180.98   814.5 2177.85
   818.5 2178.84   823.4 2183.85   829.8 2194.89   845.4 2217.46   943.1 2283.58
#Mann= 10 ,-1,0
       0     .06       0     110      .1       0  218.04     .06       0
  248.04      .1       0  328.04     .06       0  438.04      .1       0
   582.2    .045       0   710.9      .1       0  760.37     .06       0
  880.37      .1       0
Bank Sta=582.2,710.9
XS Rating Curve= 0 ,0
Exp/Cntr(USF)=0,0
Exp/Cntr=0.3,0.1

Type RM Length L Ch R = 1 ,94950   ,598,545.8,517.5
XS GIS Cut Line= 3
2324090.57604976698748.8345922672323275.73221957699091.305187566
2323173.38468534699284.190925149
#Sta/Elev= 30
       0 2280.77    67.7 2260.83    93.7 2249.65    99.9 2244.55   115.1 2223.39
   119.8 2219.47   155.7 2218.15     164  2211.6   176.2 2193.37   182.3 2187.81
   210.9 2183.77   258.7 2150.29     276 2147.29   289.3 2140.31   479.9 2143.33
     497 2138.76   510.3 2132.03   570.3 2135.53     597    2132   701.2 2131.99
   705.5 2132.19     720 2141.57   744.8 2144.55   866.7 2145.42   883.9 2151.64
   914.5 2175.94   961.9 2176.93  1002.4 2214.22    1021  2228.2  1102.2  2276.2
#Mann= 7 ,-1,0
       0      .1       0      30     .06       0     220      .1       0
     597    .045       0   701.2      .1       0  933.89     .06       0
 1043.89      .1       0
Bank Sta=597,701.2
XS Rating Curve= 0 ,0
Exp/Cntr(USF)=0,0
Exp/Cntr=0.3,0.1

Type RM Length L Ch R = 1 ,94404   ,411,395.4,383
XS GIS Cut Line= 2
2323370.20686655698260.7155828752322949.00739877699170.034060049
#Sta/Elev= 30
       0 2260.33     9.3 2252.89    22.6 2236.66    66.6 2236.83    71.2 2232.94
    80.2 2217.25    84.3 2212.19    97.5 2199.92     119 2198.68   128.4 2200.83
     146 2194.58   176.6 2162.92   191.7 2137.68   203.7    2129   206.7 2128.94
   317.9    2129   330.3 2132.02   344.4 2138.35   388.4 2138.13   441.7 2142.21
     740 2141.59   780.8 2143.72   811.6 2169.61   820.5 2174.25   860.1 2174.24
   869.6 2177.14   932.8 2230.42   943.9 2235.81   962.9  2252.6  1002.1 2279.71
#Mann= 6 ,-1,0
       0     .06       0      90      .1       0   203.7    .045       0
   317.9      .1       0     740     .06       0     930      .1       0
Bank Sta=203.7,317.9
XS Rating Curve= 0 ,0
Exp/Cntr(USF)=0,0
Exp/Cntr=0.3,0.1

Type RM Length L Ch R = 1 ,94009   ,463.3,461,458.3
XS GIS Cut Line= 3
2322933.26162427698138.6858305272322779.74032293698922.038111729
 2322693.1385632699051.940751325
#Sta/Elev= 30
       0 2210.39    14.8 2209.28    31.1 2201.55    51.5 2206.18    63.7 2203.84
    75.9 2195.71   124.8 2156.03   156.4 2138.33   165.6 2135.32   173.7 2128.53
   177.8  2128.5   304.2  2128.5   332.7 2140.63   381.6 2140.95   406.1 2137.39
   426.5  2139.3   497.2 2140.24   524.3 2138.19   536.5 2140.09   569.1 2138.71
   695.5 2141.59   715.4 2144.87   728.1  2152.1   756.6 2173.19   772.9 2174.78
   797.4 2174.19   821.3 2194.11   845.3 2219.55   859.7 2232.28   954.4 2296.26
#Mann= 7 ,-1,0
       0     .07       0      10     .06       0     110      .1       0
   173.7    .045       0   304.2      .1       0     710     .06       0
  808.25      .1       0
Bank Sta=173.7,304.2
XS Rating Curve= 0 ,0
Exp/Cntr(USF)=0,0
Exp/Cntr=0.3,0.1