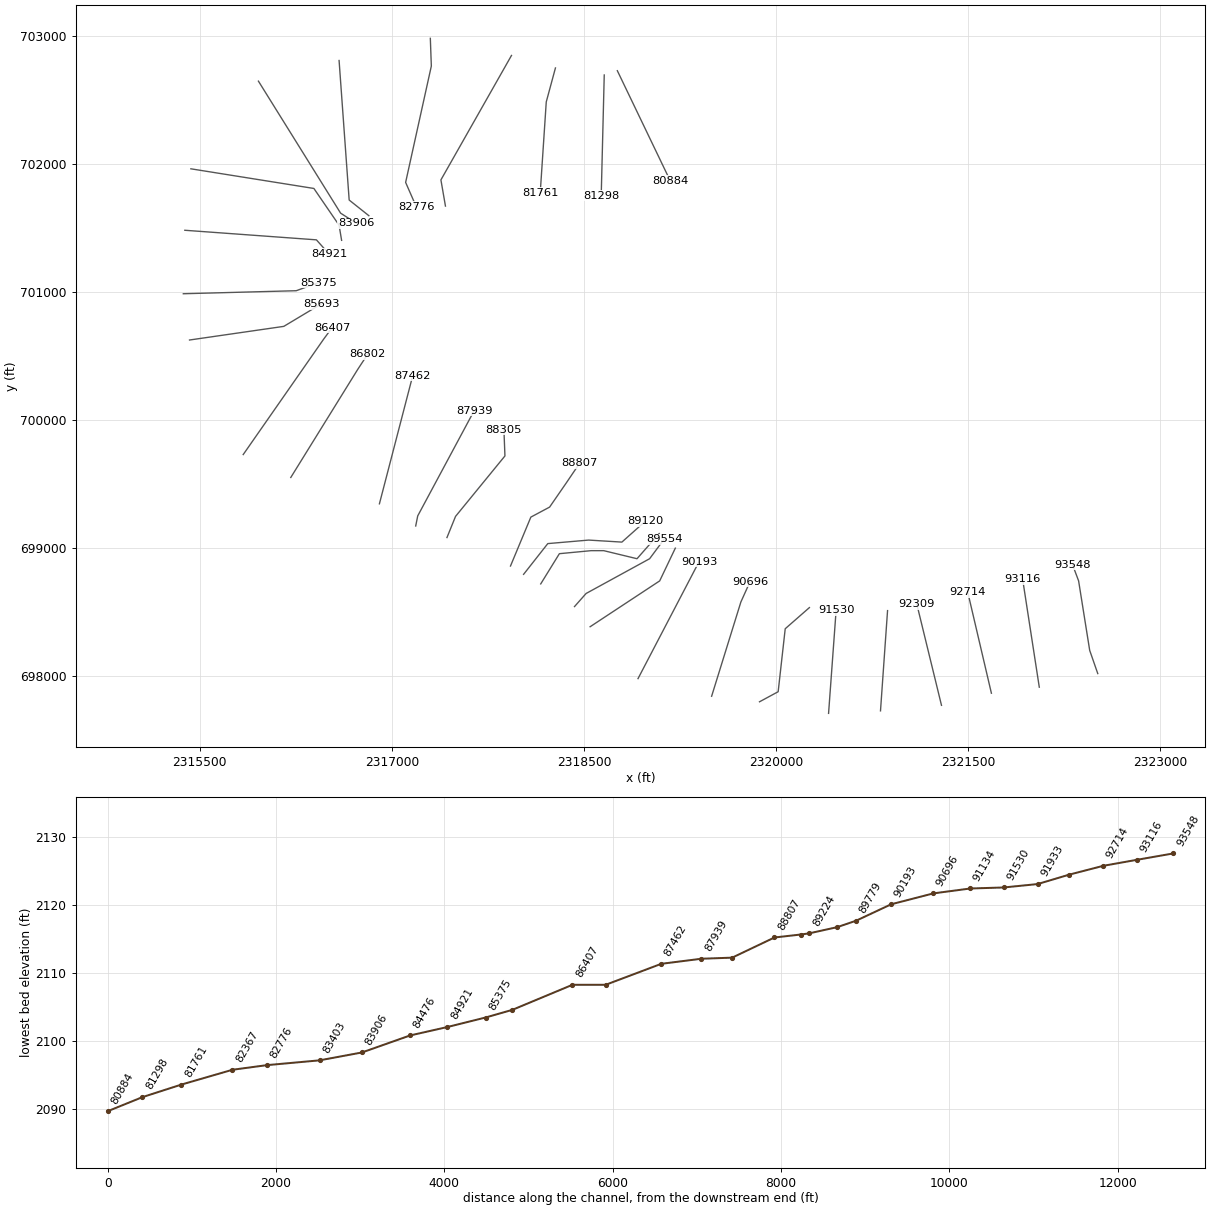
HEC-RAS study SHAVERSFK.prj: SHAVERSFK

--- SHAVERSFK.g01 (geometry) --- (continued)

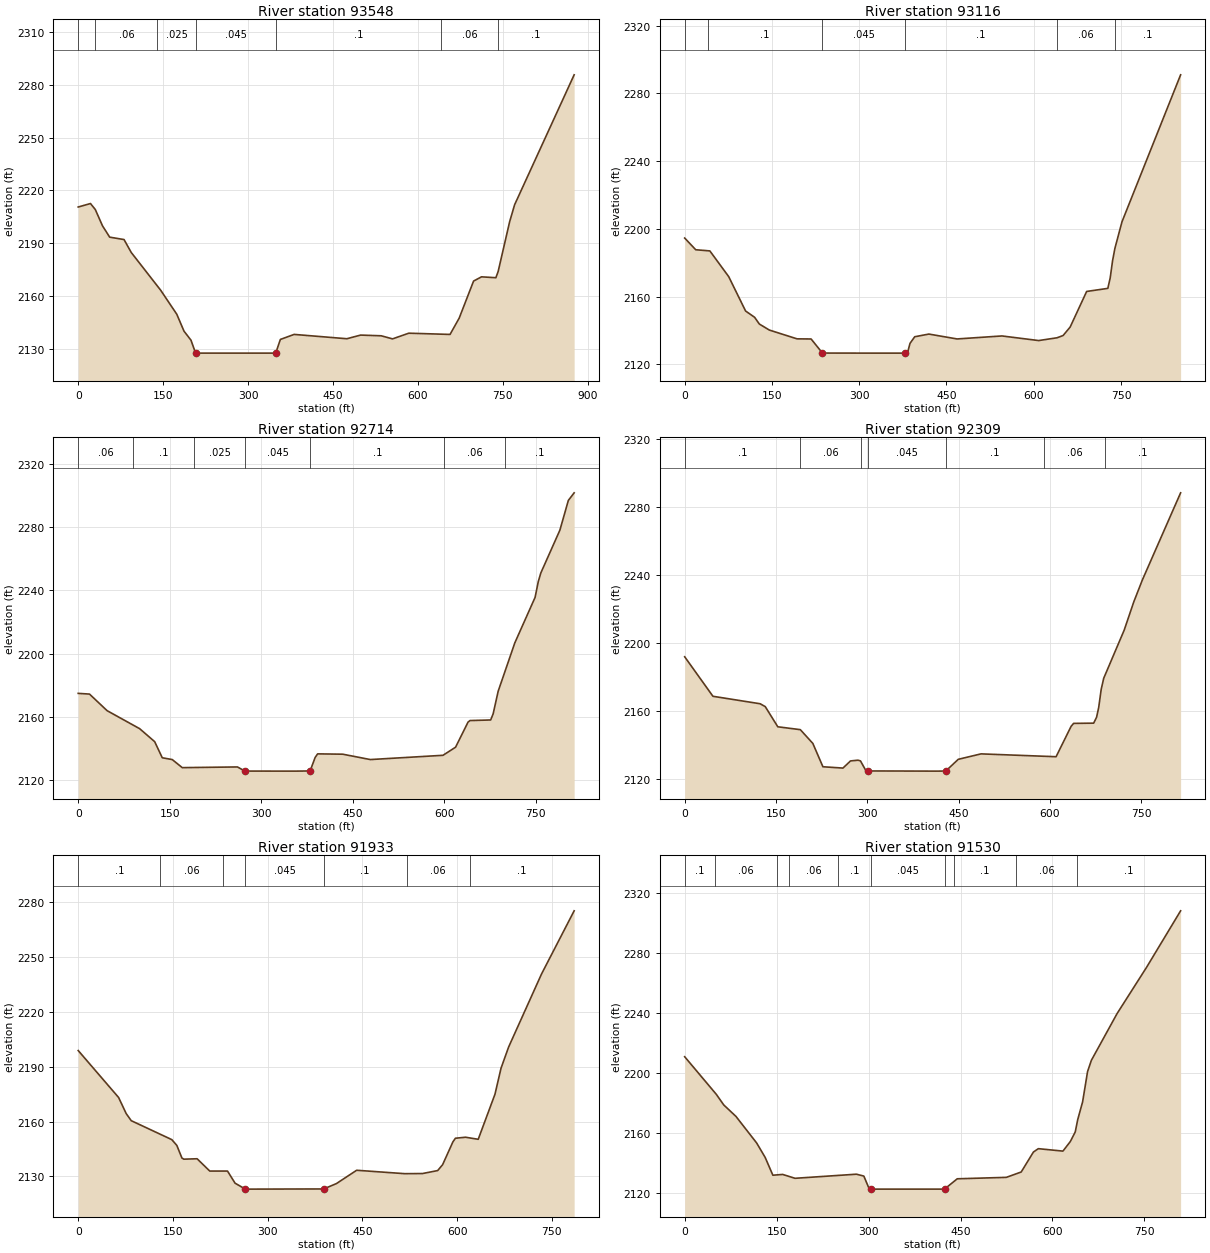
Type RM Length L Ch R = 1 ,93548   ,432.8,432.4,432
XS GIS Cut Line= 4
2322512.06215649698016.656078179 2322449.0790585698197.732484889
2322362.47729877698740.9617050192322315.23997528698866.927900991
#Sta/Elev= 30
       0  2210.6    21.7 2212.57    30.2 2209.17    42.9 2199.91    55.6 2193.48
      81 2192.11    93.7 2184.78   145.8  2163.3   174.2 2149.68   186.9 2140.11
   199.3 2134.94   207.4 2127.62   307.3 2127.61     349 2127.62   357.2 2135.38
   381.5 2138.24   474.7 2135.78     499 2137.86   535.5 2137.45   555.4  2135.7
   584.1 2138.93     657 2138.23   673.2 2147.51   698.6 2168.54   712.6 2170.94
     738 2170.44     742 2173.96   762.4 2202.34   771.1 2211.88   876.3 2285.67
#Mann= 7 ,-1,0
       0      .1       0      30     .06       0     140    .025       0
   207.4    .045       0     349      .1       0  641.72     .06       0
  741.72      .1       0
Bank Sta=207.4,349
XS Rating Curve= 0 ,0
Exp/Cntr(USF)=0,0
Exp/Cntr=0.3,0.1

Type RM Length L Ch R = 1 ,93116   ,400.5,401.4,406.1
XS GIS Cut Line= 2
2322055.43469609697910.3721003272321925.53205649698752.771035891
#Sta/Elev= 30
       0 2194.61      19  2187.7    43.3 2187.01    75.7 2171.82   104.7 2151.53
   120.2 2147.83   128.3 2143.85   145.6 2140.28   193.1  2135.1   217.3 2135.02
   236.8 2126.71   320.9 2126.67   379.2 2126.67   383.3 2127.25   387.3 2132.42
   395.4 2136.34   419.7 2137.92   468.2 2135.04   545.3 2136.81   608.4 2134.09
     640 2135.73   650.4 2137.06   662.5 2142.04   690.9 2163.08   727.3  2164.9
   731.4 2171.11   735.4 2181.13   739.4 2188.45   751.6 2204.18   852.4 2290.97
#Mann= 6 ,-1,0
       0     .06       0      40      .1       0   236.8    .045       0
   379.2      .1       0     640     .06       0     740      .1       0
Bank Sta=236.8,379.2
XS Rating Curve= 0 ,0
Exp/Cntr(USF)=0,0
Exp/Cntr=0.3,0.1

Type RM Length L Ch R = 1 ,92714   ,404.8,405.1,407.8
XS GIS Cut Line= 2
 2321681.4725518697863.1347768372321496.45970146698654.359945288
#Sta/Elev= 30
       0 2174.92    18.5 2174.47    47.3    2164   100.7  2152.6   125.3  2144.4
   137.7 2134.23   154.1 2133.08   170.5 2127.98   260.9 2128.42   273.2 2125.81
   355.4 2125.78     380 2125.89   388.2  2134.4   392.3 2136.69   433.4 2136.48
   478.6 2133.09   597.7 2135.78   618.3  2140.9   638.8  2156.8     642 2157.74
   675.8 2158.11   679.9 2162.01   688.1 2176.26   715.3 2206.76   748.6 2235.59
   753.8  2245.5     758 2251.02   789.2 2278.03   803.1 2296.87   812.6 2301.66
#Mann= 7 ,-1,0
       0     .06       0      90      .1       0     190    .025       0
   273.2    .045       0     380      .1       0     600     .06       0
     700      .1       0
Bank Sta=273.2,380
XS Rating Curve= 0 ,0
Exp/Cntr(USF)=0,0
Exp/Cntr=0.3,0.1

Type RM Length L Ch R = 1 ,92309   ,393.7,375.9,355.3
XS GIS Cut Line= 2
2321291.76463301697768.6601298582321098.87889543698559.885298309
#Sta/Elev= 30
       0 2191.71    46.4 2168.48     124 2164.08   132.3 2162.41   152.9 2150.55
   189.9 2148.86   210.5 2140.75     227 2127.05   259.9 2126.27   272.3 2130.47
   284.6 2130.91   288.7 2130.49     297 2125.15   300.7 2124.59   412.2 2124.48
   428.7 2124.52   449.3 2131.43   486.7 2134.62   609.9 2132.95   634.6 2150.83
   638.7 2152.55   671.6 2152.68   676.4 2156.15   679.9 2161.95     684  2172.6
   688.1 2179.06   721.7 2207.34   737.5 2223.99   751.5  2236.8   814.4 2288.09
#Mann= 7 ,-1,0
       0      .1       0     190     .06       0     290    .025       0
   300.7    .045       0   428.7      .1       0     590     .06       0
     690      .1       0
Bank Sta=300.7,428.7
XS Rating Curve= 0 ,0
Exp/Cntr(USF)=0,0
Exp/Cntr=0.3,0.1

Type RM Length L Ch R = 1 ,91933   ,402.7,402.7,402.6
XS GIS Cut Line= 2
2320815.45495449697725.3592499932320870.56516523698508.711531195
#Sta/Elev= 30
       0 2198.85      64 2173.17      76 2164.37      84  2160.5   148.2 2150.15
   156.2 2146.97   164.2  2140.1   167.2 2139.47   188.3 2139.69   208.3 2132.97
   236.4 2132.97   248.4 2126.33   264.5 2123.14   268.5 2123.09   388.8 2123.19
   408.9 2126.13   440.9  2133.4   517.1 2131.54   545.2 2131.61   569.2 2133.24
     577 2136.44   593.3  2148.9   597.3 2150.91   613.3 2151.46   633.4 2150.33
   659.9 2174.94   669.5 2189.16   681.5 2200.74   733.6 2240.67   785.3 2275.23
#Mann= 7 ,-1,0
       0      .1       0     130     .06       0     230    .025       0
   264.5    .045       0   388.8      .1       0     520     .06       0
     620      .1       0
Bank Sta=264.5,388.8
XS Rating Curve= 0 ,0
Exp/Cntr(USF)=0,0
Exp/Cntr=0.3,0.1

Type RM Length L Ch R = 1 ,91530   ,398.4,396.4,394.3
XS GIS Cut Line= 2
 2320410.0012612697705.6770318722320469.04791556698512.647974819
#Sta/Elev= 30
       0 2210.77    51.6 2185.72    63.7 2178.68    83.7    2171   117.4 2153.34
   131.3 2143.73   143.9 2131.85   159.9 2132.38     180  2129.8   280.2 2132.53
   292.3 2131.28   300.3 2123.51   304.3  2122.6   304.3 2122.59   423.9  2122.6
   444.7 2129.47   524.8 2130.43     549 2133.99     569 2147.32     577 2149.53
   617.1 2147.91   629.2 2154.31   637.2 2160.69   641.2 2168.85   649.2 2180.69
   657.3 2200.88   663.5 2208.37   705.4 2239.47   753.5 2270.27   809.1 2307.93
#Mann= 10 ,-1,0
       0      .1       0      50     .06       0     150      .1       0
     170     .06       0     250      .1       0   304.3    .045       0
   423.9    .025       0     440      .1       0     540     .06       0
     640      .1       0
Bank Sta=304.3,423.9
XS Rating Curve= 0 ,0
Exp/Cntr(USF)=0,0
Exp/Cntr=0.3,0.1

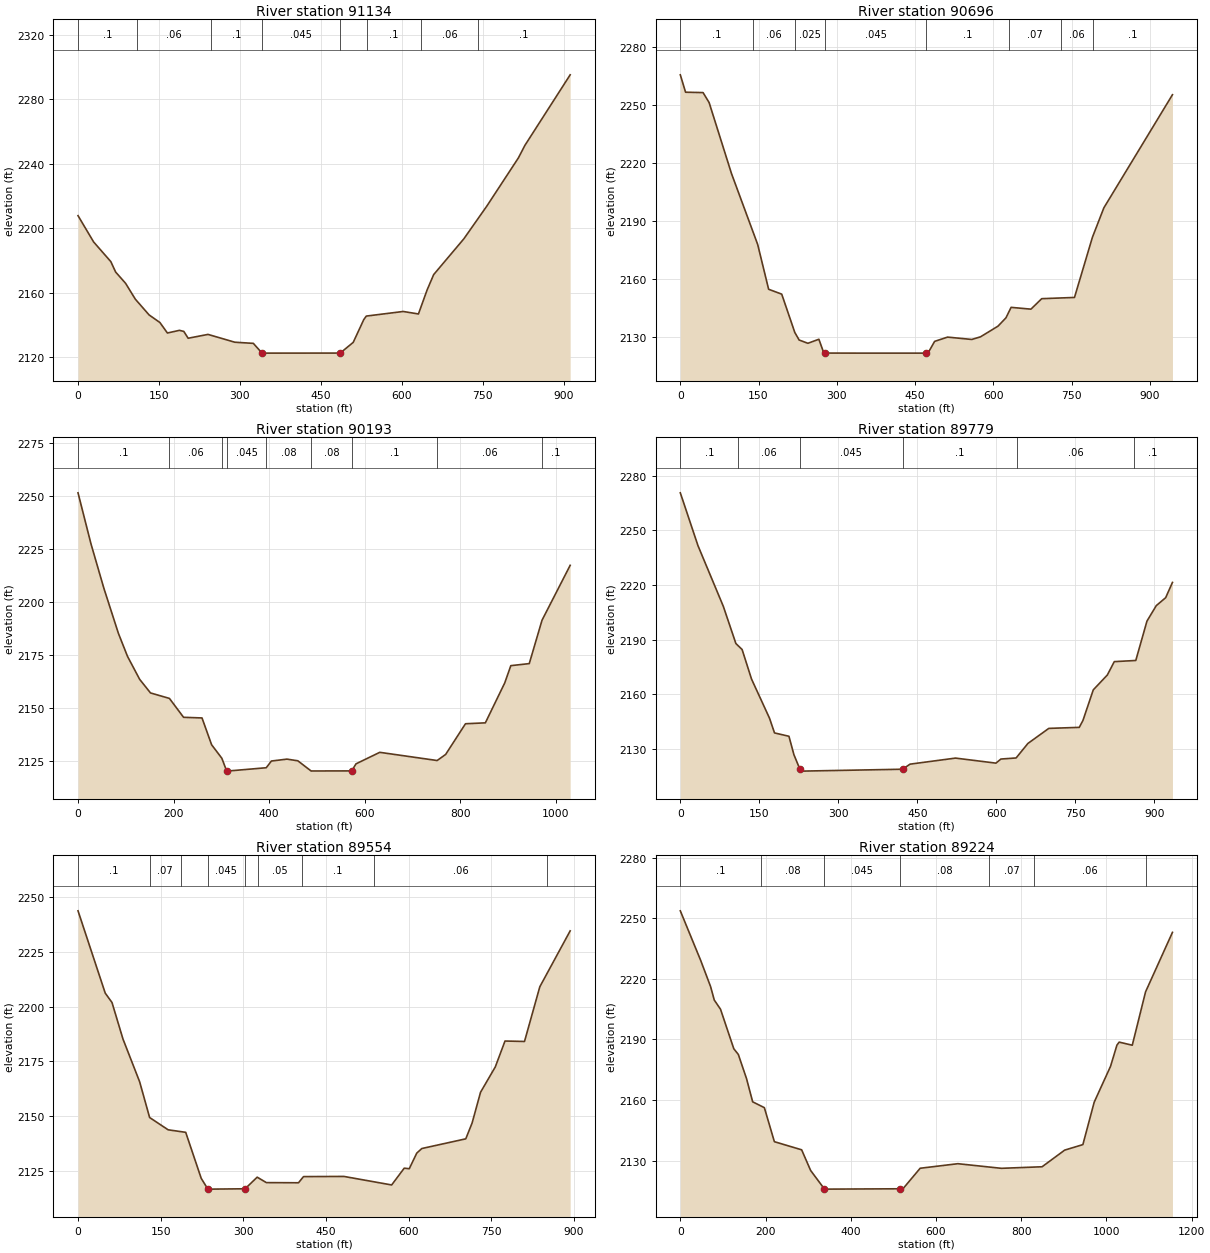
Type RM Length L Ch R = 1 ,91134   ,460.6,438.5,427
XS GIS Cut Line= 4
 2319870.7084847697796.2152352272320016.35689879 697874.94410771
2320071.46710953698366.9995607262320260.41640349 698532.33019294
#Sta/Elev= 30
       0 2207.76    28.9 2191.45    60.8 2179.23    69.7 2172.76    88.1 2165.78
   106.2 2155.92   131.7 2146.15   151.7 2141.44   165.6 2134.94   187.9 2136.58
     196 2135.92     204 2131.68   240.8 2134.06   290.5 2129.21   324.8  2128.5
   340.9 2122.47   344.8 2122.44   485.8 2122.47   509.9 2129.13   529.4 2143.23
   534.1 2145.43   602.5 2148.29   630.7 2146.74   646.8 2161.68   658.9 2171.17
   714.8 2193.37   757.3 2213.65   815.9 2243.61     828 2251.42   911.8 2295.17
#Mann= 8 ,-1,0
       0      .1       0     110     .06       0  245.56      .1       0
   340.9    .045       0   485.8    .025       0  535.56      .1       0
  635.56     .06       0   740.7      .1       0
Bank Sta=340.9,485.8
XS Rating Curve= 0 ,0
Exp/Cntr(USF)=0,0
Exp/Cntr=0.3,0.1

Type RM Length L Ch R = 1 ,90696   ,534.5,502.2,491.1
XS GIS Cut Line= 3
 2319496.7463404697839.516115093 2319725.0600706698575.631072805
2319795.91605584 698733.08881777
#Sta/Elev= 30
       0 2265.54    10.1 2256.55    43.6 2256.36    55.2 2251.22    98.1 2214.52
   148.3 2177.88   169.3 2154.72   194.4  2152.2   219.5 2132.38   227.8 2128.49
   244.6 2126.81   265.6 2128.89     274 2122.62   278.1 2121.75   336.5 2121.72
   470.8 2121.72     475 2121.84   487.5 2127.79   512.3    2130   558.7 2128.78
   575.5 2130.15     609 2135.66   624.2 2139.95   634.1 2145.37   672.1 2144.44
   692.8 2149.86   755.6 2150.49     790  2181.6   811.9  2196.8   943.4 2255.26
#Mann= 8 ,-1,0
       0      .1       0     140     .06       0     220    .025       0
   278.1    .045       0   470.8      .1       0     630     .07       0
     730     .06       0  790.71      .1       0
Bank Sta=278.1,470.8
XS Rating Curve= 0 ,0
Exp/Cntr(USF)=0,0
Exp/Cntr=0.3,0.1

Type RM Length L Ch R = 1 ,90193   ,415.7,414.6,316
XS GIS Cut Line= 2
2318922.02557128697977.291641937 2319398.3352498698890.546562736
#Sta/Elev= 30
       0 2251.57    26.9 2227.65      54 2206.57    84.5  2185.2   103.6  2174.3
     129 2163.47   151.7 2157.04   191.3 2154.46   220.9 2145.53   259.5 2145.23
   279.6 2132.56     301 2126.19   311.2 2120.11   393.9 2121.71   404.7 2124.88
   437.4 2125.78     460 2124.99   487.8 2120.18   572.8 2120.22   581.8 2123.55
   631.5 2128.99   751.6 2125.12   769.4 2127.99   810.9 2142.49   852.5 2142.91
   893.1 2161.79   905.8 2169.93   944.4  2170.9   971.1 2191.39    1030 2217.32
#Mann= 9 ,-1,0
       0      .1       0   191.3     .06       0     301      .1       0
   311.2    .045       0   393.9     .08       0   487.8     .08       0
   572.8      .1       0   751.6     .06       0   971.1      .1       0
Bank Sta=311.2,572.8
XS Rating Curve= 0 ,0
Exp/Cntr(USF)=0,0
Exp/Cntr=0.3,0.1

Type RM Length L Ch R = 1 ,89779   ,226.5,224.4,263.6
XS GIS Cut Line= 3
2318548.06342699698382.7453352232319091.29264712698740.961705019
2319213.32239947698996.830540587
#Sta/Elev= 30
       0 2270.58    33.6 2241.51    81.6 2208.26   105.5 2187.79   117.3  2184.5
   135.2 2168.27   169.3 2146.79   178.8 2138.69   206.2 2136.84   215.7 2126.68
   227.1 2118.71   229.9  2117.7   421.8 2118.74   436.1 2121.53   522.4 2124.86
   599.1 2122.09   608.6 2124.34   637.4 2124.93   659.8  2132.9   699.5 2141.18
   757.3 2141.74   764.3 2145.54   783.9 2162.34   810.6 2170.51   823.8 2177.85
   864.6 2178.48   885.8 2200.11   903.5 2208.62   921.3 2212.97   934.2 2221.36
#Mann= 6 ,-1,0
       0      .1       0     110     .06       0   227.1    .045       0
   421.8      .1       0     640     .06       0   860.7      .1       0
Bank Sta=227.1,421.8
XS Rating Curve= 0 ,0
Exp/Cntr(USF)=0,0
Exp/Cntr=0.3,0.1

Type RM Length L Ch R = 1 ,89554   ,357.5,330.9,280.1
BEGIN DESCRIPTION:
Structure XS 4
END DESCRIPTION:
XS GIS Cut Line= 4
2318426.03367464698540.203080188  2318516.571878698642.550614415
2319012.56377464 698914.165224482319126.72063974699067.686525821
#Sta/Elev= 30
       0 2243.69    49.4 2206.15    61.7 2201.87    81.6 2185.22   111.9  2165.7
     130 2149.41   163.6 2143.81   195.5 2142.66   223.7 2121.65   235.5 2116.86
   241.1 2116.75   303.3 2116.91   325.3  2122.2     342 2119.72   400.3 2119.65
   409.4 2122.46   482.8 2122.54   569.4 2118.65   592.2  2126.3   601.4 2126.07
     615 2133.18   624.2 2135.27     704 2139.69   715.5 2146.94   730.8 2160.93
   757.6 2172.51   775.2  2184.3   810.6  2184.1   838.4 2209.05   893.5 2234.55
#Mann= 9 ,-1,0
       0      .1       0     130     .07       0  186.65     .08       0
   235.5    .045       0   303.3      .1       0  326.65     .05       0
  406.65      .1       0  536.65     .06       0  852.14      .1       0
Bank Sta=235.5,303.3
XS Rating Curve= 0 ,0
Exp/Cntr(USF)=0,0
Exp/Cntr=0.3,0.1

Type RM Length L Ch R = 1 ,89224   ,126.1,103.1,102.2
BEGIN DESCRIPTION:
Structure XS 3
END DESCRIPTION:
XS GIS Cut Line= 6
2318162.29195182698717.3430432742318307.94036592698953.529660722
2318555.93631424698977.1483224662318654.34740484698977.148322466
2318914.15268403 698914.165224482319087.35620349699110.987405687
#Sta/Elev= 30
       0 2253.75    47.8 2229.18      71 2216.23    79.7 2209.53    94.3    2205
   125.5 2185.41   136.1 2182.59   155.3 2170.65   169.8  2159.1   197.2 2156.21
   220.7 2139.35   284.7 2135.32   305.8 2125.08     338 2115.95     342 2115.84
   515.8 2116.01   522.8 2116.12   562.8 2126.18   651.3 2128.44   753.3 2126.15
   848.9 2126.92   901.9 2135.17   944.6  2137.9   971.2 2158.94  1009.5 2176.69
  1024.5  2187.2  1029.8 2188.69  1060.5 2187.15  1091.7  2213.6  1154.8 2243.07
#Mann= 7 ,-1,0
       0      .1       0     190     .08       0     338    .045       0
   515.8     .08       0  725.01     .07       0  829.31     .06       0
  1092.6      .1       0
Bank Sta=338,515.8
XS Rating Curve= 0 ,0
Exp/Cntr(USF)=0,0
Exp/Cntr=0.3,0.1

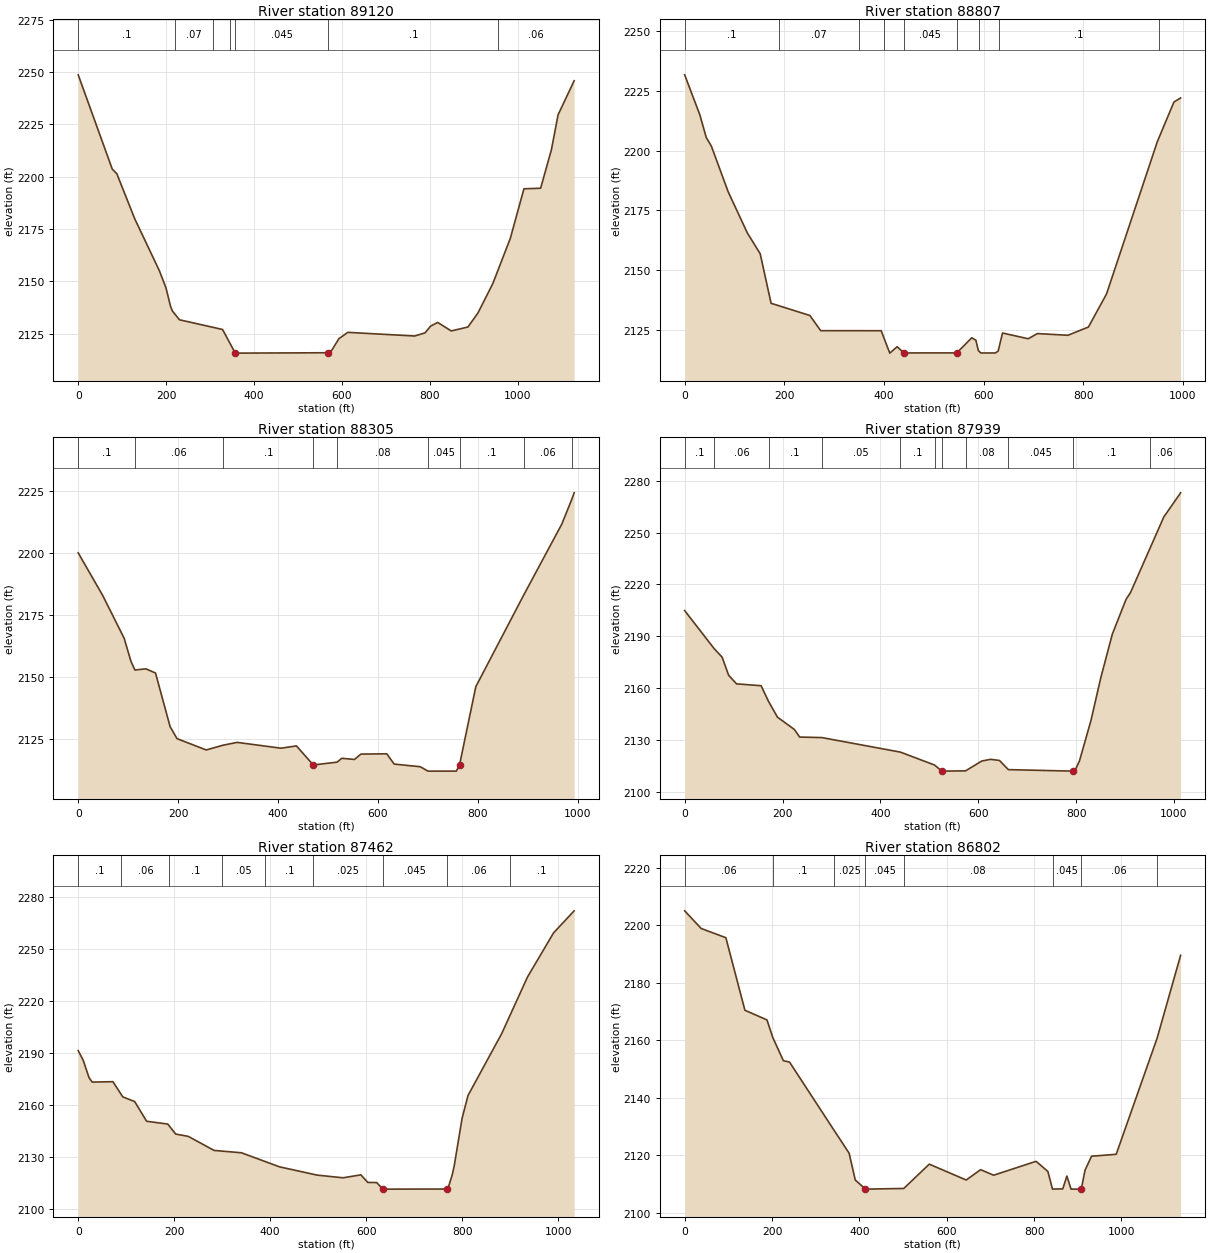
Type RM Length L Ch R = 1 ,89120   ,268.4,313.1,372.2
BEGIN DESCRIPTION:
Structure XS 2
END DESCRIPTION:
XS GIS Cut Line= 5
 2318028.4528686698792.1354721322318217.40216256699032.258533204
2318536.25409612699059.8136385732318796.05937531699044.067864077
2318977.13578202699205.462052666
#Sta/Elev= 30
       0 2248.73    77.5 2203.64    87.9 2201.44   128.7 2179.85   184.6  2155.1
   199.8 2146.82     210 2138.08   214.2 2135.84   230.4  2131.6   328.4 2126.97
     357  2115.8   360.5 2115.66   569.3 2115.84     575  2116.4   593.2 2122.58
   613.5 2125.59   765.8 2123.84   789.1 2125.36   801.8 2128.56   817.9 2130.34
   848.8 2126.27   886.7 2128.15   909.4 2134.81   943.4 2148.94   983.1  2170.5
  1014.2 2194.24  1052.1  2194.5  1076.6 2212.86  1091.9 2229.63  1128.4 2245.89
#Mann= 7 ,-1,0
       0      .1       0     220     .07       0  305.55     .08       0
  345.55      .1       0     357    .045       0   569.3      .1       0
  955.87     .06       0
Bank Sta=357,569.3
XS Rating Curve= 0 ,0
Exp/Cntr(USF)=0,0
Exp/Cntr=0.3,0.1

Type RM Length L Ch R = 1 ,88807   ,482,502.6,522.5
BEGIN DESCRIPTION:
Structure XS 1
END DESCRIPTION:
XS GIS Cut Line= 5
2317926.18444445 698857.112327072318085.22237482699239.388969949
2318231.62311672699317.5727219822318363.64539882699509.060893342
2318465.99293306699660.225936467
#Sta/Elev= 30
       0  2231.8    30.4 2215.07    43.4  2205.5    53.6 2201.91    87.2 2182.86
   125.7 2165.58   151.5 2156.87   173.4  2136.1   251.3 2130.98     273 2124.62
   394.3 2124.61   411.6 2115.22   426.4  2117.9439.84732115.303545.94732115.314
   576.1 2121.64   584.4 2120.61   589.2 2116.37   594.1 2115.28   623.3 2115.28
     629 2116.03   637.8 2123.65   689.4 2121.24   707.8 2123.41     769  2122.7
   810.2 2126.15   846.6 2140.03   948.4 2203.77   981.8 2220.41   995.2 2222.11
#Mann= 9 ,-1,0
       0      .1       0     190     .07       0     350    .025       0
     400     .06       0439.8473    .045       0545.9473     .07       0
  590.01    .025       0  630.01      .1       0   952.6     .06       0
Bank Sta=439.8473,545.9473
XS Rating Curve= 0 ,0
Exp/Cntr(USF)=0,0
Exp/Cntr=0.3,0.1

Type RM Length L Ch R = 1 ,88305   ,318.9,365.4,374.3
XS GIS Cut Line= 4
2317430.11343774699079.4958566942317497.03297935699244.826488907
2317882.80445451699717.1997238032317874.93156726699921.894792258
#Sta/Elev= 30
       0 2200.03      49 2182.91      92 2165.69   105.4 2156.53   113.5 2152.92
   135.6 2153.38   154.8 2151.71     184 2130.15   197.9 2125.31   256.3 2120.77
   290.8 2122.71   318.3 2123.81     406 2121.47     437 2122.39   470.8 2114.72
   518.5 2115.87   527.7 2117.41   553.2 2116.95   566.1  2119.1   617.8 2119.22
   632.8 2115.08   684.9 2114.02   700.4 2112.25   757.2 2112.25   763.6 2114.74
   796.2 2146.22   892.3 2183.13   968.4  2211.6   988.4 2221.58   993.1 2224.17
#Mann= 9 ,-1,0
       0      .1       0   113.5     .06       0   290.8      .1       0
   470.8    .045       0   518.5     .08       0   700.4    .045       0
   763.6      .1       0   892.3     .06       0   988.4      .1       0
Bank Sta=470.8,763.6
XS Rating Curve= 0 ,0
Exp/Cntr(USF)=0,0
Exp/Cntr=0.3,0.1

Type RM Length L Ch R = 1 ,87939   ,473.5,477.2,490.8
XS GIS Cut Line= 3
2317186.05393304699170.0340600492317201.79970754699248.762932532
2317642.68139344700071.479649975
#Sta/Elev= 30
       0  2204.9    60.3  2182.9    76.6 2177.95    89.8 2167.55     106 2162.54
   156.2 2161.48   171.5 2152.36   189.7 2143.28   224.2 2136.18   235.1 2131.79
   280.3 2131.49     441 2123.08   510.8 2115.61   525.6 2112.09   574.2 2112.25
   607.2 2117.92   625.3 2118.92   643.5 2118.25   661.6 2112.96   793.2 2112.09
   797.8 2112.46   806.9 2117.96   830.5 2141.41   850.6 2166.15   874.2 2191.36
   902.2 2211.41   911.2 2215.28     951 2240.84   979.3 2259.02  1013.7 2272.99
#Mann= 11 ,-1,0
       0      .1       0    60.3     .06       0   171.5      .1       0
   280.3     .05       0     441      .1       0   510.8    .025       0
   525.6    .045       0   574.2     .08       0   661.6    .045       0
   793.2      .1       0     951     .06       0
Bank Sta=525.6,793.2
XS Rating Curve= 0 ,0
Exp/Cntr(USF)=0,0
Exp/Cntr=0.3,0.1

Type RM Length L Ch R = 1 ,87462   ,648.7,660.3,470.9
XS GIS Cut Line= 2
 2316902.6299921699343.2375795112317162.43527129 700343.09426004
#Sta/Elev= 30
       0 2191.18    10.3 2185.72    22.5 2175.61    29.1 2173.07    72.3 2173.28
    92.9 2164.52   117.7 2161.81   142.5 2150.48   186.6 2148.85     203  2143.1
   229.2 2141.76     283 2133.66   340.2 2132.29   419.5 2124.18   497.9 2119.41
   551.7 2117.88   588.9 2119.57   603.2 2115.21   621.9 2115.12   634.3 2111.34
   767.2 2111.39   770.7 2112.13     779 2119.46   783.1 2124.48   799.6 2152.08
     812 2165.34     882 2200.91     936 2233.68   990.3 2259.12  1033.1  2271.8
#Mann= 9 ,-1,0
       0      .1       0      90     .06       0     190      .1       0
     300     .05       0     390      .1       0     490    .025       0
   634.3    .045       0   767.2     .06       0     900      .1       0
Bank Sta=634.3,767.2
XS Rating Curve= 0 ,0
Exp/Cntr(USF)=0,0
Exp/Cntr=0.3,0.1

Type RM Length L Ch R = 1 ,86802   ,395.6,394.7,362.2
XS GIS Cut Line= 3
2316210.56895657699549.0201517572316732.40559283700392.195160128
2316811.31571594700512.593656788
#Sta/Elev= 30
       0 2205.03    37.8 2198.88    94.3 2195.69   137.9 2170.46   188.4 2167.09
   201.8 2160.97     226 2152.91   240.1 2152.43   341.1 2128.93   376.5 2120.75
   390.6 2111.41   413.9 2108.27   414.1 2108.25   501.6 2108.48     560 2116.93
   644.6 2111.42   677.6 2115.02   707.4 2113.09   804.6 2117.92   831.5 2114.41
   842.2 2108.27   865.7 2108.34   875.1 2112.79   884.6 2108.25   908.1 2108.25
   916.6 2114.82   931.6  2119.7     988 2120.36  1081.7 2160.75  1135.5 2189.56
#Mann= 8 ,-1,0
       0     .06       0   201.8      .1       0   341.1    .025       0
   413.9    .045       0   501.6     .08       0   842.2    .045       0
   908.1     .06       0  1081.7      .1       0
Bank Sta=413.9,908.1
XS Rating Curve= 0 ,0
Exp/Cntr(USF)=0,0
Exp/Cntr=0.3,0.1

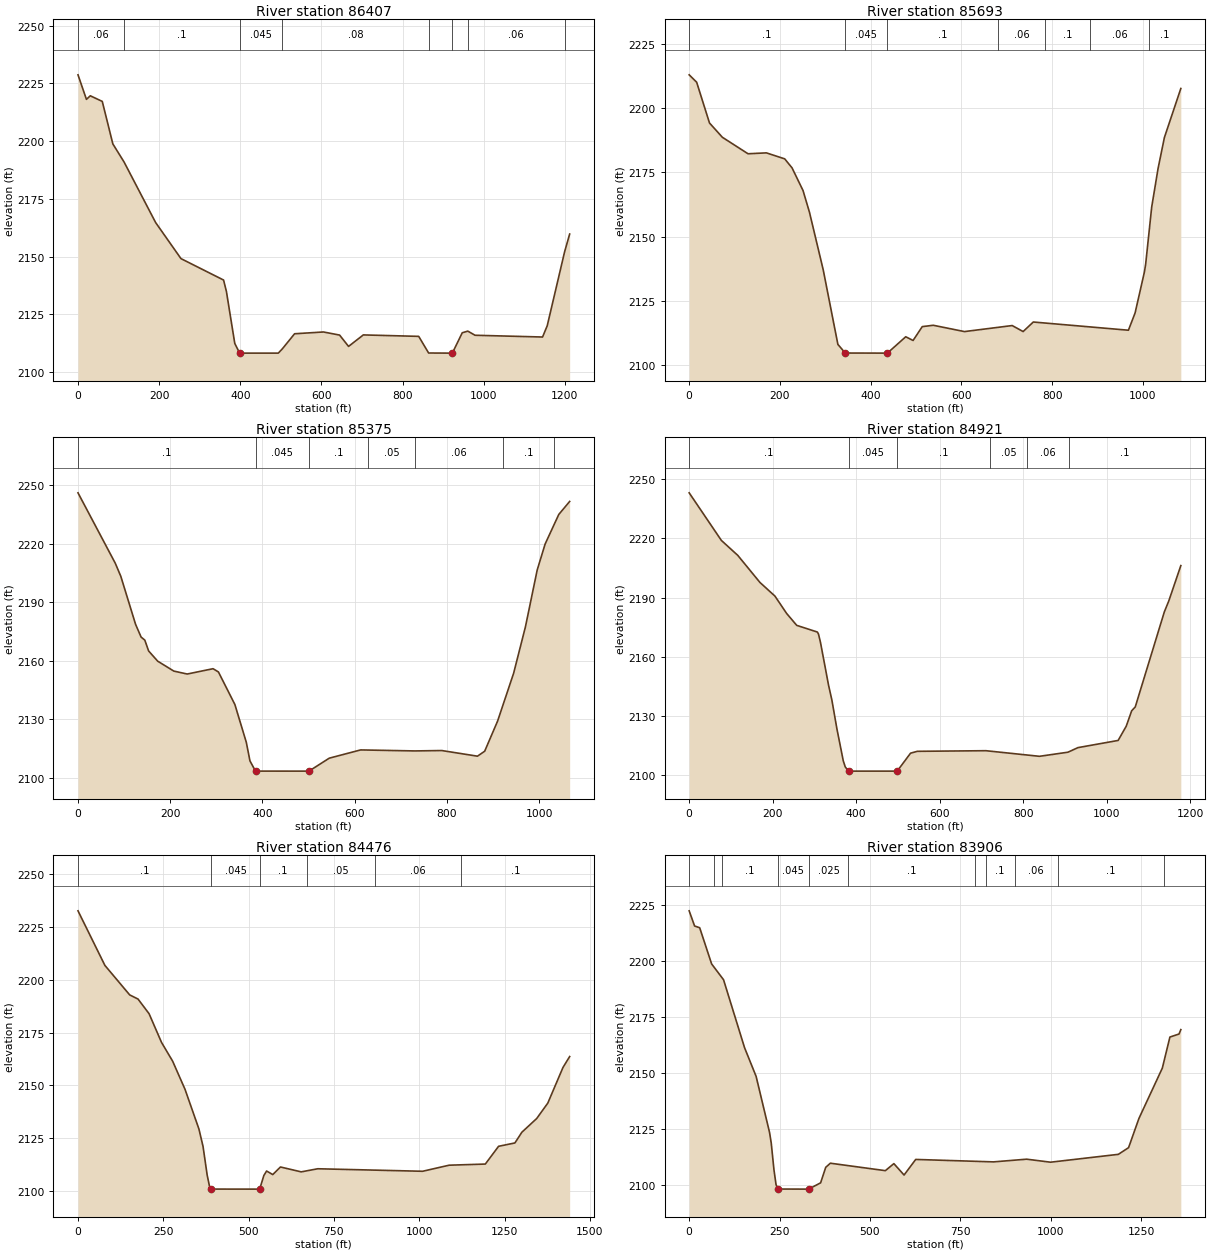
Type RM Length L Ch R = 1 ,86407   ,740.7,714,566.1
XS GIS Cut Line= 3
  2315839.101755699728.1137712272316466.13960641700628.415328896
2316534.05921701700720.635345605
#Sta/Elev= 30
       0 2228.67    20.8 2218.05    30.3  2219.6    59.8 2217.17    85.9 2198.78
   113.6 2190.93   191.4 2164.73   253.8 2149.14   358.8 2139.87   365.8 2134.91
   386.4 2112.44   398.1 2108.35   400.8 2108.25   493.6 2108.25   503.4 2110.06
   533.8 2116.63   604.9  2117.4   644.7 2116.06   666.8 2111.16   703.2 2116.13
   839.7  2115.5   864.1  2108.3   922.6 2108.25     947 2117.06   960.7 2117.77
   978.5 2115.98  1144.9 2115.22  1156.4 2120.07  1199.3 2152.13  1211.7 2159.77
#Mann= 8 ,-1,0
       0     .06       0   113.6      .1       0   398.1    .045       0
   503.4     .08       0   864.1    .045       0   922.6      .1       0
   960.7     .06       0  1199.3      .1       0
Bank Sta=398.1,922.6
XS Rating Curve= 0 ,0
Exp/Cntr(USF)=0,0
Exp/Cntr=0.3,0.1

Type RM Length L Ch R = 1 ,85693   ,322.7,318.5,313.3
XS GIS Cut Line= 3
2315419.85950022700623.2046193242316156.08028709700729.782808461
2316447.16215714700904.453695755
#Sta/Elev= 30
       0 2213.07    16.5 2210.19    44.8 2194.29    73.1 2188.73   129.7 2182.29
   170.1 2182.64   210.5 2180.31   226.7 2176.79   250.9 2167.95   265.1 2159.48
   295.4 2137.03   327.7 2107.97   343.9  2104.6   436.8 2104.56   477.2 2110.94
   493.4 2109.49   513.6 2114.89   537.9 2115.42   606.6 2112.96   711.8 2115.31
   735.9 2112.97   758.3 2116.69   967.9 2113.49   982.6 2120.22    1003 2136.08
  1005.9 2139.22  1019.2 2161.51  1033.2 2176.51  1047.2 2188.64  1083.4 2207.74
#Mann= 7 ,-1,0
       0      .1       0   343.9    .045       0   436.8      .1       0
     680     .06       0   783.9      .1       0   883.9     .06       0
  1013.9      .1       0
Bank Sta=343.9,436.8
XS Rating Curve= 0 ,0
Exp/Cntr(USF)=0,0
Exp/Cntr=0.3,0.1

Type RM Length L Ch R = 1 ,85375   ,458,453.3,446.5
XS GIS Cut Line= 3
2315371.35342231700984.7345707732316253.11679412701008.353232518
2316426.32031358701071.336330504
#Sta/Elev= 30
       0 2246.22    80.9 2210.08    92.9 2203.37   124.9 2178.74   136.9  2172.2
   144.9 2170.65   153.2 2165.08   172.9 2159.84   207.8 2154.76   236.9 2153.25
   292.9 2155.98   304.6 2154.31   340.3  2137.6     365 2118.27     373 2108.67
     385 2103.44     501 2103.43     545 2110.08     613 2114.31     730 2113.79
   789.1 2113.99   866.4  2111.1   882.1 2113.64   910.1  2129.1   944.9 2153.68
   970.5 2177.48     996 2206.62  1013.2 2219.95  1042.8 2235.11  1066.4 2241.79
#Mann= 7 ,-1,0
       0      .1       0     385    .045       0     501      .1       0
     630     .05       0     730     .06       0  922.08      .1       0
 1032.08     .06       0
Bank Sta=385,501
XS Rating Curve= 0 ,0
Exp/Cntr(USF)=0,0
Exp/Cntr=0.3,0.1

Type RM Length L Ch R = 1 ,84921   ,449.9,445.2,439.7
XS GIS Cut Line= 3
2315383.16275319701480.7264674142316410.57453908701405.934038555
2316508.98562969 701295.71361708
#Sta/Elev= 30
       0  2243.1    77.2 2218.96   116.4 2211.41   169.5 2197.69   205.6 2190.73
   233.6 2181.92   257.7 2175.92   307.1 2172.53   309.8 2171.52   314.6 2167.28
   333.9 2145.61   341.9 2138.07   353.9 2123.52   369.2 2107.24     374 2104.13
     382 2102.03   498.3 2102.03   530.4 2111.13   546.5 2112.07   710.9 2112.38
   839.2 2109.54   907.4 2111.62   931.4 2113.94  1027.7 2117.58  1047.2 2124.85
  1060.1 2132.62  1068.7 2134.55  1138.4 2182.76  1149.1 2188.33  1177.9 2206.21
#Mann= 6 ,-1,0
       0      .1       0     382    .045       0   498.3      .1       0
     720     .05       0     810     .06       0     910      .1       0
Bank Sta=382,498.3
XS Rating Curve= 0 ,0
Exp/Cntr(USF)=0,0
Exp/Cntr=0.3,0.1

Type RM Length L Ch R = 1 ,84476   ,615.9,569.9,531
XS GIS Cut Line= 4
2315430.40007668701960.9725895582316390.89232096701807.451288217
2316587.71450217701520.0909036552316607.39672029701401.997594931
#Sta/Elev= 30
       0 2232.67    78.8 2206.81   151.5 2192.82     176 2190.85   208.4 2183.88
   244.8  2170.3   277.3 2161.43   313.7 2148.04   354.4 2129.25   366.4 2121.02
   378.5 2107.45   386.6 2101.16   390.7  2100.8   532.4 2100.78   544.6 2107.24
   552.7 2109.36   570.7 2107.68   593.2 2111.27     654 2108.96   702.6 2110.43
  1009.8 2109.24  1087.5 2112.12  1193.6 2112.66  1232.4 2121.07  1280.3 2122.67
  1300.6 2127.73  1344.2 2134.26  1376.7 2141.56  1421.2 2158.46  1440.7 2163.61
#Mann= 6 ,-1,0
       0      .1       0   390.7    .045       0   532.4      .1       0
     670     .05       0     870     .06       0 1122.68      .1       0
Bank Sta=390.7,532.4
XS Rating Curve= 0 ,0
Exp/Cntr(USF)=0,0
Exp/Cntr=0.3,0.1

Type RM Length L Ch R = 1 ,83906   ,528.6,503.6,495.2
XS GIS Cut Line= 3
2315957.88352231702645.9137801572316599.52383304701614.565550634
2316721.55358539701535.836678152
#Sta/Elev= 30
       0 2222.29      15 2215.52    29.1 2214.76    62.1 2198.63    95.1 2191.58
   153.2  2161.3   185.2 2148.51   222.3 2123.56     227 2118.81   234.5 2106.92
   240.3 2100.27   245.8 2098.32   330.6 2098.28   363.6 2101.09   377.7 2107.99
   390.5 2109.83   542.6 2106.51   566.2 2109.64   594.4 2104.56   626.6 2111.51
   841.5 2110.42   933.6 2111.62   999.6 2110.28  1187.1 2113.78  1215.4 2116.77
    1244 2129.77  1308.7 2152.19  1329.7 2166.05    1355  2167.4  1359.9 2169.36
#Mann= 11 ,-1,0
       0      .1       0      70     .06       0      90      .1       0
   245.8    .045       0   330.6    .025       0     440      .1       0
     790     .05       0     820      .1       0     900     .06       0
    1020      .1       0 1314.65     .06       0
Bank Sta=245.8,330.6
XS Rating Curve= 0 ,0
Exp/Cntr(USF)=0,0
Exp/Cntr=0.3,0.1

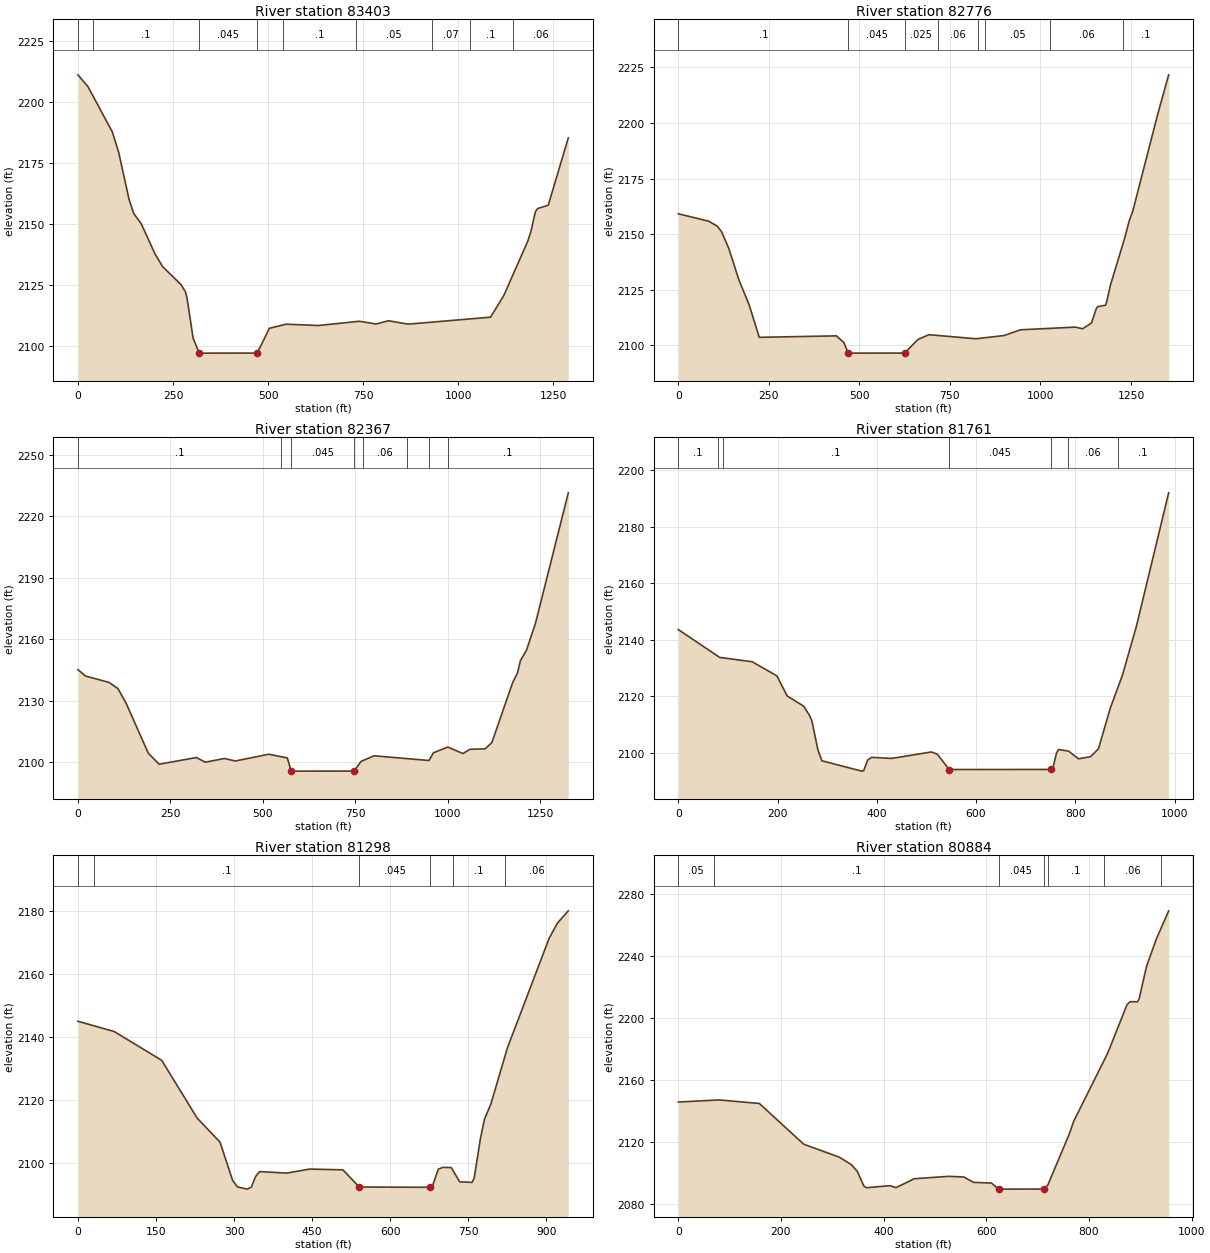
Type RM Length L Ch R = 1 ,83403   ,649.8,627,604.8
XS GIS Cut Line= 3
2316587.71450217702807.3079687462316666.44337465701716.913084862
2316819.96467599701594.883332514
#Sta/Elev= 30
       0 2210.98    26.2 2206.19    90.4 2187.65   107.2 2179.23   134.5 2159.97
   146.5 2154.31   166.6    2150   202.7 2137.69   222.7  2132.5   270.8  2125.2
   282.9 2122.12   286.9 2119.56   302.9 2103.18     319 2097.12   471.4 2097.14
   503.4 2107.28   547.6 2108.96   631.8 2108.42   740.1 2110.15   784.2 2109.03
   816.2 2110.36   868.4 2108.98  1084.9 2111.83  1119.9 2120.74  1182.8 2142.95
  1191.1 2146.97  1202.7 2154.93  1208.5 2156.26  1236.6 2157.65  1289.3 2185.19
#Mann= 9 ,-1,0
       0     .06       0      40      .1       0     319    .045       0
   471.4     .06       0     540      .1       0     730     .05       0
     930     .07       0    1030      .1       0 1143.23     .06       0
Bank Sta=319,471.4
XS Rating Curve= 0 ,0
Exp/Cntr(USF)=0,0
Exp/Cntr=0.3,0.1

Type RM Length L Ch R = 1 ,82776   ,433.4,408.5,386.1
XS GIS Cut Line= 4
2317300.21079814702980.5114882082317308.08368539702764.007088881
2317107.32506056701854.6886117062317189.99037666701665.739317748
#Sta/Elev= 30
       0 2159.14    84.3 2155.77   107.4 2153.59   119.4 2151.11   139.4 2143.58
   167.4 2129.38   195.5 2118.22   223.6 2103.52   436.6 2104.18   457.2 2101.18
   469.4 2096.41   625.1 2096.44   661.9 2102.57   692.1 2104.71   821.7 2102.87
   899.5 2104.33   944.6  2106.9  1096.2 2108.12  1116.6 2107.38  1141.2    2110
  1153.9 2116.29  1158.2 2117.31    1180 2117.99  1183.1 2119.57  1193.2 2126.96
  1232.5 2148.09  1245.6 2156.22  1254.3 2159.87  1324.2 2204.15  1354.1 2221.67
#Mann= 8 ,-1,0
       0      .1       0   469.4    .045       0   625.1    .025       0
  716.65     .06       0  826.65      .1       0  846.65     .05       0
 1026.65     .06       0 1227.86      .1       0
Bank Sta=469.4,625.1
XS Rating Curve= 0 ,0
Exp/Cntr(USF)=0,0
Exp/Cntr=0.3,0.1

Type RM Length L Ch R = 1 ,82367   ,560.6,606.3,643.8
XS GIS Cut Line= 3
2317933.97822162702846.6724049872317382.87611425701874.370829827
2317418.30410686701669.675761372
#Sta/Elev= 30
       0 2145.25    20.1 2142.13    84.5 2138.95   108.1 2135.97   130.5 2128.72
   190.2 2104.47   219.6 2099.09     320 2102.36   344.4 2100.08   395.6 2101.89
   425.5 2100.67     516 2103.97   565.9 2102.16   576.4 2095.73   746.6 2095.75
     765 2100.44   800.6 2103.21   948.9 2100.91   960.9 2104.68   999.5 2107.46
  1040.8  2104.3  1059.2 2106.36  1100.6 2106.61  1118.8 2109.66  1175.1 2138.95
  1187.8 2143.49    1196 2149.61  1212.2 2154.63  1236.6 2167.79  1325.4 2231.41
#Mann= 8 ,-1,0
       0      .1       0     550    .025       0   576.4    .045       0
   746.6    .025       0     770     .06       0     890      .1       0
     950     .06       0    1000      .1       0
Bank Sta=576.4,746.6
XS Rating Curve= 0 ,0
Exp/Cntr(USF)=0,0
Exp/Cntr=0.3,0.1

Type RM Length L Ch R = 1 ,81761   ,461.2,463,467.4
XS GIS Cut Line= 3
2318277.17212783702749.0422569862318205.44599165702483.530613864
 2318158.3555082  701772.0232956
#Sta/Elev= 30
       0 2143.65    83.5 2133.79     149 2132.25   198.7 2127.26   219.5 2120.13
   252.6 2116.55   264.6  2113.2   269.2 2111.32   281.4 2101.04   289.4 2097.22
   369.6 2093.55   373.6 2093.71   381.6 2097.48   389.6 2098.43   429.7 2098.04
   509.9 2100.33   521.9 2099.55     546 2094.12   750.4 2094.14   754.4 2094.27
   762.4 2100.14   766.5  2101.2   786.5 2100.62   806.5 2097.91   830.6 2098.65
   846.6 2101.42   870.7 2115.95   894.7 2127.35   922.8  2144.6   988.1 2192.03
#Mann= 7 ,-1,0
       0      .1       0      80     .05       0      90      .1       0
     546    .045       0   750.4    .025       0  785.03     .06       0
  885.03      .1       0
Bank Sta=546,750.4
XS Rating Curve= 0 ,0
Exp/Cntr(USF)=0,0
Exp/Cntr=0.3,0.1

Type RM Length L Ch R = 1 ,81298   ,389.4,413.9,436.6
XS GIS Cut Line= 2
2318658.28384846 702694.047309632318634.66518672701752.341077479
#Sta/Elev= 30
       0  2144.9    69.3 2141.67   160.9 2132.53   228.9 2114.24     273 2106.58
     297 2094.52   306.5 2092.39     325  2091.7     333 2092.29     341 2095.63
     349 2097.26     401 2096.78     445 2098.05     509 2097.81   540.5 2092.37
   677.1 2092.28   681.1 2092.71   692.3 2098.03   701.1  2098.6   717.1 2098.53
   733.4 2094.01   757.1 2093.84   761.1 2095.09   773.1 2107.66   781.1 2113.92
   793.1  2118.6   825.1  2136.5   905.2 2171.21   921.2 2176.04     942  2179.9
#Mann= 6 ,-1,0
       0     .05       0      30      .1       0   540.5    .045       0
   677.1    .025       0     720      .1       0     820     .06       0
Bank Sta=540.5,677.1
XS Rating Curve= 0 ,0
Exp/Cntr(USF)=0,0
Exp/Cntr=0.3,0.1

Type RM Length L Ch R = 1 ,80884   ,324.7,347.6,366.7
XS GIS Cut Line= 2
2318760.51611931702727.5358962812319173.95796323701866.497942579
#Sta/Elev= 30
       0 2145.83    79.5 2147.17   157.9  2144.9   244.3 2118.61   313.3 2110.31
   337.3 2105.38   348.7 2101.11   361.2 2091.76   366.5 2090.52   412.2 2091.86
   424.3  2090.6   459.6 2096.32   526.4 2097.87   556.1 2097.46     575 2093.99
   610.1 2093.54   623.8 2089.64   628.3 2089.62   712.6 2089.67     720 2092.38
   761.4 2125.04   770.3 2133.45   836.8 2177.62   873.9 2208.55   879.9 2210.58
   894.5 2210.52   897.8 2212.56   912.2 2233.53   930.8 2250.71   955.2 2269.22
#Mann= 7 ,-1,0
       0     .05       0      70      .1       0   623.8    .045       0
   712.6    .025       0     720      .1       0     830     .06       0
     940      .1       0
Bank Sta=623.8,712.6
XS Rating Curve= 0 ,0
Exp/Cntr(USF)=0,0
Exp/Cntr=0.3,0.1