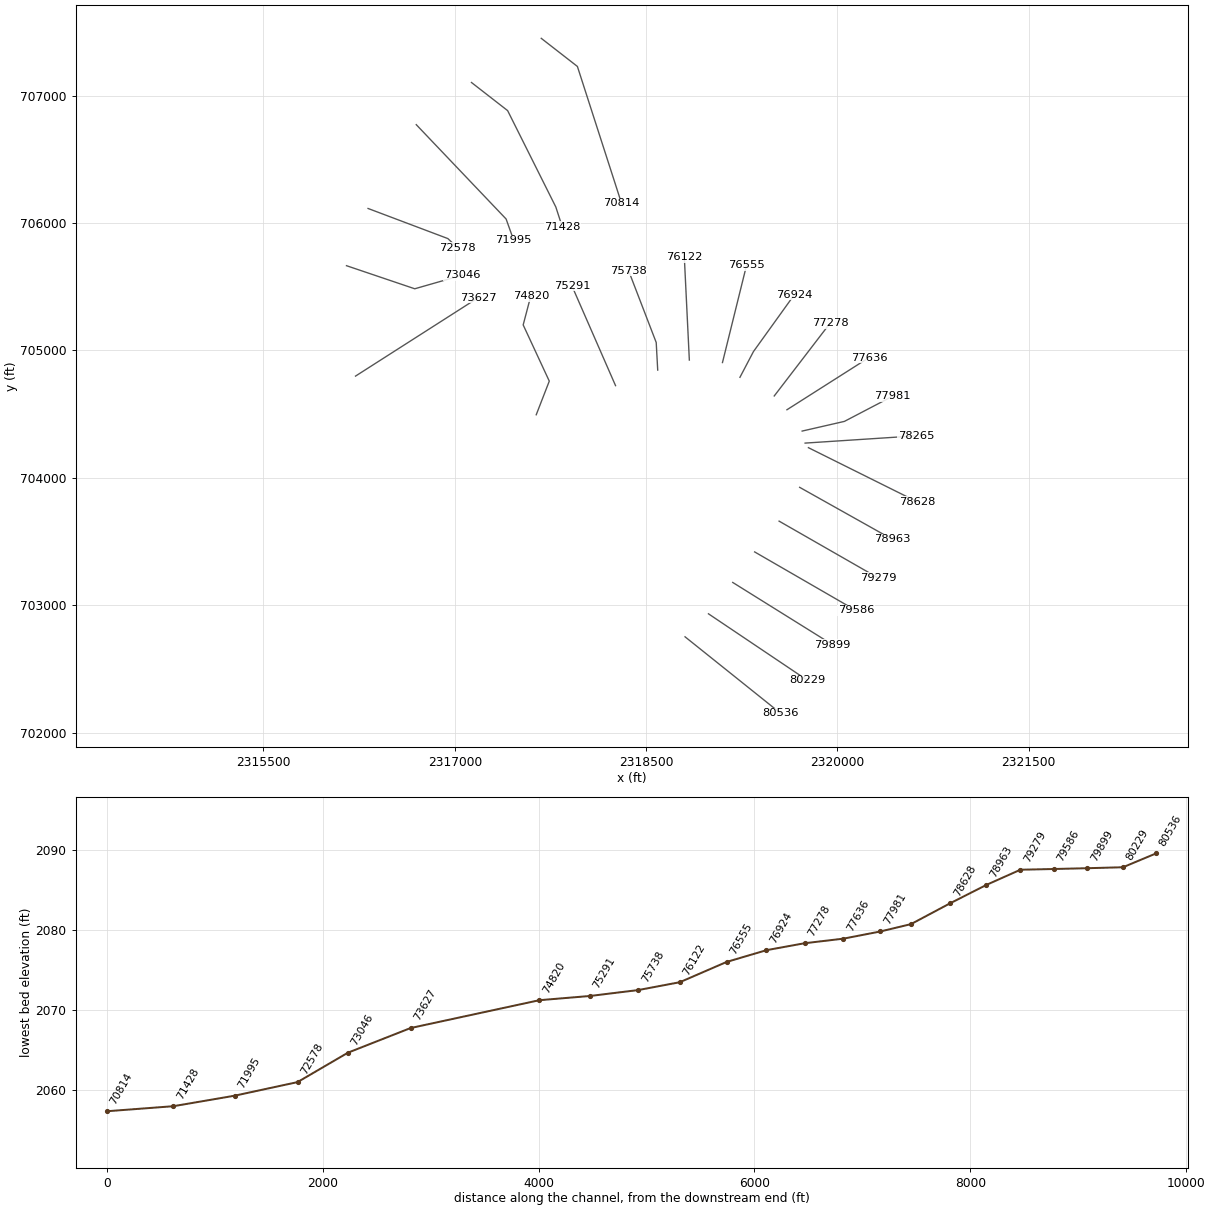
HEC-RAS study SHAVERSFK.prj: SHAVERSFK

--- SHAVERSFK.g01 (geometry) --- (continued)

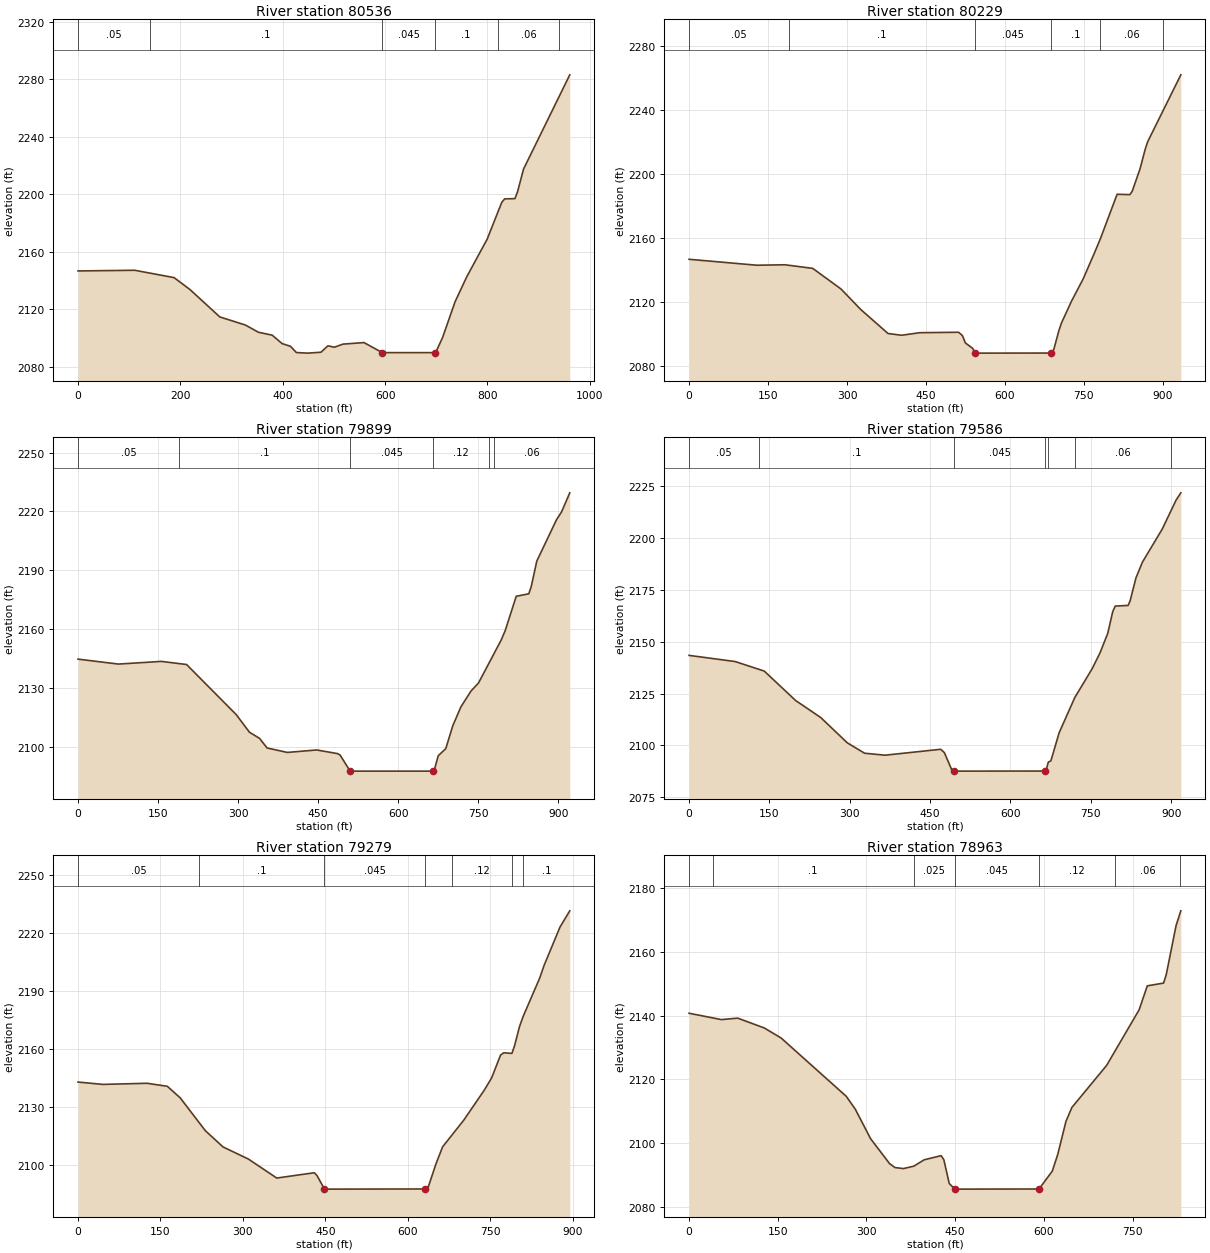
Type RM Length L Ch R = 1 ,80536   ,302,307,313.7
XS GIS Cut Line= 2
2318805.64114176702754.3676907392319555.79299477 702153.85832714
#Sta/Elev= 30
       0 2146.67   110.8 2147.15   187.7 2142.05   218.9 2133.72   277.1 2114.73
   327.1 2109.09   352.7 2104.06   379.5 2102.04   398.7 2096.22   415.3 2094.29
   426.7 2089.96     449 2089.57   474.6 2090.18   488.3 2094.64   501.1 2093.69
   517.7 2095.83   558.8  2096.9   594.6 2089.91     697 2089.92   700.1 2090.93
   712.4 2100.43   736.8 2125.29   759.6 2142.61   799.5 2168.78   827.9 2194.25
   833.6 2196.75   853.8 2196.93   858.9 2201.73   870.6  2217.5   960.9 2282.96
#Mann= 6 ,-1,0
       0     .05       0     140      .1       0   594.6    .045       0
     697      .1       0     820     .06       0     940      .1       0
Bank Sta=594.6,697
XS Rating Curve= 0 ,0
Exp/Cntr(USF)=0,0
Exp/Cntr=0.3,0.1

Type RM Length L Ch R = 1 ,80229   ,328,330.3,333
XS GIS Cut Line= 2
2318989.32263365 702934.778418232319764.42450685702413.663606333
#Sta/Elev= 30
       0 2146.57   128.8 2142.85   182.1 2143.13   234.8 2140.89   288.5 2128.01
     326 2115.17   377.9 2100.12   403.5 2099.02   438.4 2100.63   511.9  2100.9
   519.1 2098.86   524.9 2094.19   538.5 2090.88   543.3    2088   547.7 2087.84
   687.9 2087.89   692.7 2090.07   702.3 2101.79   707.2 2106.59   726.4 2120.38
   748.5 2134.28     770 2150.58   781.4 2159.58     813 2187.26   837.3 2187.04
   841.7 2189.14   856.6 2203.25   866.2 2215.29     871  2220.1     934 2262.01
#Mann= 6 ,-1,0
       0     .05       0     190      .1       0   543.3    .045       0
   687.9      .1       0     780     .06       0     900      .1       0
Bank Sta=543.3,687.9
XS Rating Curve= 0 ,0
Exp/Cntr(USF)=0,0
Exp/Cntr=0.3,0.1

Type RM Length L Ch R = 1 ,79899   ,310.8,313.3,317
XS GIS Cut Line= 2
2319179.60328605703180.7773288932319961.24668805702693.151103646
#Sta/Elev= 30
       0 2144.78    75.6 2142.25   156.3 2143.62   203.4 2142.03   296.3 2116.55
   321.3 2107.51   340.1 2104.42   354.3  2099.5   392.2 2097.25   447.2  2098.5
   486.3 2096.65     491 2095.92   509.8 2087.72   665.4 2087.72   667.9  2088.7
   674.9 2095.57     689 2099.18   702.1 2110.81   717.2 2120.37   736.1 2128.46
   750.3 2132.62   792.7 2154.44   800.3 2159.27     821  2176.8   844.6 2178.05
   849.3 2181.93   859.5 2194.69   896.4 2215.77   905.9 2219.76   921.3 2229.49
#Mann= 6 ,-1,0
       0     .05       0     190      .1       0   509.8    .045       0
   665.4     .12       0     770      .1       0     780     .06       0
Bank Sta=509.8,665.4
XS Rating Curve= 0 ,0
Exp/Cntr(USF)=0,0
Exp/Cntr=0.3,0.1

Type RM Length L Ch R = 1 ,79586   ,306.6,307.2,307.5
XS GIS Cut Line= 2
2319351.47544707703420.2347107462320146.25953839702960.829270087
#Sta/Elev= 30
       0 2143.48      86 2140.51   140.4  2135.9   198.9 2121.71   245.8 2113.49
   295.5 2101.26   327.7 2096.26   365.8 2095.31   469.7 2098.16   476.7 2096.51
   490.5 2088.19   495.2 2087.62   664.4 2087.66   666.1 2087.75   670.7 2091.99
   675.4 2092.53   690.8 2106.11   720.1 2123.15   752.3 2136.97   766.9 2144.54
   781.6 2154.12   790.9 2164.61   795.5 2167.26   819.6  2167.6   823.2 2169.65
   834.2 2180.84   846.3 2188.47   883.3 2204.44   909.3  2218.5     918 2221.93
#Mann= 7 ,-1,0
       0     .05       0     130      .1       0   495.2    .045       0
   664.4    .025       0     670     .12       0     720     .06       0
     900      .1       0
Bank Sta=495.2,664.4
XS Rating Curve= 0 ,0
Exp/Cntr(USF)=0,0
Exp/Cntr=0.3,0.1

Type RM Length L Ch R = 1 ,79279   ,314.5,315.2,317.6
XS GIS Cut Line= 2
2319543.08745791703661.6891302562320319.46305785703216.698105656
#Sta/Elev= 30
       0 2142.91    45.1 2141.69   125.7 2142.27   162.6 2140.71     186 2134.73
   231.8 2117.73     264 2109.34   310.2 2103.06   361.6 2093.26     430    2096
   434.9 2094.55   448.5 2087.57   451.5 2087.53   631.3 2087.61   637.5  2088.7
   651.3 2100.52   663.5  2109.4     702 2123.21   739.7 2138.87   752.8 2145.12
     769 2156.87   774.9 2158.04   789.6 2157.72   794.3 2161.57   803.5 2171.64
     810 2176.79   840.4 2196.84   848.1  2203.2   877.2  2223.1   894.9 2231.46
#Mann= 7 ,-1,0
       0     .05       0     220      .1       0   448.5    .045       0
   631.3    .025       0     680     .12       0     790     .06       0
     810      .1       0
Bank Sta=448.5,631.3
XS Rating Curve= 0 ,0
Exp/Cntr(USF)=0,0
Exp/Cntr=0.3,0.1

Type RM Length L Ch R = 1 ,78963   ,331.3,335,338.5
XS GIS Cut Line= 2
2319704.42401481703926.7622115112320429.68347932703519.804264714
#Sta/Elev= 30
       0 2140.75    54.8 2138.76    82.3 2139.22   127.3 2136.13   155.7 2132.99
   265.7 2114.74   281.2 2110.65     307 2101.43   339.1 2093.62   348.3 2092.39
   362.4 2092.07     380 2092.82   397.6 2094.82   426.3 2096.12   430.9 2094.82
     440 2087.38   449.2  2085.7   452.8 2085.63   591.8 2085.67   614.3  2091.3
   623.5 2096.53   637.3 2106.83   647.4 2111.23   706.1  2124.4   761.1 2141.83
   774.9 2149.34   802.4  2150.2     807 2152.89   823.6 2168.25   831.6 2172.85
#Mann= 7 ,-1,0
       0     .05       0      40      .1       0     380    .025       0
   449.2    .045       0   591.8     .12       0     720     .06       0
     830      .1       0
Bank Sta=449.2,591.8
XS Rating Curve= 0 ,0
Exp/Cntr(USF)=0,0
Exp/Cntr=0.3,0.1

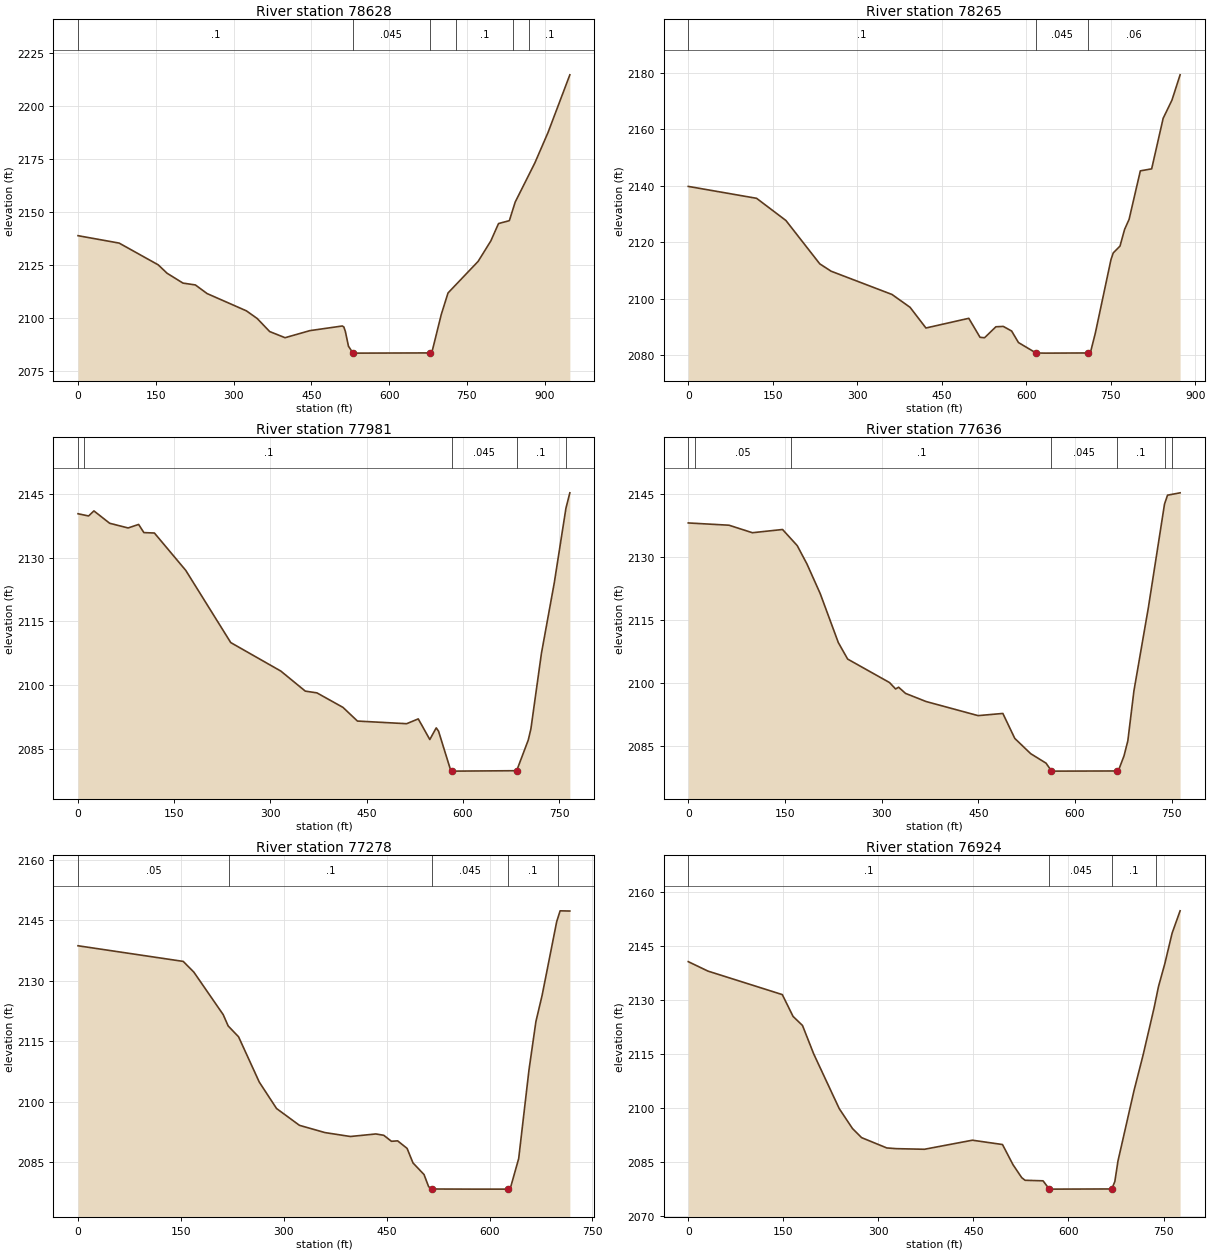
Type RM Length L Ch R = 1 ,78628   ,335.5,363.8,394.9
XS GIS Cut Line= 2
 2319773.2253307704237.7412578182320622.56921691703815.037536524
#Sta/Elev= 30
       0 2138.77    79.3 2135.28   154.8    2125   171.8 2121.04   202.5 2116.39
   226.4 2115.52     249 2111.45   324.8  2103.3   345.7 2099.67   369.7 2093.52
   399.4 2090.62   447.1 2093.95   509.8 2096.15   512.8 2095.67   515.7 2093.56
   521.7 2086.59   530.1 2083.47   539.5 2083.34     678 2083.44   683.6 2084.71
   700.7  2101.6   713.7 2111.73   771.8 2126.65   796.2 2136.26   811.1 2144.49
     832 2145.86   843.3 2154.65   881.1 2173.06   906.6 2187.48   948.7 2214.69
#Mann= 6 ,-1,0
       0      .1       0   530.1    .045       0     678     .12       0
     730      .1       0     840     .06       0     870      .1       0
Bank Sta=530.1,678
XS Rating Curve= 0 ,0
Exp/Cntr(USF)=0,0
Exp/Cntr=0.3,0.1

Type RM Length L Ch R = 1 ,78265   ,262.7,283.8,302.4
XS GIS Cut Line= 2
2319747.15714417704273.7563999292320618.63277328704330.711651285
#Sta/Elev= 30
       0 2139.72   121.3 2135.51   173.4 2127.66   233.5 2112.32   253.6 2109.72
   361.8 2101.48   393.9 2096.93     422 2089.62   498.1 2093.05   518.1 2086.32
   526.1 2086.18   546.2 2090.05   559.3 2090.19   574.2 2088.55   586.3 2084.47
   617.5 2080.78   634.4 2080.73   710.5 2080.79   714.5 2081.29   722.6 2087.64
   750.6 2113.86   754.6 2116.19   766.6 2118.61   774.7 2124.48   782.7 2128.06
   802.7 2145.22   822.8 2145.93   843.2 2163.81   858.8 2170.23   873.3  2179.2
#Mann= 3 ,-1,0
       0      .1       0   617.5    .045       0   710.5     .06       0
Bank Sta=617.5,710.5
XS Rating Curve= 0 ,0
Exp/Cntr(USF)=0,0
Exp/Cntr=0.3,0.1

Type RM Length L Ch R = 1 ,77981   ,339.8,344.3,348.3
XS GIS Cut Line= 3
2319724.04860124704368.0790498692320055.49937468704444.034945133
2320433.61992295704641.690697591
#Sta/Elev= 30
       0 2140.32    16.5  2139.8    24.8 2140.99    49.4 2138.08    78.1 2136.98
    94.5 2137.81   102.7 2135.89   119.1 2135.79     168    2127   238.1 2110.03
   316.1 2103.34   354.3 2098.62   372.4 2098.21     413  2094.8   435.6 2091.58
   512.3 2090.96   530.4 2092.09   548.4 2087.24   558.4 2089.98     562 2089.21
     580 2080.46  583.192079.927   584.5 2079.81   683.8 2079.91   701.9 2087.13
     706 2089.76   722.4  2107.5   742.5 2124.15   760.6 2141.62   766.7 2145.24
#Mann= 5 ,-1,0
       0     .05       0      10      .1       0  583.19    .045       0
   683.8      .1       0  760.04     .06       0
Bank Sta=583.19,683.8
XS Rating Curve= 0 ,0
Exp/Cntr(USF)=0,0
Exp/Cntr=0.3,0.1

Type RM Length L Ch R = 1 ,77636   ,339.2,358.7,374.9
XS GIS Cut Line= 2
2319604.73919746704535.2338246662320248.60707261704944.796856649
#Sta/Elev= 30
       0 2138.07    63.2 2137.53    99.5 2135.74   146.3 2136.51   169.1 2132.66
   184.2 2128.28   204.8  2121.2   232.8 2109.56   247.3 2105.62   312.2 2100.03
   321.7  2098.5   326.4 2098.91   337.1 2097.44     369  2095.5   449.7 2092.14
   488.1 2092.66   506.6 2086.71   531.3 2083.07   555.1 2080.81   563.5 2078.96
   568.2 2078.91   664.5 2078.95   667.8  2079.2   676.1 2082.56     682 2086.13
   691.5 2098.09   713.8 2117.83   738.9 2142.56   743.6 2144.69   763.1 2145.25
#Mann= 7 ,-1,0
       0      .1       0      10     .05       0     160      .1       0
   563.5    .045       0   664.5      .1       0     740     .06       0
     750      .1       0
Bank Sta=563.5,664.5
XS Rating Curve= 0 ,0
Exp/Cntr(USF)=0,0
Exp/Cntr=0.3,0.1

Type RM Length L Ch R = 1 ,77278   ,351.9,353.5,355.1
XS GIS Cut Line= 2
 2319505.1120118704643.4572084852319941.56446993 705212.47502309
#Sta/Elev= 30
       0 2138.73   153.4 2134.85   168.9 2132.19   211.7 2121.64   218.9 2118.84
   234.1 2116.14   264.3  2104.9   289.5 2098.34   322.9 2094.17   360.1 2092.37
   397.1  2091.4   434.2 2092.03   445.8  2091.7     457 2090.21     466 2090.32
   479.8 2088.45   488.4 2084.84   504.5 2081.96   511.2 2078.95   516.4 2078.37
   576.8 2078.34   627.3 2078.34   631.1 2079.02   642.5 2085.92   657.5 2107.89
   667.6 2119.91   676.7 2126.46   697.9  2144.7   702.9  2147.4   717.1 2147.35
#Mann= 5 ,-1,0
       0     .05       0     220      .1       0   516.4    .045       0
   627.3      .1       0     700     .06       0
Bank Sta=516.4,627.3
XS Rating Curve= 0 ,0
Exp/Cntr(USF)=0,0
Exp/Cntr=0.3,0.1

Type RM Length L Ch R = 1 ,76924   ,349.6,369,390.2
XS GIS Cut Line= 3
 2319236.2177503704789.7713017962319342.17033396704991.687563492
2319662.07697262705436.852309666
#Sta/Elev= 30
       0 2140.71      31 2138.09   148.4 2131.55   165.4 2125.49   180.3 2122.96
     198 2115.05   238.3 2099.84   259.2 2094.31   273.5 2091.79   313.3 2088.92
   328.4 2088.72   372.7 2088.55   448.4 2091.07   495.9 2089.87   512.5 2084.26
   526.2 2080.67   531.5 2079.93   559.9 2079.78   569.7  2077.5   574.2 2077.47
   668.3 2077.52   673.2 2079.57   678.1 2085.25   703.4 2104.82   717.8 2114.76
     735 2127.75   742.1  2133.8   752.2 2140.23   763.6 2148.64   776.2 2154.84
#Mann= 4 ,-1,0
       0      .1       0   569.7    .045       0   668.3      .1       0
  738.03     .06       0
Bank Sta=569.7,668.3
XS Rating Curve= 0 ,0
Exp/Cntr(USF)=0,0
Exp/Cntr=0.3,0.1

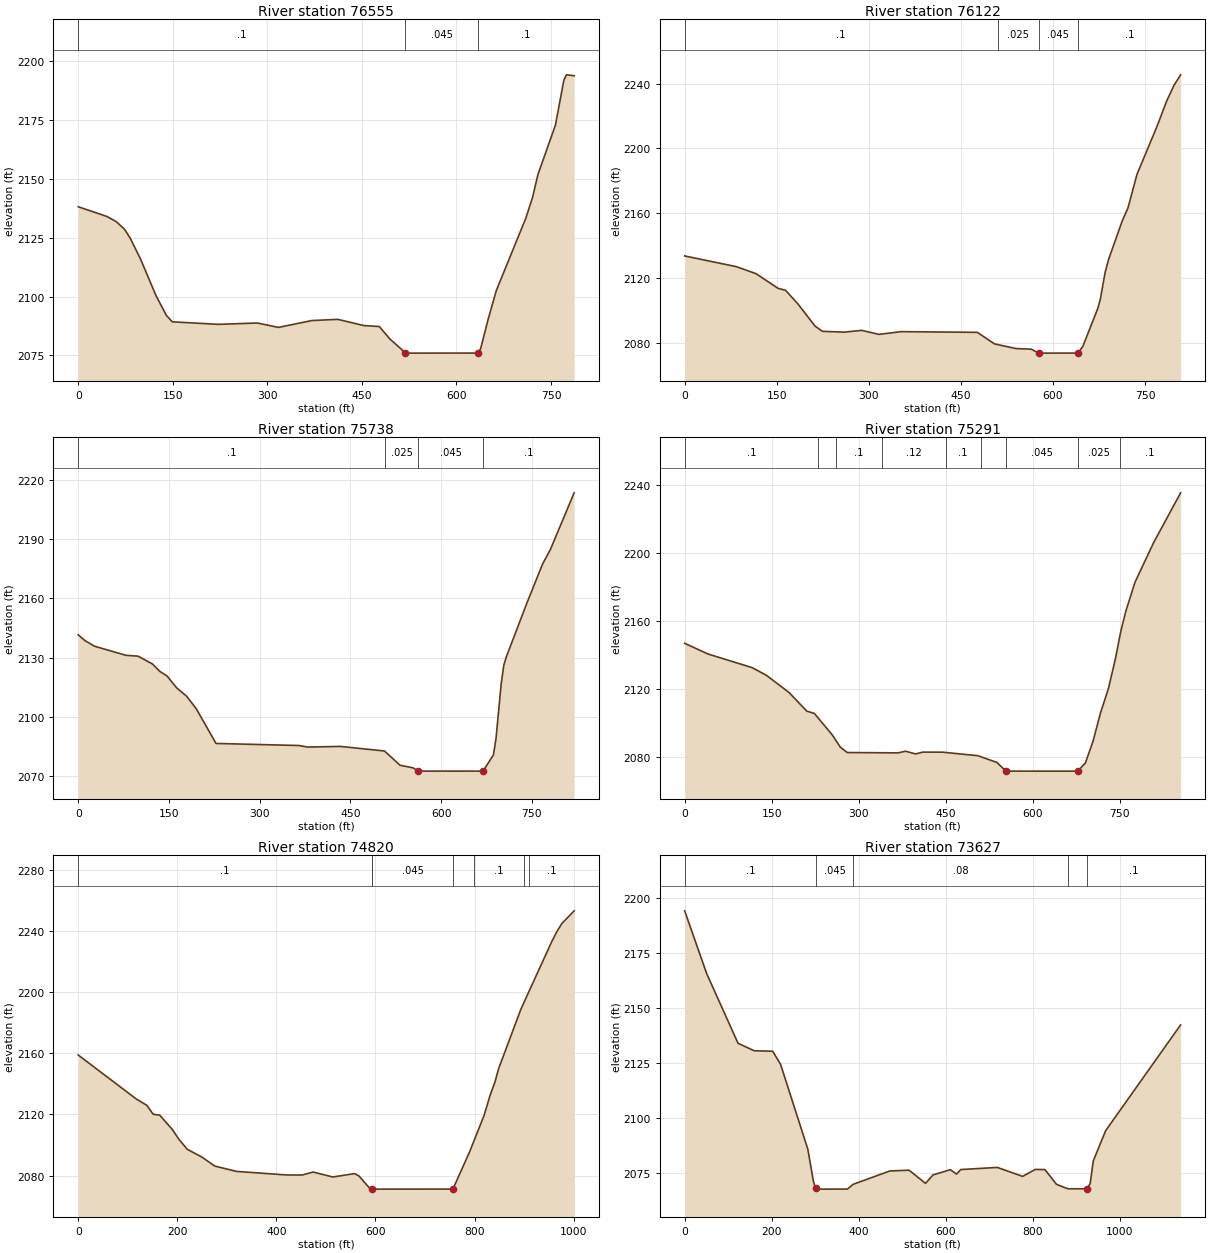
Type RM Length L Ch R = 1 ,76555   ,424.4,432.9,447.1
XS GIS Cut Line= 2
2319099.16553437704905.4324204082319288.11482832705669.102483489
#Sta/Elev= 30
       0 2138.19    45.1 2134.11    60.1 2131.92    73.3 2128.68    82.2 2124.99
    98.6 2116.12   123.4 2100.44   139.8 2092.05   149.3  2089.3   222.3 2088.23
   284.1  2088.8   317.7 2086.93   370.6 2089.84   411.8 2090.35     453 2087.72
   477.7 2087.29   494.2 2082.06   518.9 2076.16   523.1    2076   634.3 2076.03
   638.4 2077.92   649.8 2089.91   663.2 2102.57   710.1 2133.38   720.7 2142.14
   729.1 2151.74   757.1 2172.96   770.3 2191.88   774.4 2194.24   786.7 2193.86
#Mann= 3 ,-1,0
       0      .1       0   518.9    .045       0   634.3      .1       0
Bank Sta=518.9,634.3
XS Rating Curve= 0 ,0
Exp/Cntr(USF)=0,0
Exp/Cntr=0.3,0.1

Type RM Length L Ch R = 1 ,76122   ,374.9,384.3,399.6
XS GIS Cut Line= 2
2318839.36025517704925.1146385292318799.99581893705732.085581476
#Sta/Elev= 30
       0 2133.51    84.2  2126.9   116.2 2122.57   152.2 2113.49   164.3  2112.3
   184.3 2103.96   212.3 2090.21   224.3 2086.94   260.4 2086.45   288.4 2087.54
   316.4 2085.06   352.5 2086.74   476.7 2086.31   504.7 2079.17   539.8 2076.29
   564.7 2075.91   576.7 2073.47   640.9  2073.5   648.8  2077.8   672.9 2101.02
   676.9 2106.34   684.9 2123.28   690.4 2131.17   712.4 2154.77   722.2 2163.26
   736.9    2184     769 2213.12     785 2229.09   797.3 2239.07   807.9 2245.42
#Mann= 4 ,-1,0
       0      .1       0     510    .025       0   576.7    .045       0
   640.9      .1       0
Bank Sta=576.7,640.9
XS Rating Curve= 0 ,0
Exp/Cntr(USF)=0,0
Exp/Cntr=0.3,0.1

Type RM Length L Ch R = 1 ,75738   ,444.3,447,450.3
XS GIS Cut Line= 3
2318591.36430685704846.3857660462318579.55497598705062.890165373
2318363.05057665705625.801603624
#Sta/Elev= 30
       0  2141.6    10.8 2138.71    26.8 2135.81    78.9 2131.19    98.9 2130.76
     123 2126.74   134.8 2123.07     147 2120.66     163 2114.62   179.1 2110.49
   195.1 2104.15   227.8 2086.52     365 2085.47   379.1  2084.7   433.6 2085.01
   506.4 2082.69   532.1 2075.46   553.6 2074.16   562.1  2072.5   663.8 2072.49
   669.3  2072.5   686.4 2080.69   690.7 2088.97   699.3 2116.74   703.6 2126.16
   707.8 2130.42   742.1 2157.92   767.8 2177.52   780.7 2184.88   819.9 2213.54
#Mann= 4 ,-1,0
       0      .1       0  506.83    .025       0   562.1    .045       0
   669.3      .1       0
Bank Sta=562.1,669.3
XS Rating Curve= 0 ,0
Exp/Cntr(USF)=0,0
Exp/Cntr=0.3,0.1

Type RM Length L Ch R = 1 ,75291   ,469.1,470.8,474.2
XS GIS Cut Line= 2
2318260.70304243704724.3560136982317918.23244713  705507.7082949
#Sta/Elev= 30
       0 2147.03    40.2 2140.73   116.5 2132.68   141.1 2128.12   179.9 2118.06
   210.4  2107.1   223.5 2105.75   254.1 2093.22   268.3 2085.87   280.3  2082.7
   367.6  2082.5   380.8 2083.47   398.2 2081.88   410.7 2082.95   444.5 2082.91
   505.3 2080.85   537.9 2076.91   553.9 2071.79   555.3 2071.75   677.6 2071.75
   690.7 2076.54   703.8 2089.21   716.8 2106.01   730.3 2120.21   742.2 2137.41
   751.8 2154.09   760.2 2165.62   776.2 2182.93   808.5 2206.39   854.9 2235.64
#Mann= 9 ,-1,0
       0      .1       0     230     .12       0     260      .1       0
     340     .12       0     450      .1       0     510    .025       0
   553.9    .045       0   677.6    .025       0     750      .1       0
Bank Sta=553.9,677.6
XS Rating Curve= 0 ,0
Exp/Cntr(USF)=0,0
Exp/Cntr=0.3,0.1

Type RM Length L Ch R = 1 ,74820   ,1267.9,1193.5,568.6
XS GIS Cut Line= 4
2317638.74494981704496.0422834982317741.09248404704759.784006315
2317536.39741559705200.6656922182317595.44406995705425.042978793
#Sta/Elev= 30
       0 2158.85   117.1 2130.13   138.5 2125.96   151.4 2120.12   164.3 2119.61
     190 2110.18   202.9 2103.91     220 2097.28   250.1 2092.04   275.8 2086.27
   319.7 2082.79   421.2 2080.47     452 2080.42   474.1 2082.38   513.8 2079.16
   557.9 2081.34   566.7  2079.8   588.7 2071.64   593.1 2071.22   756.3 2071.24
   790.2 2095.73   819.2 2119.35   831.4 2132.55   841.3 2141.35   848.1  2149.5
   893.5 2188.78   955.6 2232.81   966.5 2239.68   976.3  2244.8    1001 2253.04
#Mann= 7 ,-1,0
       0      .1       0   592.9    .025       0   593.1    .045       0
   756.3    .025       0  798.99      .1       0  898.99    .025       0
  908.99      .1       0
Bank Sta=593.1,756.3
XS Rating Curve= 0 ,0
Exp/Cntr(USF)=0,0
Exp/Cntr=0.3,0.1

Type RM Length L Ch R = 1 ,73627   ,619.7,580.8,453.2
XS GIS Cut Line= 2
2316221.62524513704799.1484425562317182.11748941705413.233647921
#Sta/Elev= 30
       0 2194.01    50.5 2165.56   122.6 2133.93   159.7 2130.53   202.4  2130.3
   220.5 2124.33   283.1 2085.86   295.8 2071.39   300.8 2068.07   302.1 2067.74
     374 2067.76   387.6 2069.95   471.6 2075.98   515.8 2076.33   553.6 2070.34
   570.9 2074.21   610.7 2076.55     625 2074.57   634.5 2076.62   718.6 2077.59
   776.9 2073.52   805.8 2076.68     828 2076.61   854.8 2069.89   880.8 2067.91
   924.6 2067.88     932 2070.22   939.4 2080.61   967.7 2094.27    1140 2142.26
#Mann= 5 ,-1,0
       0      .1       0   302.1    .045       0   387.6     .08       0
   880.8    .045       0   924.6      .1       0
Bank Sta=300.8,924.6
XS Rating Curve= 0 ,0
Exp/Cntr(USF)=0,0
Exp/Cntr=0.3,0.1

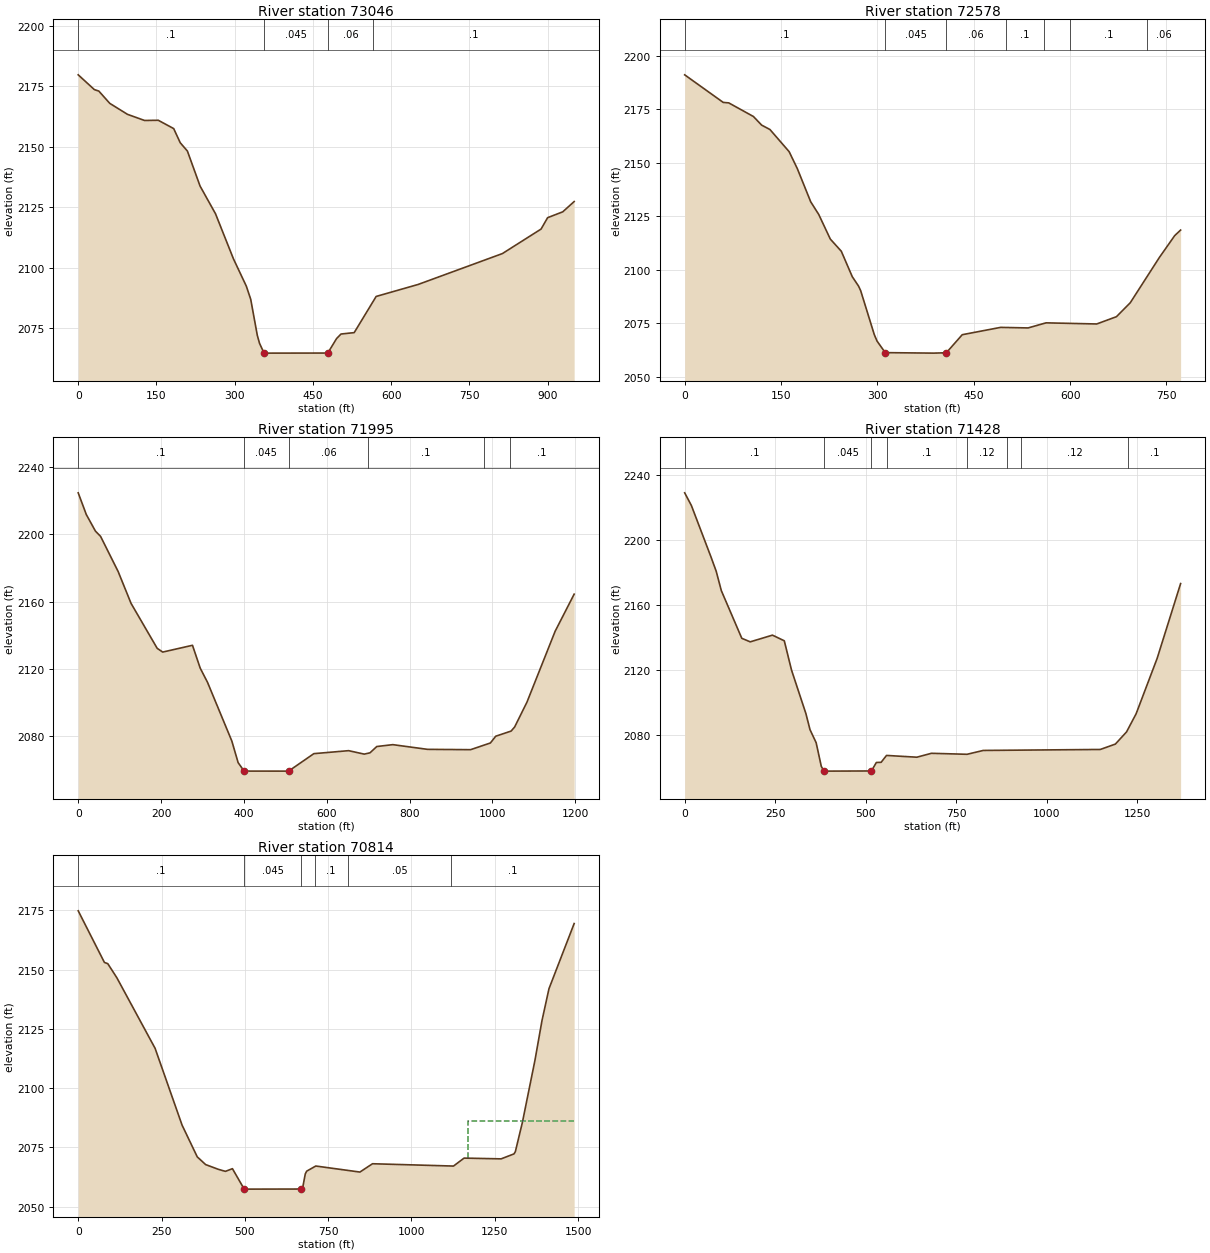
Type RM Length L Ch R = 1 ,73046   ,469.4,467.4,468.7
XS GIS Cut Line= 3
2316150.76925989705665.1660398652316686.12559277705484.089633155
2317057.10513111705590.431242698
#Sta/Elev= 30
       0 2179.75      31 2173.63    39.5 2173.03    60.6 2167.94    94.4 2163.42
   127.3 2160.87   153.5 2160.96   183.1 2157.52   195.7 2151.65   209.4 2148.23
   233.7 2133.75   263.3  2122.3   297.7 2103.66   322.4 2092.36   330.8 2086.96
   343.5 2071.99   347.7 2068.73   356.2 2064.76   360.4 2064.66   478.6 2064.69
   495.5 2070.68     504 2072.56   529.3 2073.14   571.4  2088.1   651.8 2093.05
   813.5 2105.83   887.7 2115.97   900.2 2120.67   929.3  2123.1   951.1 2127.34
#Mann= 4 ,-1,0
       0      .1       0   356.2    .045       0   478.6     .06       0
  565.15      .1       0
Bank Sta=356.2,478.6
XS Rating Curve= 0 ,0
Exp/Cntr(USF)=0,0
Exp/Cntr=0.3,0.1

Type RM Length L Ch R = 1 ,72578   ,603.1,583.7,558.5
XS GIS Cut Line= 3
2316320.03633573706113.9206130162316945.93087197705877.733995568
2317020.72330083705806.878010334
#Sta/Elev= 30
       0 2191.01      60 2178.12    68.6  2177.9     107 2171.54   119.9 2167.49
   132.7 2165.47   162.6 2155.12   175.4 2147.15   196.2 2131.68   208.7 2125.76
   226.7 2114.27   243.8 2108.59   260.9 2096.69   270.7 2092.29     274 2090.13
   295.1 2069.68   299.4 2066.63   312.2 2061.21   387.3 2060.98   407.3 2061.15
   432.1 2069.59   491.8 2073.01   534.6 2072.75   562.5 2075.13   641.4  2074.6
   672.1    2078   693.6 2084.51   738.9 2105.66   762.8 2115.89     772 2118.48
#Mann= 7 ,-1,0
       0      .1       0   312.2    .045       0   407.3     .06       0
     500      .1       0     560     .06       0     600      .1       0
  718.98     .06       0
Bank Sta=312.2,407.3
XS Rating Curve= 0 ,0
Exp/Cntr(USF)=0,0
Exp/Cntr=0.3,0.1

Type RM Length L Ch R = 1 ,71995   ,589.4,567,552.4
XS GIS Cut Line= 3
2316697.93492365706771.3066982462317402.55833237706031.255296909
2317461.60498673705865.924664696
#Sta/Elev= 30
       0 2224.65    19.5 2211.77    41.6  2201.9      54 2198.77    96.5 2177.84
   127.6 2158.96   190.7 2132.24     204 2130.02   275.9 2134.05   294.5 2120.52
   312.2 2112.04   370.9 2077.17   386.1 2064.32   400.6  2059.3   507.9 2059.28
   568.9 2069.66   652.9 2071.44   690.6 2069.38   704.4 2070.15   720.9  2073.9
   759.6 2075.01   843.4 2072.22   947.4 2072.03   995.2 2076.01  1008.1 2080.03
  1045.3 2083.09  1053.8 2085.54  1083.5 2100.29  1151.5 2142.39  1197.4 2164.44
#Mann= 6 ,-1,0
       0      .1       0   400.6    .045       0   507.9     .06       0
     700      .1       0     980     .12       0 1041.85      .1       0
Bank Sta=400.6,507.9
XS Rating Curve= 0 ,0
Exp/Cntr(USF)=0,0
Exp/Cntr=0.3,0.1

Type RM Length L Ch R = 1 ,71428   ,626.5,613.9,605.3
XS GIS Cut Line= 4
 2317130.9437223707101.9679626732317414.36766324706881.527119722
2317792.26625116706125.7299438882317843.44001827705968.272198923
#Sta/Elev= 30
       0 2229.09    18.5 2221.31    72.5 2189.76      87 2180.92   101.2 2168.96
   157.7 2139.65     181 2137.46   242.4 2141.58   275.1 2138.11     295 2120.16
   334.9 2093.25   346.1 2083.47   363.1 2075.44   377.3 2060.88   384.5 2058.09
   386.3 2057.97   515.7 2058.07   529.4 2063.29   542.5 2063.38   557.4 2067.62
   641.2 2066.53   681.4 2068.93   779.8 2068.32   824.6 2070.69  1147.8 2071.29
  1189.5 2074.61  1220.3 2082.09  1246.7 2093.22  1304.8  2127.3  1369.6 2173.29
#Mann= 8 ,-1,0
       0      .1       0   384.5    .045       0   515.7     .06       0
  559.06      .1       0  779.06     .12       0  889.06      .1       0
  929.06     .12       0 1224.07      .1       0
Bank Sta=384.5,515.7
XS Rating Curve= 0 ,0
Exp/Cntr(USF)=0,0
Exp/Cntr=0.3,0.1

Type RM Length L Ch R = 1 ,70814   ,764.9,813.4,806.2
XS GIS Cut Line= 3
2317678.10938606707448.3750015972317961.53332699707227.934158645
2318307.94036592706153.285049257
#Sta/Elev= 30
       0 2174.77    78.6    2153    88.8 2152.46     116 2146.52   230.7 2116.76
   311.7 2084.34   357.2 2070.96   382.4 2067.69   420.8 2065.68   441.8 2064.84
   462.8 2065.97     498 2057.38   500.6 2057.34   668.7 2057.38     673  2057.5
   681.4 2063.76   685.6 2064.92   712.9 2067.09   845.3 2064.54   883.1 2068.05
  1126.1 2067.07  1157.9 2070.43  1269.1 2070.11  1307.6  2072.2  1311.8 2073.17
  1332.8 2085.45  1370.6 2111.71  1391.6 2128.39  1412.6 2141.88  1488.2  2169.4
#Mann= 6 ,-1,0
       0      .1       0     498    .045       0   668.7     .06       0
  709.06      .1       0  809.06     .05       0 1119.06      .1       0
#XS Ineff= 2 , 0
                         1168.67         2086.17
Permanent Ineff=
       F       F
Bank Sta=498,668.7
XS Rating Curve= 0 ,0
Exp/Cntr(USF)=0,0
Exp/Cntr=0.3,0.1