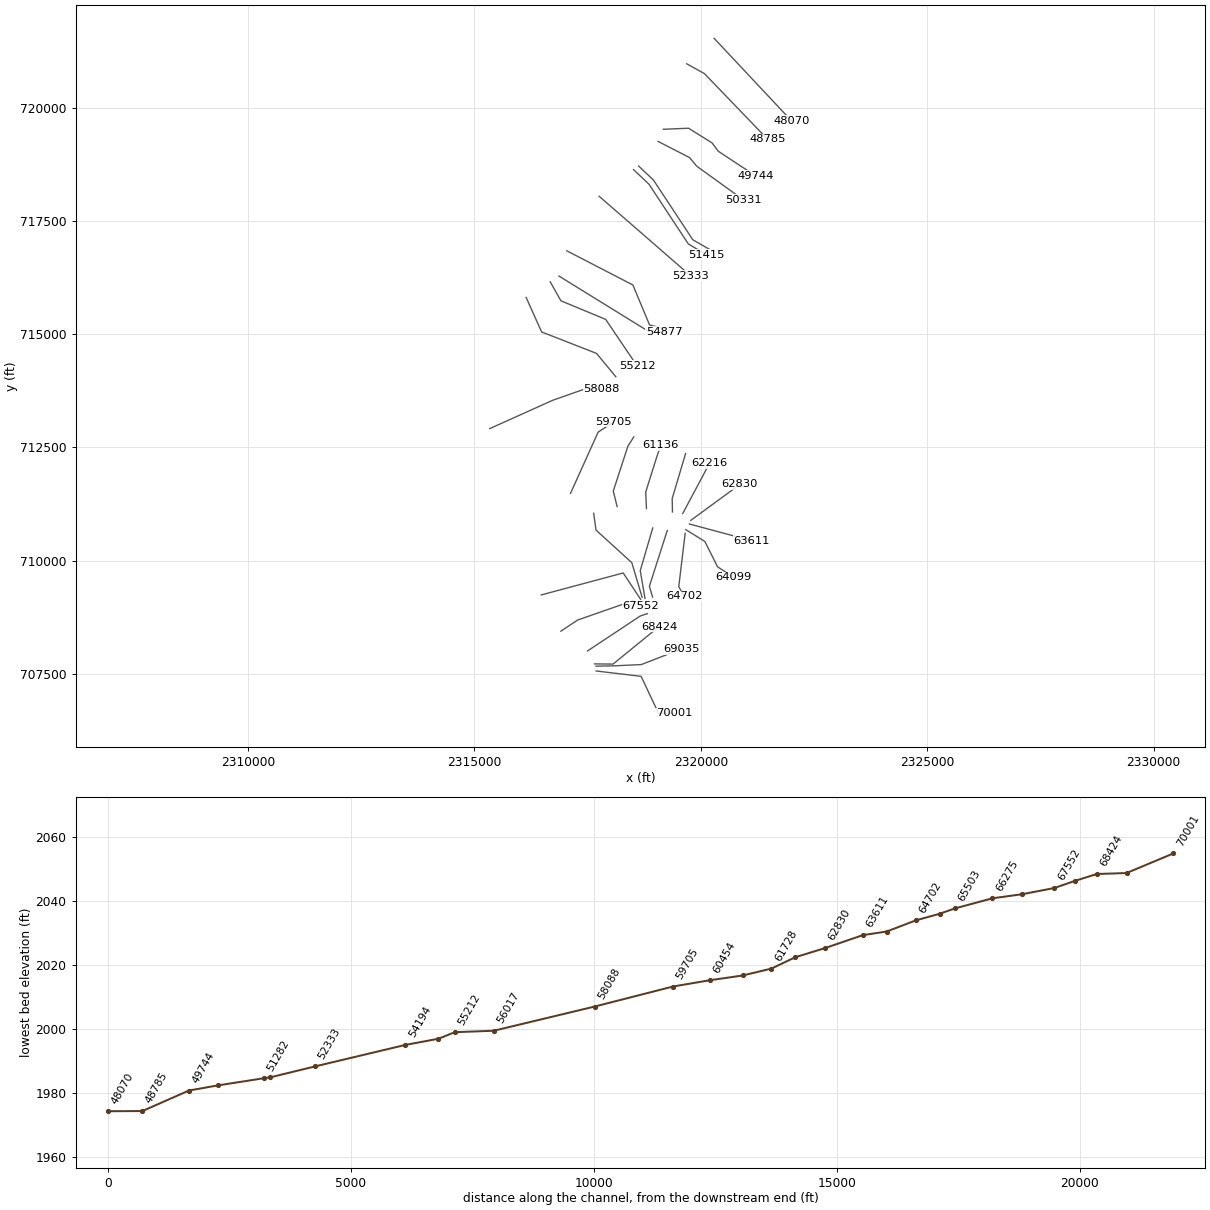
HEC-RAS study SHAVERSFK.prj: SHAVERSFK

--- SHAVERSFK.g01 (geometry) --- (continued)

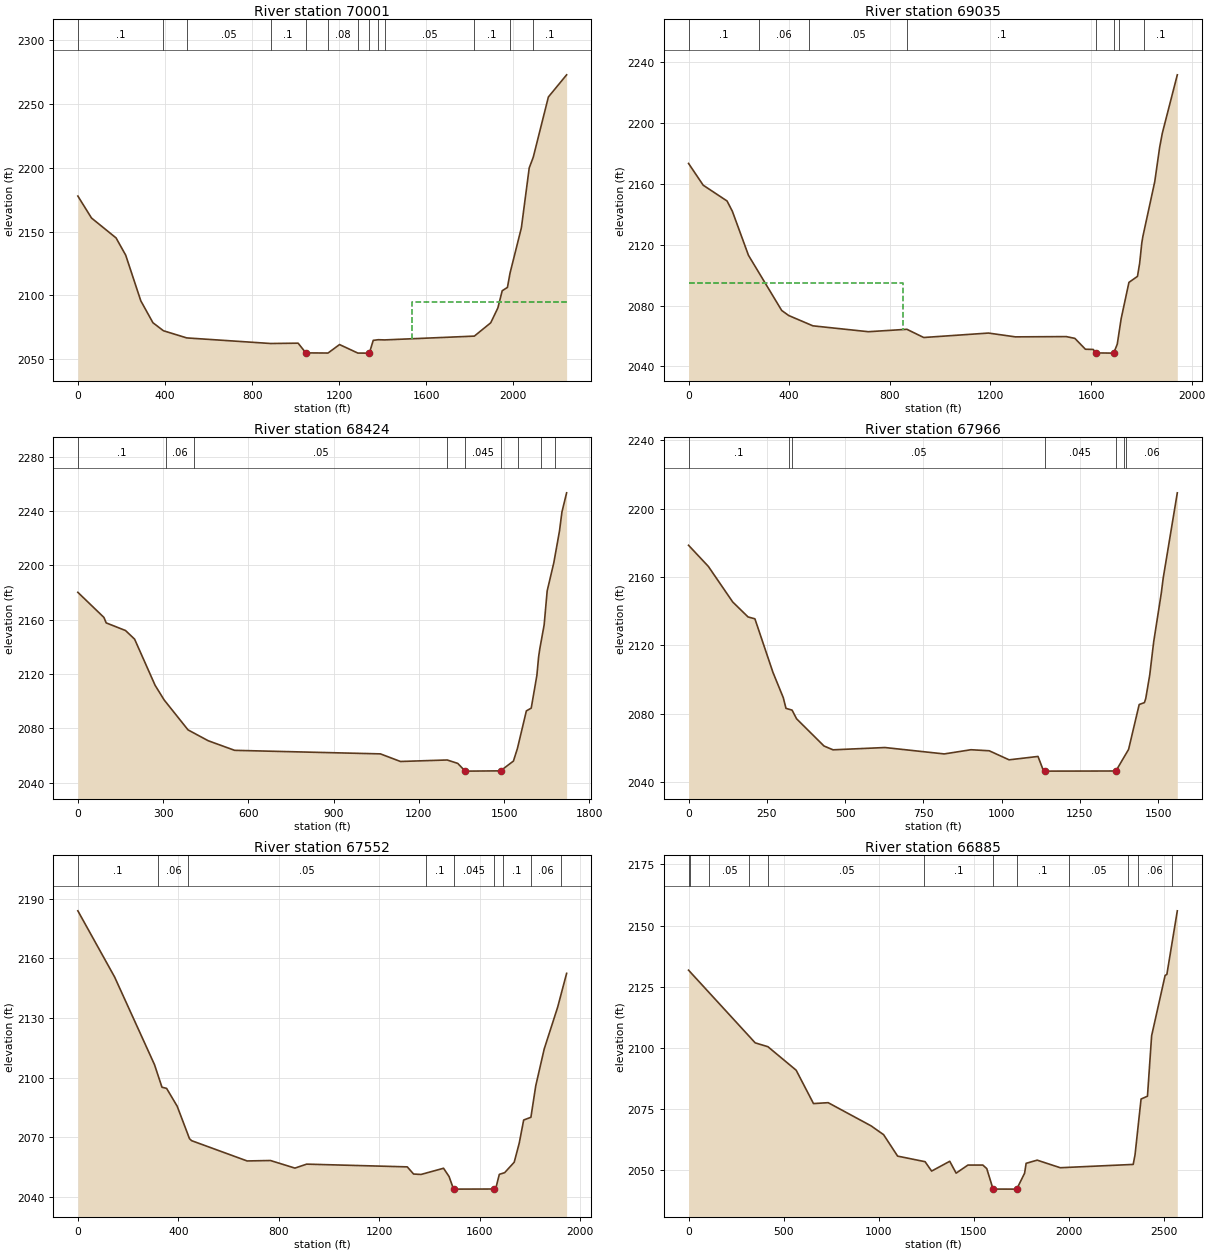
Type RM Length L Ch R = 1 ,70001   ,819.9,965.6,1026.7
BEGIN DESCRIPTION:
Disconnected without IFA
END DESCRIPTION:
XS GIS Cut Line= 4
2317689.91871693707558.5954230722318681.90251021707440.502114348
2319067.67398537706621.7218405292319407.88528564706625.658284153
#Sta/Elev= 30
       0 2177.87    62.7 2160.67   175.5 2145.08   219.8 2131.55     289 2095.85
   344.7 2078.69     393 2072.39   500.1 2066.78   885.2 2062.41  1011.5 2062.66
  1046.9 2055.06  1148.6 2054.94  1201.6 2061.58  1285.7 2054.91  1333.8 2054.87
  1338.7    2055  1356.4 2064.87  1379.7 2065.36    1409 2065.22  1820.6 2068.19
  1895.9 2078.62  1928.6 2090.25  1948.6 2103.73  1972.6 2106.33  1984.6 2117.61
  2036.6 2152.99  2072.6 2199.88  2091.3 2208.36  2160.6 2255.45  2244.3  2272.8
#Mann= 13 ,-1,0
       0      .1       0     393     .06       0   500.1     .05       0
   885.2      .1       0  1046.9    .045       0  1148.6     .08       0
  1285.7    .045       0  1338.7     .06       0  1379.7      .1       0
    1409     .05       0  1820.6      .1       0  1984.6     .06       0
  2091.3      .1       0
#XS Ineff= 2 , 0
                         1534.61         2094.85
Permanent Ineff=
       F       F
Bank Sta=1046.9,1338.7
XS Rating Curve= 0 ,0
Exp/Cntr(USF)=0,0
Exp/Cntr=0.3,0.1

Type RM Length L Ch R = 1 ,69035   ,611.1,610.5,622.8
XS GIS Cut Line= 4
 2317685.9822733707664.8794009242318083.56307934707672.752288172
2318685.83895383707700.3073935412319563.66588201 708042.77798884
#Sta/Elev= 30
       0 2173.32    58.2 2159.03     153 2148.66   174.2 2141.88   238.2 2112.96
   370.3 2076.75   398.3 2073.42   494.4 2066.66   714.6 2062.81   867.8 2064.39
   934.8    2059    1192 2061.92  1299.3 2059.42  1501.1  2059.6  1535.5 2058.44
  1577.5  2051.3  1608.5 2051.16  1619.3 2048.89  1690.1 2048.74  1704.2 2054.72
  1719.6 2071.39  1750.5  2095.2  1784.5 2099.16  1793.1  2107.8  1801.7 2121.19
    1806 2125.42  1853.2 2161.41  1872.4 2183.73  1883.3 2193.28  1942.8 2231.52
#Mann= 8 ,-1,0
       0      .1       0     280     .06       0  477.66     .05       0
  867.66      .1       0  1619.3    .045       0  1690.1      .1       0
 1710.56     .06       0 1810.56      .1       0
#XS Ineff= 2 , 0
          852.46 2094.99
Permanent Ineff=
       F       F
Bank Sta=1619.3,1690.1
XS Rating Curve= 0 ,0
Exp/Cntr(USF)=0,0
Exp/Cntr=0.3,0.1

Type RM Length L Ch R = 1 ,68424   ,475,458.2,448.6
XS GIS Cut Line= 3
2317652.45269856707715.1955767732318062.70042674707711.466051971
2319077.13117277708539.420557922
#Sta/Elev= 30
       0  2180.2    91.7 2161.71    99.7 2157.68   167.7 2152.05   199.7 2145.69
   271.7 2111.74   303.7 2100.88   387.7 2078.83   458.6 2070.84   551.6 2063.76
  1064.6 2061.15    1135 2055.55  1299.5 2056.65  1336.5 2054.16  1361.9 2048.68
  1367.4 2048.44  1487.1 2048.64  1532.6 2055.86  1546.8 2065.25  1578.1 2092.83
  1595.2 2094.86  1615.1 2119.01  1621.2 2132.64  1625.5 2138.72  1640.7 2156.27
  1651.3 2181.23  1674.8 2202.11  1694.7 2225.47  1703.2 2239.33  1719.7 2253.52
#Mann= 9 ,-1,0
       0      .1       0     310     .06       0     410     .05       0
 1300.26      .1       0  1361.9    .045       0  1487.1    .025       0
 1550.26      .1       0 1630.26     .06       0 1680.26      .1       0
Bank Sta=1361.9,1487.1
XS Rating Curve= 0 ,0
Exp/Cntr(USF)=0,0
Exp/Cntr=0.3,0.1

Type RM Length L Ch R = 1 ,67966   ,437.9,414.5,390.9
XS GIS Cut Line= 3
 2317499.5421817708002.3689864952318663.15391979708774.380620422
2318819.79396146708826.593967644
#Sta/Elev= 30
       0 2178.54    63.2 2166.17     141 2145.35   190.1 2136.56     212 2135.47
   269.6 2104.12   302.6  2089.3   311.3 2083.02   330.7 2081.99   345.1 2076.91
   432.8 2060.96   461.6 2058.74   627.3 2060.08   816.8 2056.33   902.3 2058.79
   960.5 2058.19    1024 2052.88  1116.4 2054.86  1133.8 2046.52  1138.4 2046.26
  1365.3 2046.34  1405.8 2058.98  1439.7 2085.28  1456.4 2086.39  1460.7 2088.83
  1473.4  2102.6    1486 2121.97  1510.1 2150.26  1516.4 2159.29  1561.5 2209.26
#Mann= 7 ,-1,0
       0      .1       0     320     .06       0     330     .05       0
  1138.4    .045       0  1365.3    .025       0    1390      .1       0
 1396.42     .06       0
Bank Sta=1138.4,1365.3
XS Rating Curve= 0 ,0
Exp/Cntr(USF)=0,0
Exp/Cntr=0.3,0.1

Type RM Length L Ch R = 1 ,67552   ,671.6,667.2,664.8
XS GIS Cut Line= 4
2316910.27726305 708438.72338828 2317279.5002184708684.872025184
2318506.51387812709113.767377366 2318674.3424942709001.881633318
#Sta/Elev= 30
       0 2183.84   146.5 2150.56   305.1 2106.58   334.8 2095.25   353.2 2094.67
   395.4  2085.7   444.3 2069.42   452.9  2068.4   673.7 2058.22   766.5 2058.44
     864 2054.63   910.6 2056.62  1311.1 2055.25  1336.2 2051.65    1366 2051.44
  1455.5 2054.55  1477.5 2050.39  1495.3 2044.07  1656.9 2044.13  1664.8 2045.18
  1677.5 2051.49  1698.7 2052.33  1736.8 2057.59  1756.7 2067.15  1774.4 2078.78
  1803.2 2080.15  1822.5 2095.97  1856.1 2114.44  1909.6 2135.42  1945.3 2152.43
#Mann= 9 ,-1,0
       0      .1       0     320     .06       0     440     .05       0
 1383.75      .1       0  1495.3    .045       0  1656.9    .025       0
 1693.75      .1       0 1803.56     .06       0 1923.56      .1       0
Bank Sta=1495.3,1656.9
XS Rating Curve= 0 ,0
Exp/Cntr(USF)=0,0
Exp/Cntr=0.3,0.1

Type RM Length L Ch R = 1 ,66885   ,671.1,609.7,553.6
XS GIS Cut Line= 3
2316477.65238606709240.5712206192318286.47191483709725.409444825
2318670.61296939709143.603575778
#Sta/Elev= 30
       0 2131.73   350.5 2101.98   417.3 2100.41   565.8 2090.79   656.9 2077.14
   734.1  2077.5   959.4 2068.03  1025.5 2064.41  1099.3 2055.63  1243.6 2053.35
  1278.1 2049.51  1373.3 2053.52  1406.9 2048.66  1468.9 2051.97  1547.3 2051.97
    1568 2050.52  1601.1 2042.14  1725.4 2042.12  1766.8 2048.62    1775 2052.68
    1833 2053.98  1954.4 2050.88  2337.9 2052.23  2347.5 2056.09  2379.3 2078.99
    2413 2080.16  2434.8 2104.88  2505.7 2129.56    2515 2130.01  2569.9 2156.02
#Mann= 12 ,-1,0
       0     .05       0      10     .06       0     110     .05       0
     320     .06       0     420     .05       0    1240      .1       0
  1601.1    .045       0  1725.4      .1       0 2002.67     .05       0
 2312.67      .1       0 2362.67     .06       0 2542.67      .1       0
Bank Sta=1601.1,1725.4
XS Rating Curve= 0 ,0
Exp/Cntr(USF)=0,0
Exp/Cntr=0.3,0.1

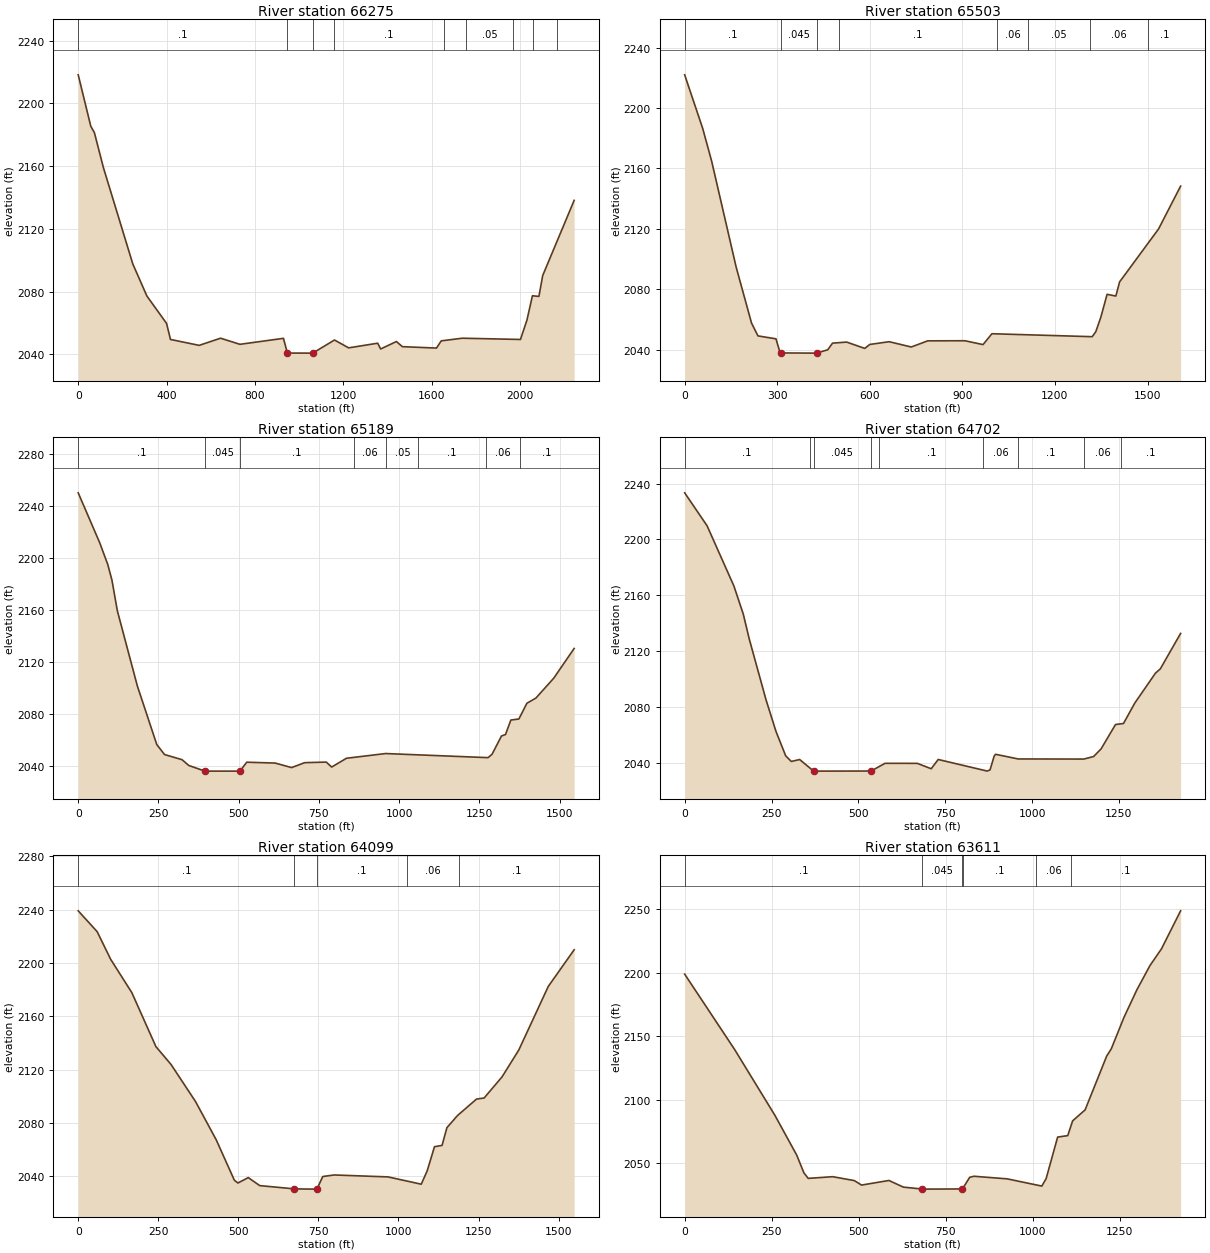
Type RM Length L Ch R = 1 ,66275   ,837.6,772.2,710
XS GIS Cut Line= 4
2317633.80507455711045.6612245842317686.01842178710672.708744426
2318476.67767971709952.9104577212318704.17869261709188.357873397
#Sta/Elev= 30
       0 2218.27      57 2185.44    73.2 2181.44   113.6  2159.3     247 2097.68
   310.8 2077.24   399.7 2059.79   417.4 2049.57   547.2  2045.8   643.9 2050.36
   731.7 2046.47   928.5 2050.28   946.3 2040.89  1059.2 2040.85  1061.1 2040.87
  1159.3 2049.21  1223.4 2044.21  1354.7 2047.17  1368.2  2043.5  1439.5 2048.25
  1466.4 2044.97  1620.8 2044.07  1642.2 2048.67  1737.7 2050.36  2000.6 2049.56
  2029.8 2061.82  2054.8 2077.42  2084.1    2077  2101.3 2090.34  2243.5 2138.23
#Mann= 9 ,-1,0
       0      .1       0   946.3    .045       0  1061.1    .025       0
 1156.59      .1       0 1655.82     .06       0 1755.82     .05       0
 1965.82      .1       0 2055.82     .06       0 2165.82      .1       0
Bank Sta=946.3,1061.1
XS Rating Curve= 0 ,0
Exp/Cntr(USF)=0,0
Exp/Cntr=0.3,0.1

Type RM Length L Ch R = 1 ,65503   ,317,313.7,313.4
XS GIS Cut Line= 3
2318939.13875511710721.1925668472318663.15391979709777.622792047
2318767.58061424709162.251199786
#Sta/Elev= 30
       0 2221.92    58.4 2186.44    87.5 2164.72   166.8 2094.67   216.7 2057.57
   237.6 2049.09   295.9 2047.15   308.4 2038.48   312.6 2037.81   425.1 2037.69
     428 2037.75   463.5 2039.87   479.3  2044.3   525.1    2045   583.5 2040.81
   600.1 2043.44   662.7 2045.25   734.4 2041.75   787.7 2045.82   908.5 2045.88
   966.9 2043.34   995.7 2050.53  1320.8 2048.57  1332.5 2051.93  1348.7 2061.44
    1369 2076.62  1397.4 2075.48  1409.6 2084.85  1535.9 2119.91  1607.3 2148.25
#Mann= 8 ,-1,0
       0      .1       0   312.6    .045       0     428    .025       0
     500      .1       0  1013.1     .06       0  1113.1     .05       0
  1313.1     .06       0  1503.1      .1       0
Bank Sta=312.6,428
XS Rating Curve= 0 ,0
Exp/Cntr(USF)=0,0
Exp/Cntr=0.3,0.1

Type RM Length L Ch R = 1 ,65189   ,476.5,487.4,500
XS GIS Cut Line= 3
2319259.87788804710665.2496948232318864.54825908  709430.7769855
2318935.40923031709192.087398199
#Sta/Elev= 30
       0  2249.9    67.3 2211.35    92.1 2194.83   105.1 2182.84   121.9 2159.29
   184.3 2101.43   244.8 2056.47   268.9 2048.77   323.5 2044.82   344.5 2040.36
   394.9 2036.03   504.1 2036.02   525.1 2042.88   613.8 2042.21   664.7 2038.74
   705.7 2042.52   772.8 2042.97   789.7 2039.16   835.9 2045.91   957.7 2049.53
  1276.9 2046.38  1289.5 2049.02  1318.8 2063.02  1331.3 2064.16    1348 2075.28
    1373 2076.08    1398 2088.19  1425.9 2092.14  1481.5 2107.41  1545.2  2130.3
#Mann= 8 ,-1,0
       0      .1       0   394.9    .045       0   504.1      .1       0
     860     .06       0     960     .05       0    1060      .1       0
    1270     .06       0 1376.23      .1       0
Bank Sta=394.9,504.1
XS Rating Curve= 0 ,0
Exp/Cntr(USF)=0,0
Exp/Cntr=0.3,0.1

Type RM Length L Ch R = 1 ,64702   ,569.1,602.9,634.2
XS GIS Cut Line= 3
2319655.20751701710601.8477731962319513.48557455709423.317935897
 2319632.8303682709214.464547008
#Sta/Elev= 30
       0 2233.32    64.5 2209.72   141.7 2166.59   168.8 2146.37     186 2128.51
   234.3 2084.97   262.5 2062.67   290.7 2044.96   306.9 2040.89     331 2042.28
   371.3 2033.97   536.5 2034.04   576.8 2039.57   669.5 2039.54   709.7 2035.68
   729.8 2042.31   870.9 2034.02     879 2034.86     891 2044.83   895.1 2046.03
     960 2042.69  1148.9 2042.61  1177.1 2044.43  1198.7 2049.91  1240.2 2067.35
  1263.2  2068.1  1295.4 2082.61  1355.3  2104.2  1369.2 2107.23  1427.6 2132.62
#Mann= 9 ,-1,0
       0      .1       0     360    .025       0   371.3    .045       0
   536.5    .025       0     560      .1       0     860     .06       0
     960      .1       0    1150     .06       0 1257.02      .1       0
Bank Sta=371.3,536.5
XS Rating Curve= 0 ,0
Exp/Cntr(USF)=0,0
Exp/Cntr=0.3,0.1

Type RM Length L Ch R = 1 ,64099   ,457.4,487.8,532.1
XS GIS Cut Line= 4
2319670.01647603710682.5921841042320090.66094382 710421.11048791
2320369.19579411709864.0407873242320727.31203021709625.296629929
#Sta/Elev= 30
       0 2239.24    59.1 2223.65   101.4 2202.86   167.4 2177.88   242.7 2137.36
   289.8    2124   366.4 2096.15   431.1 2067.39   487.6 2037.13   498.7 2035.07
     531 2039.13   566.8 2033.11   675.3 2030.65   740.2 2030.47   745.7 2030.59
   763.5 2039.92   799.3 2041.09   967.4 2039.64  1071.1 2034.17  1089.7 2044.21
  1112.4 2062.28  1136.1 2063.29  1151.2 2076.55  1184.2 2085.65  1243.5    2098
  1267.5 2098.85  1323.6 2114.75  1375.7 2134.85  1467.8 2182.56  1548.5 2210.02
#Mann= 5 ,-1,0
       0      .1       0   675.3    .045       0   745.7      .1       0
 1025.29     .06       0 1188.12      .1       0
Bank Sta=675.3,745.7
XS Rating Curve= 0 ,0
Exp/Cntr(USF)=0,0
Exp/Cntr=0.3,0.1

Type RM Length L Ch R = 1 ,63611   ,743,781.2,821.8
XS GIS Cut Line= 2
2319749.59786183710807.648647501 2321125.2189592 710438.16364201
#Sta/Elev= 30
       0 2198.84   143.5 2139.44   259.5 2087.39   321.6  2056.3   342.3 2042.29
   354.7 2037.84   425.1 2039.17   487.3 2036.09     508 2032.55   586.7 2036.19
   628.1 2030.94  681.152029.462   681.9 2029.36   797.9 2029.51   818.6 2038.69
     831  2039.5   926.3 2037.46  1025.7 2031.76  1038.1  2037.6  1071.2  2070.4
  1100.2 2071.54  1114.2 2083.16  1150.1 2091.85  1212.1 2134.29  1225.2 2139.91
  1261.8 2164.84    1299 2186.62  1336.3  2205.6  1369.5 2218.82  1424.4 2248.77
#Mann= 6 ,-1,0
       0      .1       0  681.15    .045       0   797.9    .025       0
     800      .1       0    1010     .06       0    1110      .1       0
Bank Sta=681.15,797.9
XS Rating Curve= 0 ,0
Exp/Cntr(USF)=0,0
Exp/Cntr=0.3,0.1

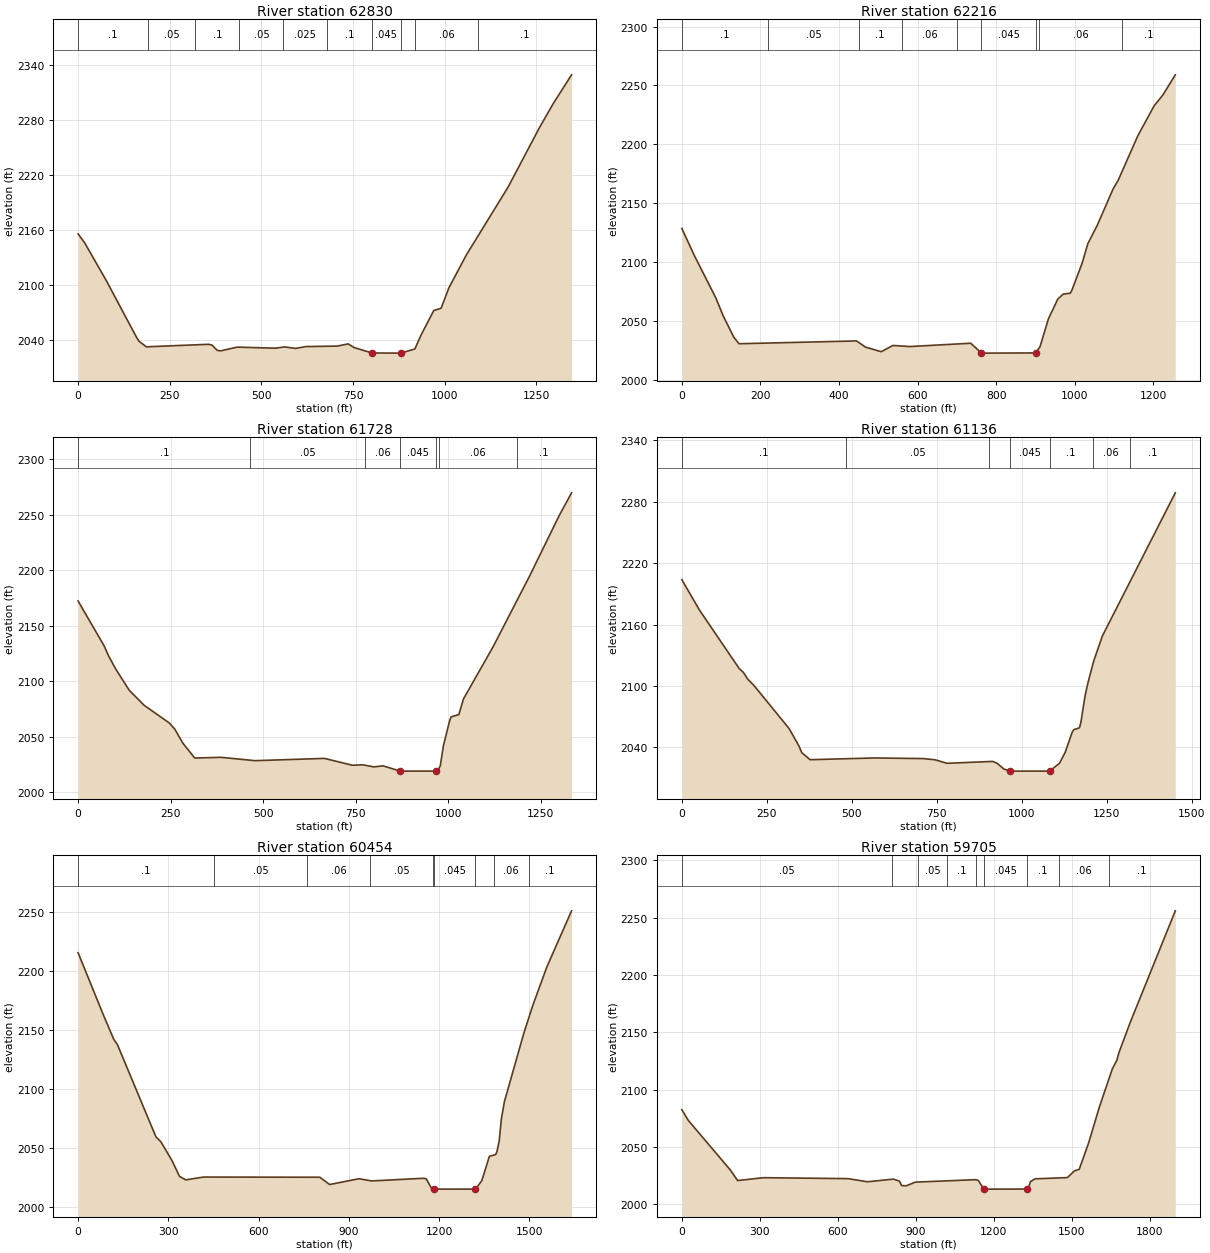
Type RM Length L Ch R = 1 ,62830   ,588.2,613.4,635.1
XS GIS Cut Line= 2
2319778.01978533710887.230033299  2320863.737263 711683.04389128
#Sta/Elev= 30
       0 2155.33    17.6 2145.88    77.3 2104.19   160.3 2041.91   166.3 2038.19
   186.2 2032.18   354.9 2034.91   364.7  2034.2   379.6 2028.28     389 2027.81
   434.1 2031.83   538.3 2030.69   563.8 2032.09   592.8 2030.41   621.1 2032.45
     707 2032.97   736.7 2035.36   752.7 2031.42   801.7 2025.45   880.5  2025.3
   918.7 2029.86   935.1 2044.64   970.2 2071.75   990.3 2074.28  1011.4 2096.46
  1058.9 2132.24  1173.1 2206.46  1257.4 2270.39  1295.6 2297.13  1346.1 2328.84
#Mann= 10 ,-1,0
       0      .1       0     190     .05       0     320      .1       0
     440     .05       0     560    .025       0     680      .1       0
   801.7    .045       0   880.5      .1       0     920     .06       0
    1090      .1       0
Bank Sta=801.7,880.5
XS Rating Curve= 0 ,0
Exp/Cntr(USF)=0,0
Exp/Cntr=0.3,0.1

Type RM Length L Ch R = 1 ,62216   ,476.5,488.3,499.5
XS GIS Cut Line= 2
2319601.80385963711040.7084201952320192.97986842712149.163436669
#Sta/Elev= 30
       0 2128.41    32.3 2105.07    86.7  2069.3   104.8 2054.47     132  2036.1
   145.6 2030.41   444.8  2032.8   467.5 2027.52   507.7 2023.64   537.2 2028.93
   580.8 2028.03   735.3 2030.83   762.8 2022.53   766.7 2022.43   900.9  2022.6
   911.7  2027.8   933.4 2051.74     957 2068.33   970.7 2072.59   988.8 2073.37
   992.5 2075.54  1019.1 2098.96  1033.5 2115.43  1057.6 2131.13  1097.6 2161.82
  1110.8 2169.36    1161 2207.33  1202.4 2232.71  1224.5 2241.85  1256.2 2259.02
#Mann= 9 ,-1,0
       0      .1       0     220     .05       0     450      .1       0
     560     .06       0     700      .1       0   762.8    .045       0
   900.9      .1       0     910     .06       0    1120      .1       0
Bank Sta=762.8,900.9
XS Rating Curve= 0 ,0
Exp/Cntr(USF)=0,0
Exp/Cntr=0.3,0.1

Type RM Length L Ch R = 1 ,61728   ,592.4,591.5,590.7
XS GIS Cut Line= 3
2319374.42847164711074.8147283952319368.74408694711370.402732787
2319664.33209133712365.170055263
#Sta/Elev= 30
       0 2172.32    70.4 2131.84    82.4 2122.77   102.4 2110.61   138.4 2091.75
   178.4 2078.29   246.4 2062.33   261.2 2056.87   282.4 2044.45   315.2  2030.7
   386.2 2031.35     478 2028.33   665.8 2030.38   740.9 2024.23   770.1 2024.57
   799.2 2022.72   824.3 2023.65   870.2 2018.91   966.2  2018.9   974.5 2020.91
   978.7 2023.76   987.1 2041.67  1003.8 2064.16  1007.9 2067.84  1028.8 2069.83
  1041.3 2083.95    1121 2130.77  1220.7 2195.26    1300 2249.33  1333.4 2269.85
#Mann= 7 ,-1,0
       0      .1       0  465.64     .05       0  775.64     .06       0
   870.2    .045       0   966.2      .1       0  975.64     .06       0
 1185.64      .1       0
Bank Sta=870.2,966.2
XS Rating Curve= 0 ,0
Exp/Cntr(USF)=0,0
Exp/Cntr=0.3,0.1

Type RM Length L Ch R = 1 ,61136   ,682.9,682,683
XS GIS Cut Line= 4
2318800.30561695711148.7117294932318783.25246285711512.512350284
2319033.36538965712308.3262082652319118.63116015712547.070365659
#Sta/Elev= 30
       0 2203.86    52.5 2173.85   168.7 2117.06   180.7  2113.4   193.6 2106.82
   212.7 2100.28   315.5 2058.43   344.9 2041.11   352.9 2034.77   377.5 2027.92
   567.4 2029.62     710 2029.01   745.1 2027.83   780.2  2024.4   914.2 2026.25
     927 2024.57   947.7 2018.81   964.5 2016.77  1081.9 2016.75  1111.2 2024.42
    1128 2035.19    1149 2055.22  1153.5  2057.3  1169.9 2059.08  1174.1 2064.37
  1186.7  2090.8  1194.9  2103.1    1212 2124.58  1237.5 2148.95  1451.9 2288.76
#Mann= 7 ,-1,0
       0      .1       0   484.2     .05       0   904.2     .06       0
   964.5    .045       0  1081.9      .1       0 1208.39     .06       0
 1318.39      .1       0
Bank Sta=964.5,1081.9
XS Rating Curve= 0 ,0
Exp/Cntr(USF)=0,0
Exp/Cntr=0.3,0.1

Type RM Length L Ch R = 1 ,60454   ,757.4,749.7,739.1
XS GIS Cut Line= 4
2318152.28576117711194.1868070922318067.01999067711535.249889083
2318391.02991856712530.0172115592318521.77076666712734.655060755
#Sta/Elev= 30
       0 2215.66    81.4 2164.53   118.5 2142.29   130.9 2137.66   258.7 2059.63
   275.2 2055.43   312.3 2039.43   337.1 2026.08   357.8 2023.09   416.7 2025.48
   803.7 2025.33   836.3 2019.15   934.1 2024.06   976.2 2022.19  1147.3 2024.43
  1157.1  2024.1  1173.9 2016.47  1182.2 2015.28  1321.2 2015.25  1342.2  2022.4
  1367.4 2043.05  1388.5 2044.62  1392.7 2047.21  1399.9 2055.78  1407.3 2074.84
  1417.5 2089.54  1481.6 2147.14  1510.9 2170.37  1558.2  2203.4  1640.6 2251.15
#Mann= 9 ,-1,0
       0      .1       0  451.56     .05       0  761.56     .06       0
  971.56     .05       0 1181.56      .1       0  1182.2    .045       0
  1321.2      .1       0 1381.56     .06       0 1497.76      .1       0
Bank Sta=1182.2,1321.2
XS Rating Curve= 0 ,0
Exp/Cntr(USF)=0,0
Exp/Cntr=0.3,0.1

Type RM Length L Ch R = 1 ,59705   ,1651.1,1616.9,1589.7
XS GIS Cut Line= 3
2317123.41315313711486.3079383492317732.28032073712838.528851534
2318080.02412836713064.542929521
#Sta/Elev= 30
       0 2082.51    25.1 2073.15   187.3 2029.77   214.5 2020.77   313.6 2023.27
   639.2 2022.46   713.8 2019.72   813.4 2022.02   836.6 2020.31   845.4 2016.44
     863 2016.22     898 2019.41  1130.6 2021.55  1140.1 2020.87  1161.3 2013.37
  1177.3 2013.31    1328 2013.38  1332.3 2014.16  1341.1 2019.93  1358.7 2022.28
    1483 2023.37  1509.9 2029.27  1528.2 2030.58    1564 2053.29  1605.3 2084.54
  1655.4    2118  1672.8 2125.61  1681.4 2132.55  1724.8 2158.87  1897.7 2255.86
#Mann= 9 ,-1,0
       0     .05       0     810     .06       0     910     .05       0
    1020      .1       0    1130    .025       0  1161.3    .045       0
    1328      .1       0    1450     .06       0 1642.98      .1       0
Bank Sta=1161.3,1328
XS Rating Curve= 0 ,0
Exp/Cntr(USF)=0,0
Exp/Cntr=0.3,0.1

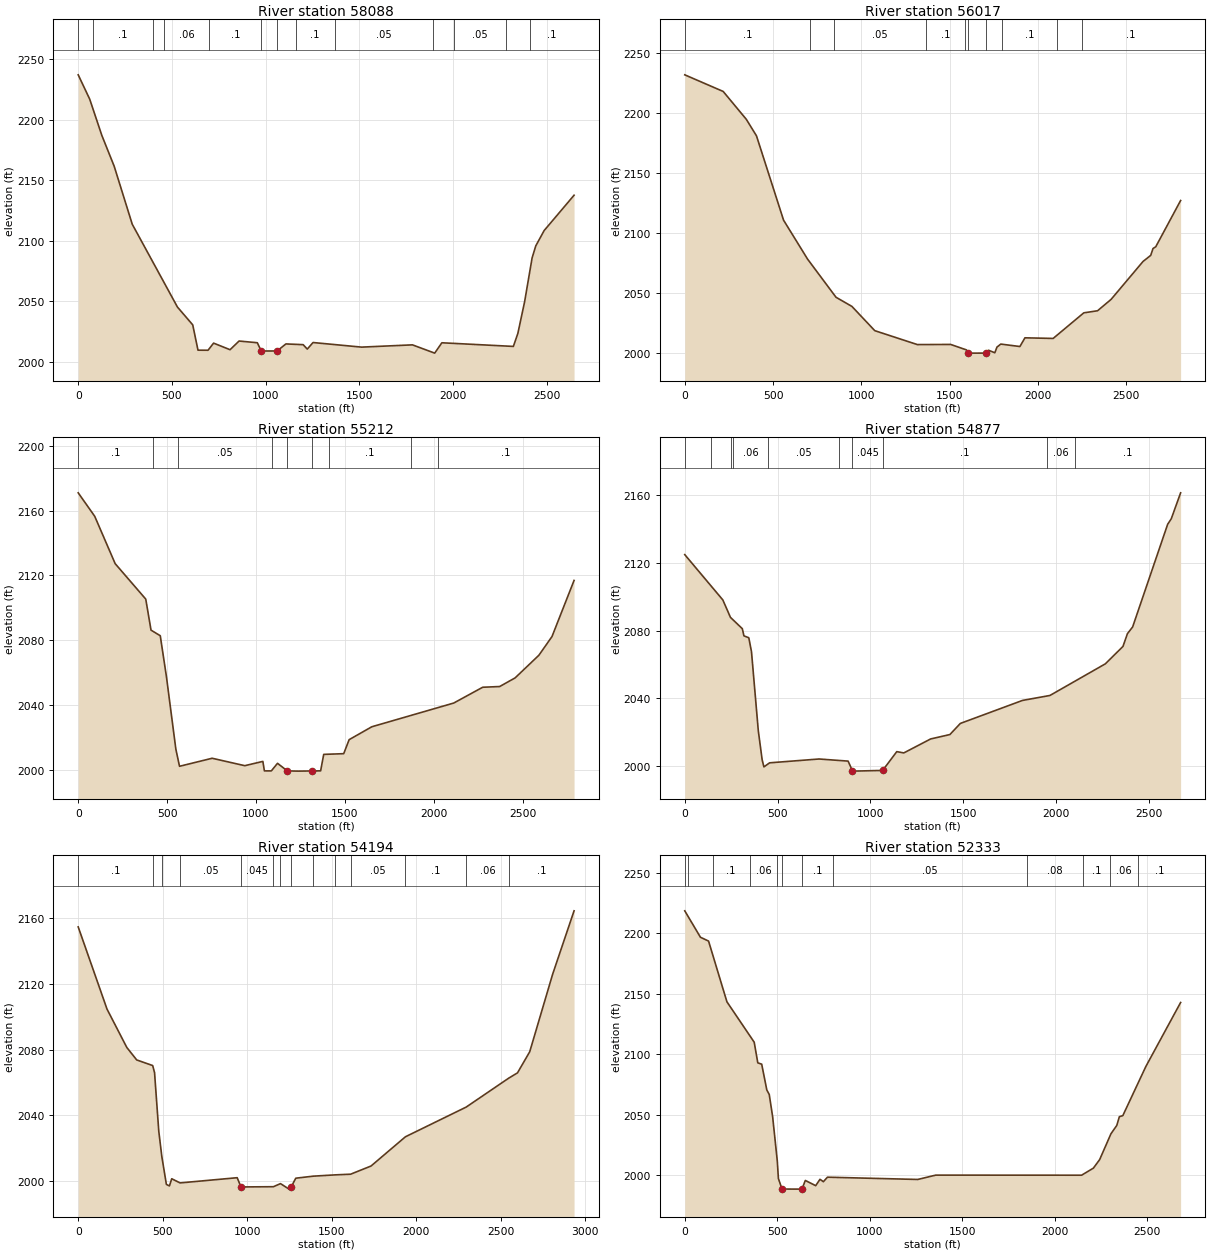
Type RM Length L Ch R = 1 ,58088   ,2112.6,2070.8,2052.4
XS GIS Cut Line= 4
2315337.09558987 712916.002033652316727.22695455713541.561147759
 2317479.8736587713806.946248699 2317803.8239489713790.363348817
#Sta/Elev= 30
       0 2236.96    61.4 2216.87   126.2 2186.89     192 2161.46   288.5 2113.52
   529.7 2045.11   611.3 2030.39   639.4 2009.48   692.9 2009.41   722.7  2015.3
   810.5 2009.86   858.7 2017.04   956.1 2015.62   977.1 2008.78    1062 2008.83
  1108.7 2014.64  1200.8 2014.02  1222.8 2010.37  1253.5 2015.79  1512.7    2012
  1784.1 2013.87  1902.9 2007.04  1941.1 2015.59  2322.8 2012.58  2346.8 2023.33
  2382.8 2049.44  2422.9 2085.77  2442.5 2095.67    2487 2108.28  2646.8  2137.5
#Mann= 13 ,-1,0
       0     .06       0      80      .1       0     400     .05       0
     460     .06       0     700      .1       0   977.1    .045       0
    1062     .08       0    1160      .1       0    1370     .05       0
  1894.4     .08       0  2004.4     .05       0  2284.4     .06       0
 2412.46      .1       0
Bank Sta=977.1,1062
XS Rating Curve= 0 ,0
Exp/Cntr(USF)=0,0
Exp/Cntr=0.3,0.1

Type RM Length L Ch R = 1 ,56017   ,803.1,805.4,798.5
XS GIS Cut Line= 4
2316142.32168502715815.6536199642316484.55490033715053.133999881
2317697.38138267714578.8107716412318123.67187893714062.458902923
#Sta/Elev= 30
       0 2231.77   217.5  2217.9   348.3 2194.68   406.1 2180.86   559.5 2110.45
   695.4 2077.97   856.4 2046.13   946.6 2038.47  1075.9 2018.25  1317.1 2006.63
  1505.5 2006.75    1595 2002.19  1604.2  1999.5  1604.8  1999.5  1707.3 1999.53
  1720.2 2001.92  1755.6 1999.79  1767.9 2004.55  1789.5 2007.05  1897.6 2005.01
  1926.3 2012.28  2085.9 2011.76  2259.5 2033.13  2337.3 2034.85    2414 2044.35
  2594.8 2075.99  2638.4  2081.1  2651.4  2086.8  2666.9 2088.28  2807.7 2126.86
#Mann= 10 ,-1,0
       0      .1       0     710     .06       0   845.8     .05       0
  1365.8      .1       0  1585.8    .025       0  1604.8    .045       0
  1707.3    .025       0  1795.8      .1       0  2105.8     .06       0
 2248.08      .1       0
Bank Sta=1604.8,1707.3
XS Rating Curve= 0 ,0
Exp/Cntr(USF)=0,0
Exp/Cntr=0.3,0.1

Type RM Length L Ch R = 1 ,55212   ,350,334.6,322.1
XS GIS Cut Line= 4
 2316673.8598048716162.1700089742316910.21687066715741.979669667
2317899.41496111715330.5432957632318590.97822789714306.329343703
#Sta/Elev= 30
       0 2170.94    92.9 2156.45     208 2127.18     380 2105.29   409.6 2086.13
   461.6 2082.67   496.5 2057.25   549.2 2012.68   569.9 2002.03   753.5 2006.99
     937  2002.4  1038.7 2005.05  1047.4 1999.19  1086.4 1999.18  1121.1 2003.87
  1176.51999.166    1238 1999.04  1316.71999.146  1363.7 1999.21    1381 2009.38
  1493.6 2009.82    1524 2018.47  1651.6 2026.44  2112.4 2041.09  2275.3 2050.85
  2370.8 2051.29  2457.6 2056.62  2591.3  2070.6  2665.2 2082.17  2789.3 2116.82
#Mann= 9 ,-1,0
       0      .1       0     420     .06       0   562.1     .05       0
  1092.1      .1       0  1176.5    .045       0  1316.7    .025       0
  1412.1      .1       0 1873.46     .06       0 2023.46      .1       0
Bank Sta=1176.5,1316.7
XS Rating Curve= 0 ,0
Exp/Cntr(USF)=0,0
Exp/Cntr=0.3,0.1

Type RM Length L Ch R = 1 ,54877   ,647,683.1,676.7
XS GIS Cut Line= 3
2316865.82468339716289.3676377352318854.90457756715060.005758696
2319186.41789326715050.797055482
#Sta/Elev= 30
       0  2124.8     205 2098.05     246 2087.77   309.9 2081.08   318.6 2076.85
   344.8 2075.73   359.3  2067.5     396 2020.82   416.6 2003.77   426.1  1999.5
   456.9  2001.9   723.1 2004.16   879.5 2002.91   902.8 1997.24   905.6    1997
  1065.5 1997.41  1141.6  2008.5  1179.6 2007.75  1324.1    2016  1427.6 2018.59
    1484 2025.16  1818.7 2038.74  1966.4 2041.66  2264.6 2060.33  2359.6 2070.61
  2383.6 2078.13  2411.6  2082.1  2600.1 2142.68  2619.7 2145.98    2670 2161.28
#Mann= 10 ,-1,0
       0      .1       0     140     .06       0     250      .1       0
     260     .06       0     450     .05       0     830      .1       0
   902.8    .045       0  1065.5      .1       0    1950     .06       0
    2100      .1       0
Bank Sta=902.8,1065.5
XS Rating Curve= 0 ,0
Exp/Cntr(USF)=0,0
Exp/Cntr=0.3,0.1

Type RM Length L Ch R = 1 ,54194   ,1417.1,1861.2,1824.3
XS GIS Cut Line= 4
2317040.79004445716846.4941821692318500.36950383716091.380518639
2318868.71763238715207.3450101162319191.02224487715124.466681192
#Sta/Elev= 30
       0 2154.64   170.4 2104.63   287.5 2081.29   346.1 2073.68   440.7 2070.26
   451.7 2065.96   476.7 2030.33   494.7 2014.92   521.7 1997.94   539.7    1997
   553.3 2001.38   602.8 1998.84   940.6 2002.01   963.1 1996.39  1155.1 1996.53
  1196.7 1998.42  1247.7 1995.06  1260.3 1996.42  1287.3 2001.71  1390.9 2002.95
  1517.6 2003.72  1611.6 2004.14  1732.4 2009.11  1936.1 2026.92  2295.7    2045
  2547.2  2062.6  2599.1 2065.82  2671.4 2078.65    2807 2125.83  2933.8 2164.43
#Mann= 14 ,-1,0
       0      .1       0   440.7     .06       0   494.7      .1       0
   602.8     .05       0   963.1    .045       0  1155.1     .08       0
  1196.7    .045       0  1260.3      .1       0  1390.9     .05       0
  1517.6     .06       0  1611.6     .05       0  1936.1      .1       0
  2295.7     .06       0  2547.2      .1       0
Bank Sta=963.1,1260.3
XS Rating Curve= 0 ,0
Exp/Cntr(USF)=0,0
Exp/Cntr=0.3,0.1

Type RM Length L Ch R = 1 ,52333   ,934.6,917.9,902.4
BEGIN DESCRIPTION:
Structure XS 4
END DESCRIPTION:
XS GIS Cut Line= 2
2317754.46454352718052.8343031732319775.77489894716293.971989342
#Sta/Elev= 30
       0 2218.65    84.8 2196.77   128.6 2193.62   227.8 2143.36   375.2 2109.93
   394.6 2092.87   415.8 2091.72   443.3 2070.43   456.5 2066.66   474.8 2048.34
     500 2011.59     506 1997.07   525.5 1988.41   633.2 1988.34   651.5 1995.52
   707.5 1991.19   730.7 1996.47     749 1994.49   771.1 1998.22  1258.9 1996.34
  1356.2 1999.93  2144.4 1999.87    2208 2005.71  2241.9 2012.77  2302.8 2034.11
  2334.4 2041.04  2348.5 2048.29  2367.1 2049.17  2491.7 2089.89  2679.4 2142.79
#Mann= 12 ,-1,0
       0      .1       0      20     .06       0     150      .1       0
     350     .06       0     500      .1       0   525.5    .045       0
   633.2      .1       0     800     .05       0    1850     .08       0
    2150      .1       0    2300     .06       0    2450      .1       0
Bank Sta=525.5,633.2
XS Rating Curve= 0 ,0
Exp/Cntr(USF)=0,0
Exp/Cntr=0.3,0.1

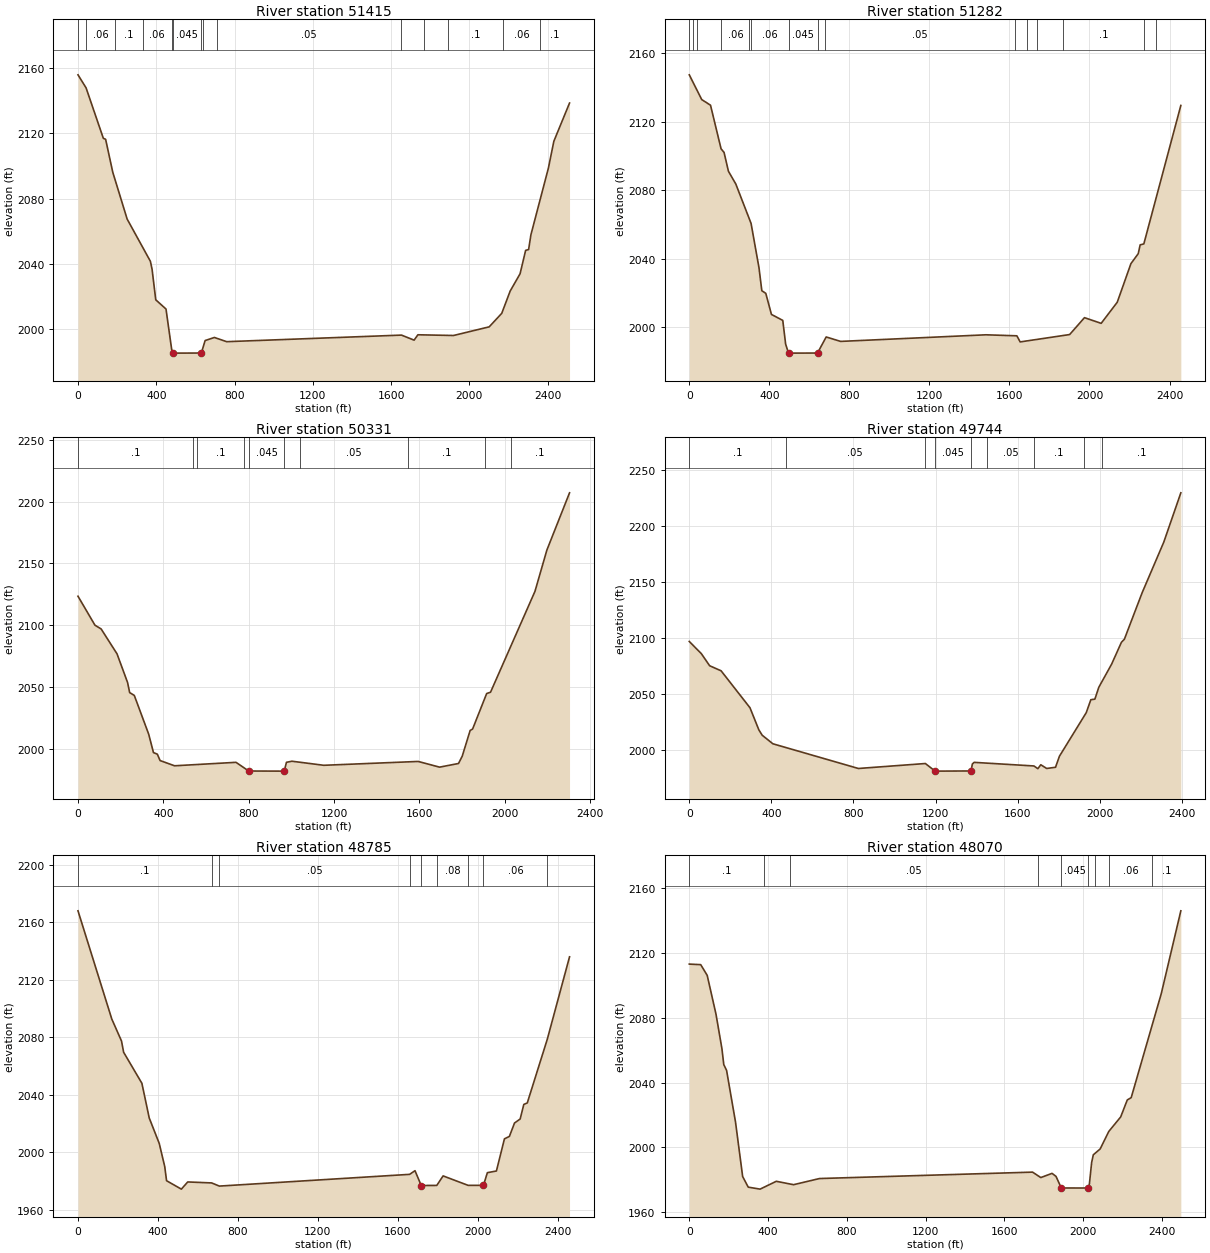
Type RM Length L Ch R = 1 ,51415   ,133.5,133.5,133.5
BEGIN DESCRIPTION:
Structure XS 3
END DESCRIPTION:
XS GIS Cut Line= 4
2318514.18255865718642.1913088552318854.90457756718319.886696373
2319725.12703126716998.4377851962320121.10126946716763.615853244
#Sta/Elev= 30
       0 2156.05    41.3 2148.04   129.5 2117.02   141.2 2116.42   177.6 2096.21
   251.1 2067.38     370 2041.39   378.5 2036.53   397.3 2017.73   449.7 2012.05
   478.6 1987.27   486.3 1984.94   630.3    1985   649.5 1992.67   697.1 1994.57
   759.6 1991.98    1653 1996.02  1717.5 1992.92  1736.7 1996.22  1918.8 1995.78
  2101.1  2001.1  2165.3 2009.42  2208.3 2023.11  2258.8 2033.72  2287.3 2048.12
  2302.5 2048.64  2314.2 2057.68  2403.6 2098.71  2431.5 2115.23  2511.6  2138.7
#Mann= 14 ,-1,0
       0      .1       0      40     .06       0     190      .1       0
     330     .06       0  479.01    .025       0   486.3    .045       0
   630.3    .025       0  639.01      .1       0  709.01     .05       0
 1649.01      .1       0 1769.01     .08       0 1889.01      .1       0
 2171.26     .06       0 2361.26      .1       0
Bank Sta=486.3,630.3
XS Rating Curve= 0 ,0
Exp/Cntr(USF)=0,0
Exp/Cntr=0.3,0.1

Type RM Length L Ch R = 1 ,51282   ,941.9,950.3,960.3
BEGIN DESCRIPTION:
Structure XS 2
END DESCRIPTION:
XS GIS Cut Line= 4
2318626.98917302718720.4652861722318953.89813711718411.973728511
2319824.12059081717090.5248173332320192.46871936716878.724643417
#Sta/Elev= 30
       0  2147.5    62.1 2133.03   106.1 2129.72   158.8 2104.23   173.8 2102.09
   195.6 2091.09   232.4 2083.64   308.8 2060.55   348.4 2034.59   362.5 2021.18
   382.3 2019.65   410.6 2007.31   467.2  2003.8   481.6 1989.89   495.9 1984.66
   640.8 1984.71   684.2 1994.12   756.4 1991.52  1482.6 1995.38  1637.1 1994.79
  1653.6 1991.22  1900.9 1995.53    1975 2005.41  2058.5 2002.09  2138.8 2014.43
  2207.1 2037.01  2243.7 2042.86  2253.3 2048.01  2271.7 2048.57  2456.6 2129.58
#Mann= 15 ,-1,0
       0      .1       0      20     .06       0      40      .1       0
     160     .06       0     300      .1       0     310     .06       0
   495.9    .045       0   640.8     .08       0  679.48     .05       0
 1629.48     .08       0 1689.48      .1       0 1739.48     .08       0
 1869.48      .1       0 2271.73     .06       0 2331.73      .1       0
Bank Sta=495.9,640.8
XS Rating Curve= 0 ,0
Exp/Cntr(USF)=0,0
Exp/Cntr=0.3,0.1

Type RM Length L Ch R = 1 ,50331   ,592.6,587.7,585.4
XS GIS Cut Line= 4
 2319057.4454327719264.4792491912319752.85154236718907.504112896
2319910.47692722 718717.426442922320944.31401026717971.023885212
#Sta/Elev= 30
       0 2123.55    79.5 2100.19   108.5 2097.14   182.9 2077.07   232.4 2053.91
   242.2 2045.78   263.9 2043.51   331.3 2012.25   353.8 1997.36   371.8  1996.1
   384.8 1990.93   452.7 1986.72   740.5 1989.51   800.3  1982.5   956.1 1982.41
   966.6 1982.42     977 1989.52  1002.9  1990.4    1152 1987.12  1594.4 1990.22
  1694.7 1985.62  1783.5 1988.58  1800.7 1994.43  1837.9 2015.22  1849.4 2016.39
  1915.3 2045.02  1933.5 2046.11  2141.6 2127.46  2197.5  2160.8  2303.7    2207
#Mann= 10 ,-1,0
       0      .1       0     540     .05       0     560      .1       0
     780    .025       0   800.3    .045       0   966.6    .025       0
 1038.61     .05       0 1548.61      .1       0 1908.61     .06       0
 2028.61      .1       0
Bank Sta=800.3,966.6
XS Rating Curve= 0 ,0
Exp/Cntr(USF)=0,0
Exp/Cntr=0.3,0.1

Type RM Length L Ch R = 1 ,49744   ,950.6,958.1,982
XS GIS Cut Line= 5
2319173.34645098719533.3696115952319729.67133871 719556.54981525
2320248.90790059719232.0269640732320387.98912253719046.585334829
2321217.84041339718499.532528559
#Sta/Elev= 30
       0 2096.65    58.9 2085.71    99.2 2074.96     155 2070.44   295.6 2037.47
   339.1 2017.64   355.1 2012.92   407.2 2005.26   823.9 1983.19  1150.3 1987.62
  1197.7 1980.83  1372.7 1980.98  1379.2 1987.18  1387.8 1988.66  1679.3 1985.44
  1698.2 1983.01  1712.6 1986.51  1741.3  1983.2  1784.4 1984.28  1803.4 1994.13
    1934 2033.03  1956.5 2044.62  1976.1 2045.13  1995.2 2055.71  2057.6 2076.36
  2105.4 2095.89  2119.8 2098.66    2206    2140  2311.9 2185.43  2394.9 2229.42
#Mann= 9 ,-1,0
       0      .1       0     470     .05       0 1146.81      .1       0
  1197.7    .045       0  1372.7     .06       0 1450.92     .05       0
 1680.92      .1       0 1920.92     .06       0 2010.92      .1       0
Bank Sta=1197.7,1372.7
XS Rating Curve= 0 ,0
Exp/Cntr(USF)=0,0
Exp/Cntr=0.3,0.1

Type RM Length L Ch R = 1 ,48785   ,709.4,715.6,672.7
XS GIS Cut Line= 3
2319688.29221841720981.201925155  2320079.662105720764.797399631
2321474.78064188719314.426643461
#Sta/Elev= 30
       0 2167.87     169 2092.71   217.7 2077.38   228.4 2069.55   319.8 2047.98
   356.4 2023.93   406.7 2006.12   434.1 1990.07   443.2 1980.27   517.2 1974.42
   549.2 1979.41   668.7 1978.73   707.5 1976.53  1659.6 1984.69  1686.4 1987.23
  1717.5 1976.94  1795.4 1976.99    1827 1983.61  1952.3 1977.03  2028.9 1977.03
  2048.5 1985.85  2093.8 1987.02  2133.9 2009.37  2158.8 2011.07  2184.3 2020.37
  2212.6 2023.17  2230.9  2033.3  2248.2 2034.33  2348.4 2078.62  2459.7 2135.89
#Mann= 9 ,-1,0
       0      .1       0   668.7     .07       0   707.5     .05       0
  1659.6      .1       0  1717.5    .045       0  1795.4     .08       0
  1952.3    .045       0  2028.9     .06       0  2348.4      .1       0
Bank Sta=1717.5,2028.9
XS Rating Curve= 0 ,0
Exp/Cntr(USF)=0,0
Exp/Cntr=0.3,0.1

Type RM Length L Ch R = 1 ,48070   ,689.7,691.7,694.4
XS GIS Cut Line= 2
2320294.87408553721543.5695541512322001.60809582719722.246510061
#Sta/Elev= 30
       0 2112.94    58.1  2112.6      91 2105.99   135.6 2082.11   165.7 2060.89
   175.2 2051.04   189.4 2047.47   234.7 2015.71     271  1982.1   299.3 1975.58
   359.6 1974.36   441.8 1979.18   529.5 1977.09   661.1 1980.88    1743 1984.83
  1784.9 1981.49  1842.1 1984.07  1862.2  1982.2    1889 1975.06 2026.471975.049
  2031.7 1977.53    2043 1990.67  2051.5 1995.49  2086.4 1999.11  2130.2 2009.89
  2190.5 2018.81  2224.1 2029.29  2243.9 2030.69  2396.7 2094.77    2496 2145.75
#Mann= 9 ,-1,0
       0      .1       0     380     .08       0     510     .05       0
    1770      .1       0    1889    .045       0 2026.47    .025       0
    2060      .1       0    2130     .06       0    2350      .1       0
Bank Sta=1889,2026.47
XS Rating Curve= 0 ,0
Exp/Cntr(USF)=0,0
Exp/Cntr=0.3,0.1