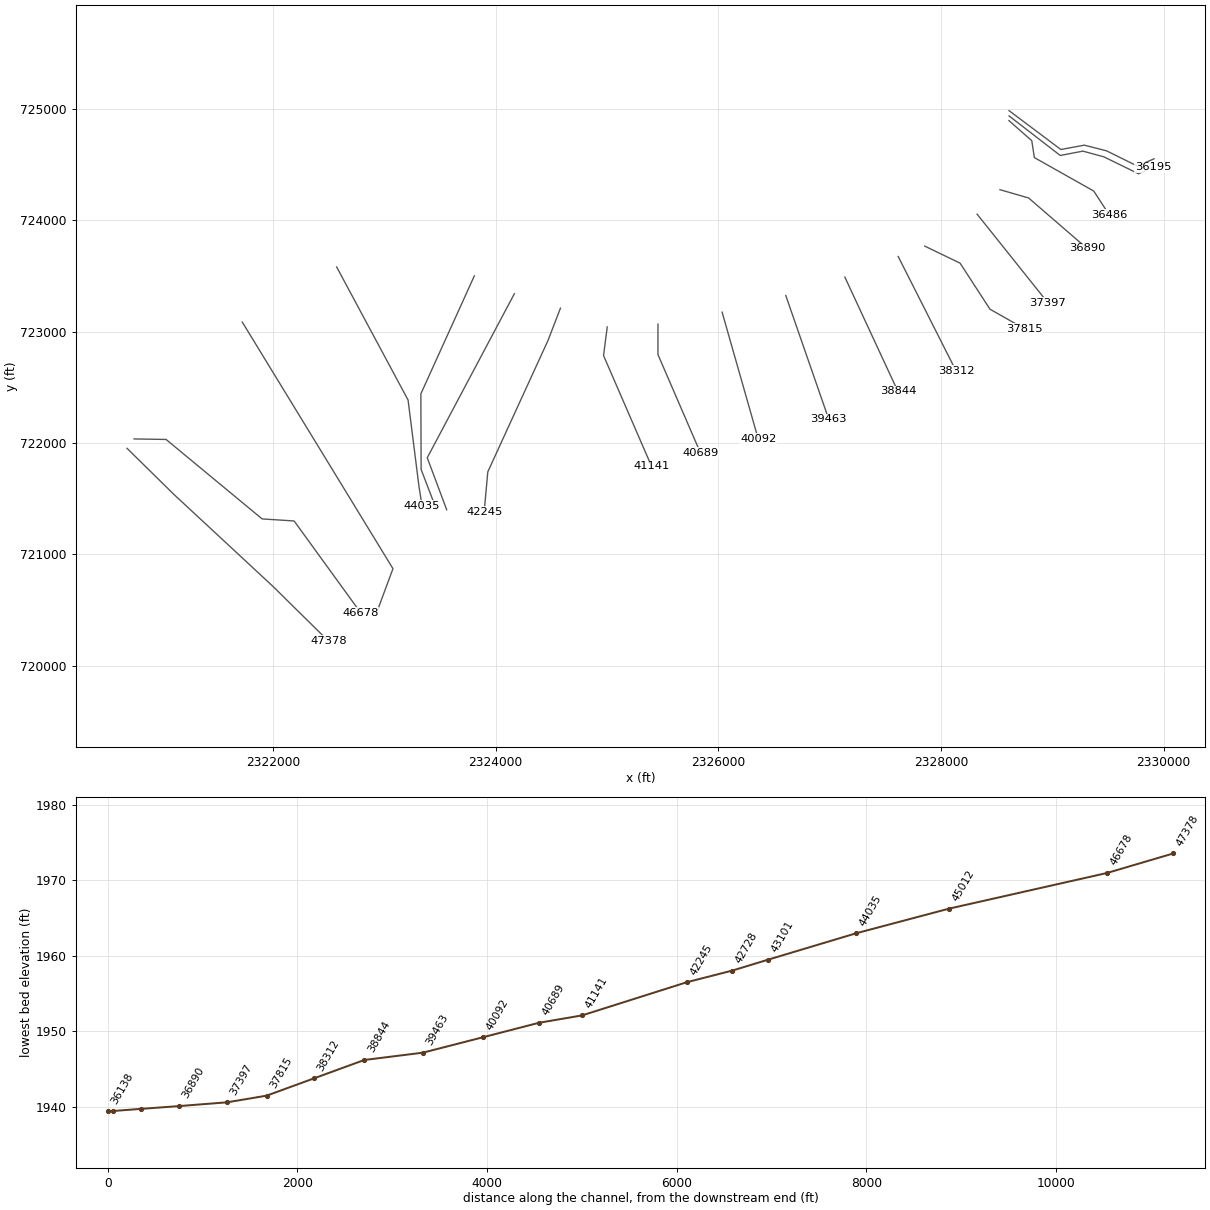
HEC-RAS study SHAVERSFK.prj: SHAVERSFK

--- SHAVERSFK.g01 (geometry) --- (continued)

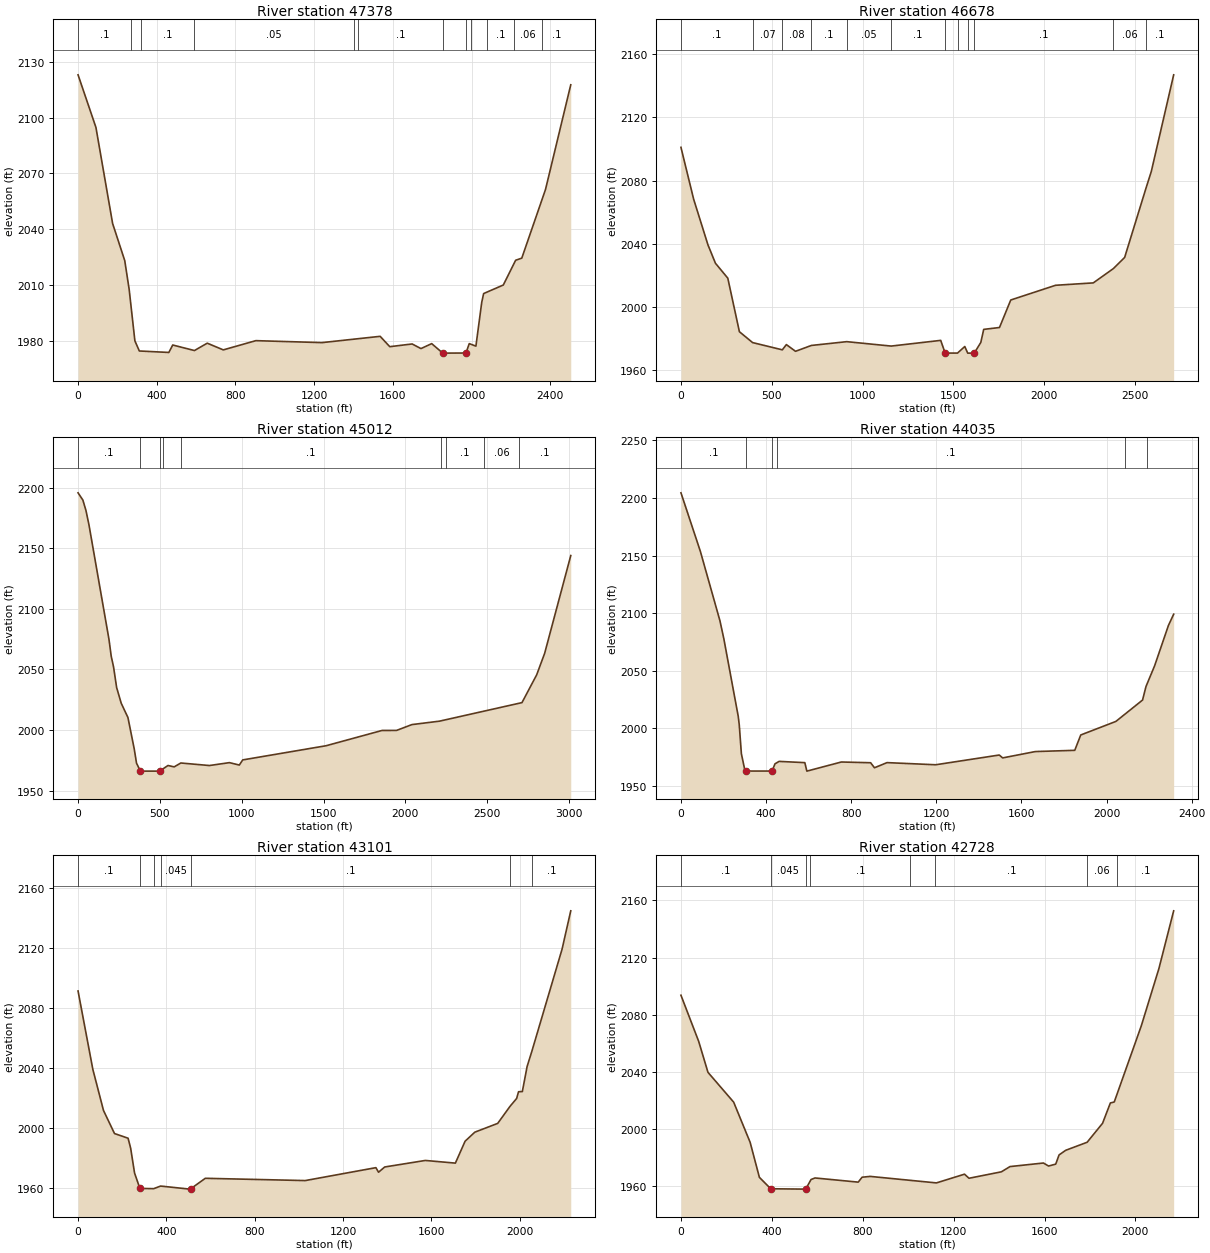
Type RM Length L Ch R = 1 ,47378   ,658.2,700.5,723.8
XS GIS Cut Line= 5
2320690.93381632721952.5041687412321114.45376776721535.984547069
2322003.28514707720710.1377901632322188.16237935720527.398089915
2322499.60994457720220.637420512
#Sta/Elev= 30
       0 2122.97    90.9 2094.74   175.7 2043.14   237.4  2023.2   259.8 2007.78
   288.9 1980.14   311.5 1974.68   461.5 1973.89   481.2 1977.89   591.6 1974.92
   656.7 1978.87   738.3 1975.27   903.7 1980.23  1239.7 1979.17  1535.5 1982.55
  1584.6 1976.99  1698.2 1978.45    1743 1975.97  1797.6 1978.63  1853.9 1973.53
  1971.7 1973.59  1988.5 1978.64  2022.3 1977.28  2051.9 2000.81  2061.6 2005.52
  2161.6 2010.11  2224.3  2023.4  2255.5 2024.54  2376.1 2061.42  2504.4 2117.62
#Mann= 12 ,-1,0
       0      .1       0     270     .07       0     320      .1       0
     590     .05       0 1404.02    .025       0 1424.02      .1       0
  1853.9    .045       0  1971.7      .1       0  1997.3    .025       0
 2077.25      .1       0 2217.25     .06       0 2357.25      .1       0
Bank Sta=1853.9,1971.7
XS Rating Curve= 0 ,0
Exp/Cntr(USF)=0,0
Exp/Cntr=0.3,0.1

Type RM Length L Ch R = 1 ,46678   ,1729.4,1666,1619
XS GIS Cut Line= 5
2320754.23634028722036.8316063922321041.67086561722032.195565661
 2321903.9744416 721318.245293072322191.40896692721299.701130146
2322789.45822124720474.485880009
#Sta/Elev= 30
       0 2101.07    69.9 2068.28   148.7 2039.41     190 2027.78     258 2018.35
   321.9 1984.49   394.6 1977.61   558.4 1973.02   580.7 1976.34   630.9 1972.09
   718.7  1975.8   913.1 1978.19    1158  1975.4  1430.8    1979  1455.3 1970.97
  1523.4 1970.97  1563.5 1975.13  1579.5 1970.94  1615.6 1970.94  1651.7  1977.7
  1667.7 1985.96  1754.6 1987.14  1816.7 2004.54  2063.7 2013.85  2271.2 2015.35
  2381.9  2024.4  2444.1 2031.46  2562.4 2075.54    2591 2085.85  2714.1 2146.94
#Mann= 12 ,-1,0
       0      .1       0   394.6     .07       0   558.4     .08       0
   718.7      .1       0   913.1     .05       0    1158      .1       0
  1455.3    .045       0  1523.4     .08       0  1579.5    .045       0
  1615.6      .1       0  2381.9     .06       0  2562.4      .1       0
Bank Sta=1455.3,1615.6
XS Rating Curve= 0 ,0
Exp/Cntr(USF)=0,0
Exp/Cntr=0.3,0.1

Type RM Length L Ch R = 1 ,45012   ,979.5,977,973
XS GIS Cut Line= 3
2321726.25190924723086.3621276922323078.95055478720871.024395553
2322934.61794496720481.662006268
#Sta/Elev= 30
       0 2195.61    29.5 2189.65    48.3 2181.08      67 2169.03   188.9  2074.9
   202.9 2060.78     217 2052.12   235.7 2035.16   263.8 2022.19   304.9 2010.39
   343.5 1984.42   357.3  1972.8     381 1966.24   498.2 1966.22   549.7 1970.86
   587.5 1969.73   627.9 1972.92   802.8 1970.83   924.8 1973.22   985.6 1971.23
  1006.2 1975.46  1515.8 1987.15  1857.3 1999.73  1946.4 1999.78  2040.1 2004.57
  2208.8 2007.41  2712.8 2022.69  2802.4 2045.54  2851.4 2063.33  3010.9 2143.89
#Mann= 9 ,-1,0
       0      .1       0     381    .045       0   498.2      .1       0
     520     .08       0     630      .1       0    2220     .06       0
    2250      .1       0    2480     .06       0 2695.67      .1       0
Bank Sta=381,498.2
XS Rating Curve= 0 ,0
Exp/Cntr(USF)=0,0
Exp/Cntr=0.3,0.1

Type RM Length L Ch R = 1 ,44035   ,1013.4,933.3,878.7
XS GIS Cut Line= 4
2322573.13202477723582.5455662082323214.55270057722386.524614853
2323312.55731743721609.4880097172323340.05853267721436.855461509
#Sta/Elev= 30
       0 2204.44    91.1  2153.7   183.1 2093.48   201.3    2078   269.2 2010.43
   273.9 2003.14   283.9 1978.05   298.7 1965.13   305.7 1963.05   428.2 1963.03
   441.8  1969.3   461.2 1971.42     582 1970.33   591.6 1962.97   753.7 1970.89
   891.2 1970.25   909.3 1965.89   968.3 1970.35  1196.9 1968.49  1495.6 1976.94
  1511.7 1974.44  1664.9 1979.94  1850.4 1981.02  1878.6 1994.34  2043.6 2006.09
    2169 2024.64  2185.2 2036.43  2225.7 2054.38  2290.5 2089.32  2315.2 2099.11
#Mann= 6 ,-1,0
       0      .1       0   305.7    .045       0   428.2    .025       0
     450      .1       0 2087.16     .06       0 2190.35      .1       0
Bank Sta=305.7,428.2
XS Rating Curve= 0 ,0
Exp/Cntr(USF)=0,0
Exp/Cntr=0.3,0.1

Type RM Length L Ch R = 1 ,43101   ,389.4,373.8,363.5
XS GIS Cut Line= 5
2323809.67634915723502.2414383162323329.35084995722441.900241979
2323331.92481775721762.0597354432323448.22721761721458.851765407
2323470.98697177721400.532096439
#Sta/Elev= 30
       0 2091.36      67 2039.18   115.3  2011.8   165.1 1996.46   226.6 1993.35
   238.3 1986.66   255.9 1970.18     280 1959.92   342.9 1959.78   373.7  1961.5
   506.2 1959.46   510.6 1959.73   576.4 1966.67  1028.7 1965.15  1348.8 1973.75
  1360.8 1970.72  1388.8  1974.2  1572.8 1978.55  1708.8 1976.77  1752.8 1991.36
  1796.8 1997.37  1900.5 2003.22  1956.3 2014.58  1986.2  2019.8  1994.8 2024.29
    2012 2024.39  2033.7 2041.13  2054.8 2051.04  2191.9 2119.16  2231.3 2144.71
#Mann= 7 ,-1,0
       0      .1       0     280    .045       0   342.9     .08       0
   373.7    .045       0   510.6      .1       0  1956.3     .06       0
  2054.8      .1       0
Bank Sta=280,510.6
XS Rating Curve= 0 ,0
Exp/Cntr(USF)=0,0
Exp/Cntr=0.3,0.1

Type RM Length L Ch R = 1 ,42728   ,481.4,482.2,487.1
XS GIS Cut Line= 3
2324169.16524477723342.1329385842323386.74823665721867.926375016
2323561.48740428721400.158443727
#Sta/Elev= 30
       0 2093.62    78.1 2061.32   118.8 2039.72     232 2018.85   304.5 1990.72
   345.2 1966.26   395.1 1958.28     549 1958.03   572.4 1964.73   589.8 1965.84
     780 1962.92   797.2 1966.36   832.7 1966.93  1124.1 1962.38  1247.8 1968.48
  1267.6 1965.63    1410 1970.13  1448.1  1973.8  1595.1 1976.29  1617.7 1974.18
  1649.2 1975.52    1664 1981.95  1693.3 1985.19  1787.4  1990.8  1855.3 2004.05
  1889.7 2018.28  1906.8 2018.98  2025.7 2072.16  2103.2  2112.2  2168.3 2152.66
#Mann= 8 ,-1,0
       0      .1       0   395.1    .045       0     549    .025       0
     570      .1       0    1010     .07       0    1120      .1       0
 1788.97     .06       0 1918.97      .1       0
Bank Sta=395.1,549
XS Rating Curve= 0 ,0
Exp/Cntr(USF)=0,0
Exp/Cntr=0.3,0.1

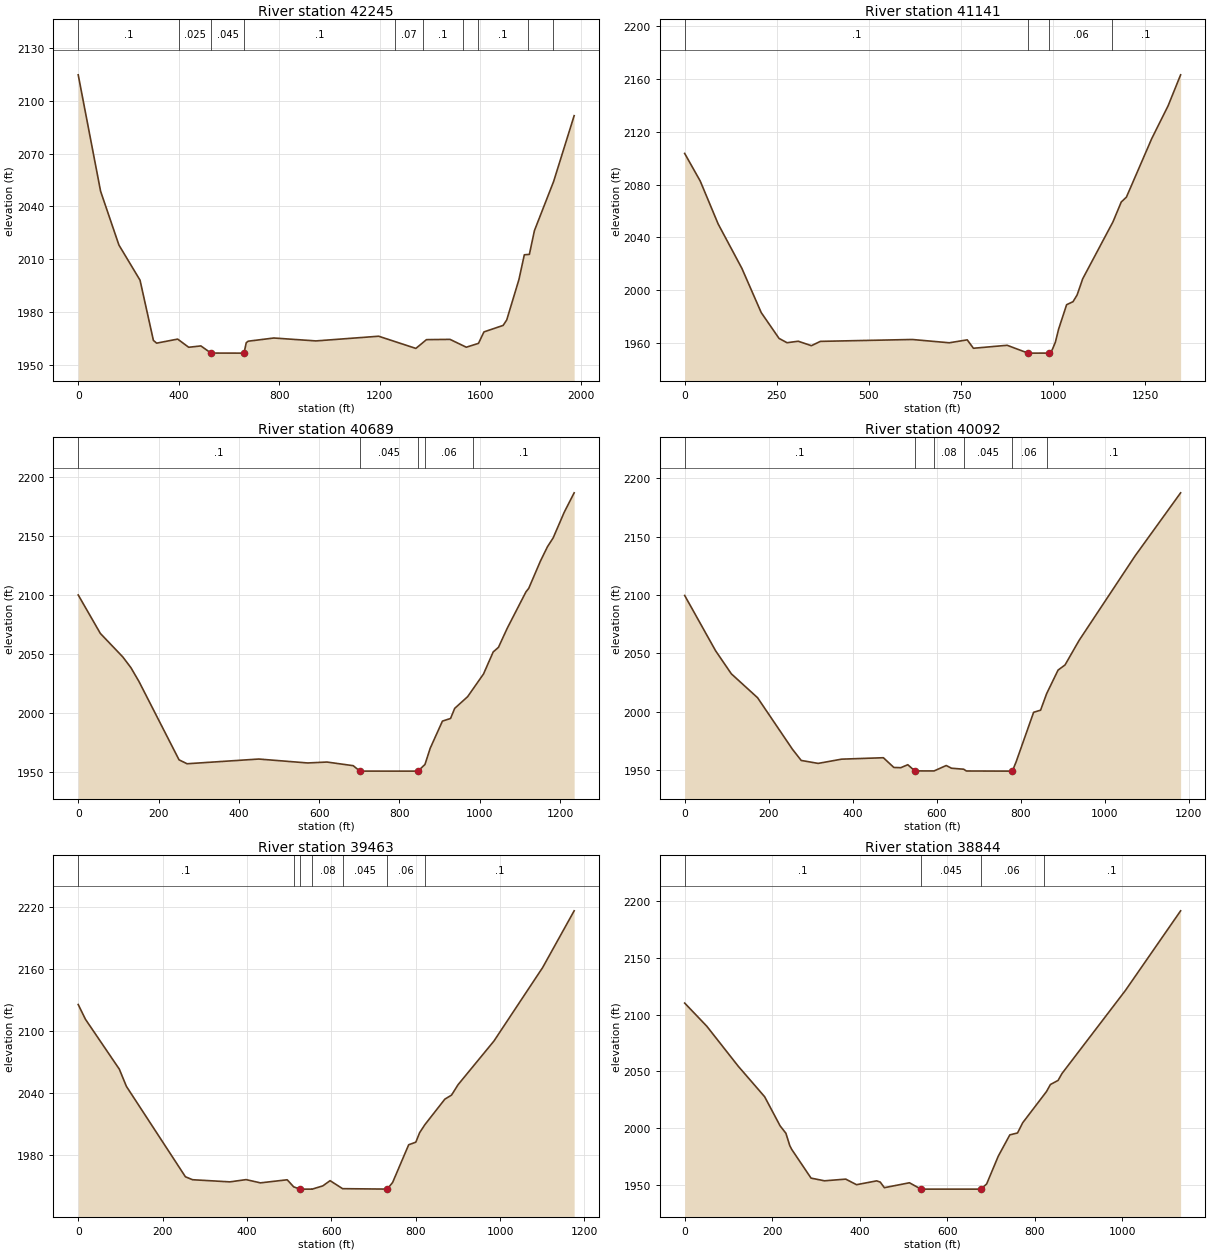
Type RM Length L Ch R = 1 ,42245   ,1092,1104.6,1121.8
XS GIS Cut Line= 4
  2324583.030612723212.233589745 2324471.2567537722922.225741174
2323930.51295272721741.0479412662323897.59059072721379.861040615
#Sta/Elev= 30
       0 2114.94      89 2048.67   161.9 2018.04   245.9 1998.02   299.1 1963.72
     312 1962.16   395.5 1964.47   439.5 1959.82   487.9 1960.58   528.2 1956.51
   659.5 1956.48   668.3 1962.39     676 1963.27   778.3 1965.09   945.4 1963.43
  1195.1  1966.1    1343 1959.16  1385.2 1964.16  1478.8 1964.31  1543.7 1959.85
  1592.1 1962.04  1613.8 1968.56  1690.1 1972.26  1704.4 1975.36    1753 1998.39
  1774.4 2012.47  1794.5 2012.71  1814.6 2026.23  1890.9  2054.2  1972.6 2091.67
#Mann= 10 ,-1,0
       0      .1       0   400.8    .025       0   528.2    .045       0
   659.5      .1       0  1260.8     .07       0  1370.8      .1       0
  1530.8     .07       0  1590.8      .1       0 1789.87     .06       0
 1889.87      .1       0
Bank Sta=528.2,659.5
XS Rating Curve= 0 ,0
Exp/Cntr(USF)=0,0
Exp/Cntr=0.3,0.1

Type RM Length L Ch R = 1 ,41141   ,455.7,451.8,452.4
XS GIS Cut Line= 3
2325002.93780942723043.0623447452324969.70774343722786.284562156
 2325401.6986012721789.382582694
#Sta/Elev= 30
       0 2103.63    42.2 2082.68    90.6 2050.24   155.2  2016.4   207.6 1982.89
     256 1963.26   277.6    1960   308.1 1961.11   343.8 1957.74   368.1 1961.01
   617.2 1962.44   717.8 1959.94   766.5 1962.17   783.3 1955.78   874.8 1958.04
   931.5 1952.09   988.5 1952.11   996.9  1954.5  1005.6 1960.37  1014.3 1970.18
  1036.1 1988.82  1053.5 1991.14  1064.6 1996.22  1079.7 2008.45  1161.9 2051.73
  1184.3 2066.75  1198.4  2070.5  1267.1 2114.92  1311.4 2139.75  1345.4 2163.29
#Mann= 4 ,-1,0
       0      .1       0   931.5    .045       0   988.5     .06       0
 1158.92      .1       0
Bank Sta=931.5,988.5
XS Rating Curve= 0 ,0
Exp/Cntr(USF)=0,0
Exp/Cntr=0.3,0.1

Type RM Length L Ch R = 1 ,40689   ,609.6,596.4,585.1
XS GIS Cut Line= 3
2325458.44756697723068.2779332142325458.44756697722794.779447765
2325839.68788002721912.125244725
#Sta/Elev= 30
       0 2100.07    55.1 2067.55   111.1 2047.63   131.1 2038.65   151.1 2027.03
   251.1 1960.67   271.1 1957.35   449.5 1961.34   571.5 1958.02   619.5  1958.8
   684.8 1955.72   701.5 1951.14     846 1951.12   863.5 1956.75   876.5 1970.43
     907 1993.41   927.2 1995.64   937.5 2004.16   969.8 2014.09  1009.4 2033.32
  1033.4 2051.88  1046.5 2055.77  1068.2  2071.8  1115.1 2102.75  1121.9 2105.64
    1151 2128.69  1168.5 2140.81  1182.8 2148.36  1210.2 2169.94    1235 2186.41
#Mann= 5 ,-1,0
       0      .1       0   701.5    .045       0     846    .025       0
   863.5     .06       0   983.5      .1       0
Bank Sta=701.5,846
XS Rating Curve= 0 ,0
Exp/Cntr(USF)=0,0
Exp/Cntr=0.3,0.1

Type RM Length L Ch R = 1 ,40092   ,620.8,629.7,633.6
XS GIS Cut Line= 2
2326034.45195299723176.0197608152326357.67743579722040.586654557
#Sta/Elev= 30
       0 2099.73    73.7 2052.27   111.1 2032.56   173.5  2012.1   256.6 1967.89
   277.4 1958.35   317.7 1955.81   373.7 1959.45   472.9 1960.67   497.9 1952.33
   514.5 1952.14   531.1 1954.68   547.8 1949.38   593.5 1949.34   622.6 1953.99
   635.1 1951.68   664.1 1950.83   670.6  1949.3   776.5 1949.19  778.021949.379
   780.7 1949.84     789 1957.17   830.6 1999.62   847.2 2001.42   861.6 2015.59
   888.8 2035.76   905.4 2040.19   938.7 2061.13  1071.8 2133.46  1180.5 2187.68
#Mann= 6 ,-1,0
       0      .1       0   547.8    .045       0   593.5     .08       0
   664.1    .045       0  778.02     .06       0   861.6      .1       0
Bank Sta=547.8,778.02
XS Rating Curve= 0 ,0
Exp/Cntr(USF)=0,0
Exp/Cntr=0.3,0.1

Type RM Length L Ch R = 1 ,39463   ,610.3,618.9,624.6
XS GIS Cut Line= 2
2326606.31242256723325.2007528792326991.69665206722214.631145297
#Sta/Elev= 30
       0 2125.97    17.2 2111.64    97.4 2063.38   114.3 2046.63   254.1 1959.13
     271 1956.27   359.5 1954.19     398 1956.37   431.9 1953.23   495.4 1956.21
   510.7 1949.37     525 1947.25   529.3 1947.16   554.7 1947.16   554.7 1947.18
   579.8  1950.3     597 1955.36   626.7  1947.6   732.5 1947.19   745.2  1953.6
   783.3 1990.12   800.2 1992.64   809.3 2001.85   821.4 2009.43     869 2034.29
   884.9 2038.25   900.4 2048.33   985.3 2090.55  1100.9 2161.83  1175.5 2216.71
#Mann= 7 ,-1,0
       0      .1       0   510.7    .025       0     525    .045       0
   554.7     .08       0   626.7    .045       0   732.5     .06       0
   821.4      .1       0
Bank Sta=525,732.5
XS Rating Curve= 0 ,0
Exp/Cntr(USF)=0,0
Exp/Cntr=0.3,0.1

Type RM Length L Ch R = 1 ,38844   ,531.7,532.1,534.2
XS GIS Cut Line= 2
2327136.73372768723490.9574107262327613.28411899722463.266132069
#Sta/Elev= 30
       0 2110.33    50.5 2089.93   122.3 2054.65   182.7 2027.68     218    2002
   231.2 1995.48   240.1 1984.53   244.5 1981.25   288.6 1955.91   319.4 1953.53
   367.9 1955.01   392.5  1950.1   438.5 1953.48   446.7  1952.4   456.1 1947.46
   513.4  1951.8   539.2 1946.28   539.9 1946.19   676.6 1946.19   689.8  1950.8
   716.2 1975.19   742.7 1994.06   760.3 1995.74   772.1 2004.74   826.5  2032.3
   835.4 2038.49   852.9  2042.1   861.7 2048.12  1006.6 2121.42  1132.8 2191.72
#Mann= 4 ,-1,0
       0      .1       0   539.2    .045       0   676.6     .06       0
     820      .1       0
Bank Sta=539.2,676.6
XS Rating Curve= 0 ,0
Exp/Cntr(USF)=0,0
Exp/Cntr=0.3,0.1

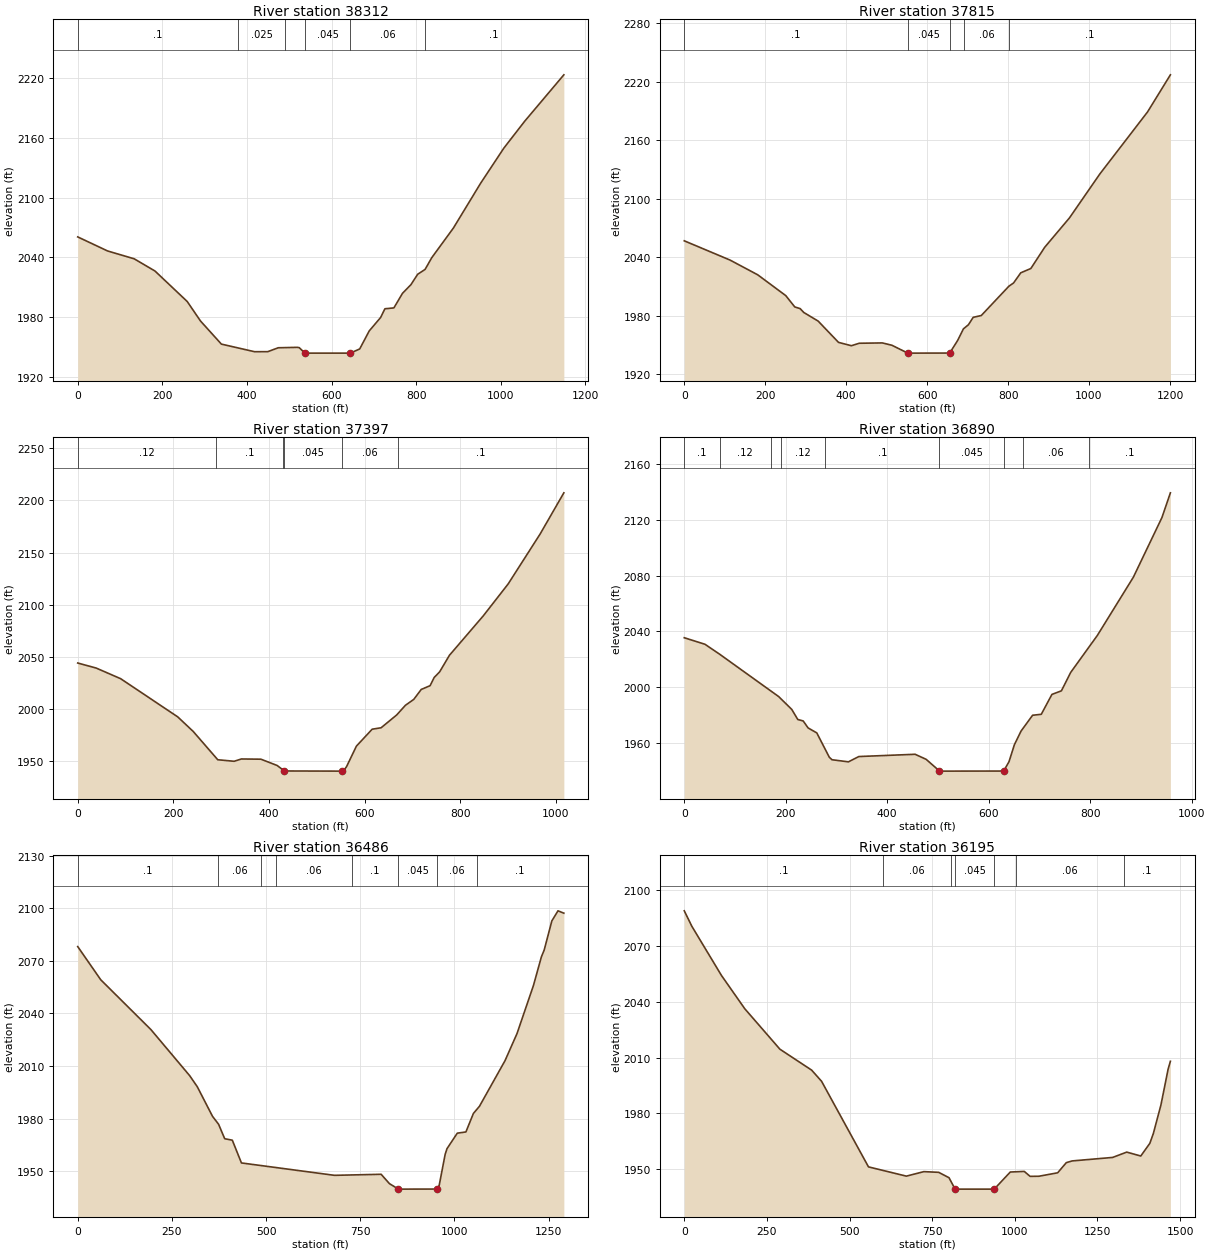
Type RM Length L Ch R = 1 ,38312   ,492.9,497.3,504.2
XS GIS Cut Line= 2
2327615.56693221723676.2187547032328133.97087963722650.599434269
#Sta/Elev= 30
       0 2060.47    70.6 2046.35   133.4 2038.49   182.7 2026.19   258.9 1995.58
   290.2 1976.05   339.6 1952.81   418.1 1945.17   449.3 1945.22     474 1949.13
   518.8 1949.56   523.7 1949.24   536.8 1943.83   541.2 1943.75   644.3 1943.75
   666.6 1947.94   689.1 1966.05     716  1979.5   726.2  1988.3   747.4 1989.17
   767.8 2003.83   787.7  2012.5   803.6 2022.93   821.2 2027.84     837 2039.64
   888.1 2069.37   952.4 2114.33  1007.4 2149.66  1056.5 2176.57  1149.2 2223.24
#Mann= 6 ,-1,0
       0      .1       0     380    .025       0     490      .1       0
   536.8    .045       0   644.3     .06       0     820      .1       0
Bank Sta=536.8,644.3
XS Rating Curve= 0 ,0
Exp/Cntr(USF)=0,0
Exp/Cntr=0.3,0.1

Type RM Length L Ch R = 1 ,37815   ,414,417.3,423.8
XS GIS Cut Line= 4
2327854.25651951723769.4568747422328171.26612765723616.546357877
2328439.79191336723202.5691049022328749.34247189723027.281439228
#Sta/Elev= 30
       0 2056.72   113.2 2036.94   181.4 2021.86   250.8 2000.48     273 1988.87
   286.3 1987.14   295.2 1983.22   330.8 1974.34   381.1  1952.5   412.9 1949.06
   432.3  1951.6   489.5 1951.94   513.3 1949.51   551.7 1941.57   557.5 1941.47
   655.8 1941.54   675.4 1954.43   689.7 1966.38   702.1  1970.6   713.8 1978.19
   733.9 1980.08     802 2010.11   813.7 2013.52   831.4 2023.89   856.3 2028.32
   890.7 2050.18   951.6 2080.17  1026.8 2125.34  1144.6 2188.96  1201.1 2227.05
#Mann= 5 ,-1,0
       0      .1       0   551.7    .045       0   655.8      .1       0
  691.96     .06       0  801.96      .1       0
Bank Sta=551.7,655.8
XS Rating Curve= 0 ,0
Exp/Cntr(USF)=0,0
Exp/Cntr=0.3,0.1

Type RM Length L Ch R = 1 ,37397   ,496.2,507.1,519.2
XS GIS Cut Line= 2
2328324.17664451724056.6302844642328958.19586078723262.241501727
#Sta/Elev= 30
       0 2044.14    38.5 2039.34    89.8 2029.13   209.1 1992.56   241.5 1978.59
   292.8 1951.49     327 1950.03   342.2 1952.23   383.1 1952.02   416.8 1946.02
   432.2 1940.74   551.5 1940.59   551.8  1940.6   557.5 1941.88   562.3  1945.1
   582.7 1964.55   615.6 1980.74   634.3 1982.12   666.9  1994.4   685.1 2003.63
   702.6  2009.3   718.2 2018.82   736.8 2022.46   745.3 2030.29   756.7 2035.67
   777.2 2051.56   847.8 2089.24     900 2119.92   966.6 2167.57  1016.4 2207.17
#Mann= 6 ,-1,0
       0     .12       0     290      .1       0     430    .025       0
   432.2    .045       0   551.8     .06       0     670      .1       0
Bank Sta=432.2,551.8
XS Rating Curve= 0 ,0
Exp/Cntr(USF)=0,0
Exp/Cntr=0.3,0.1

Type RM Length L Ch R = 1 ,36890   ,393.3,404.2,415.7
XS GIS Cut Line= 3
 2328529.3005086724276.6722477572328786.63771991724202.081751725
2329308.77119213723750.809250734
#Sta/Elev= 30
       0  2035.5    40.7 2030.85      70 2023.65     186 1993.43   211.8 1984.25
   223.7 1977.03   234.4 1975.97   244.1 1970.98   261.2 1967.43   285.8 1950.06
   291.1 1948.24   323.5 1946.73     344 1950.52     455 1952.14   476.7 1948.53
   502.6 1940.31   507.8 1940.09   629.5 1940.15     640 1946.83   650.6 1958.96
   663.7 1968.71   686.5 1980.06   703.6 1980.73   724.6 1994.96   743.3 1997.53
   761.6  2010.7   814.2 2037.19   885.1 2078.81   941.4 2121.46   958.1 2139.16
#Mann= 9 ,-1,0
       0      .1       0      70     .12       0     170      .1       0
     190     .12       0  277.93      .1       0   502.6    .045       0
   629.5      .1       0  667.93     .06       0  797.93      .1       0
Bank Sta=502.6,629.5
XS Rating Curve= 0 ,0
Exp/Cntr(USF)=0,0
Exp/Cntr=0.3,0.1

Type RM Length L Ch R = 1 ,36486   ,277.9,291.4,304.8
BEGIN DESCRIPTION:
Structure XS 4
END DESCRIPTION:
XS GIS Cut Line= 5
 2328609.9612325724897.3147091782328815.13622627724716.702918883
2328838.25453543724564.9890150342329371.42054038724264.450995982
2329508.68550101724053.496424917
#Sta/Elev= 30
       0 2078.13    61.2 2059.18   194.4 2030.74   297.1  2004.5   317.4 1998.16
   357.8 1981.28     374 1976.72   390.2 1968.48   410.4 1967.65   434.6 1954.66
   681.6 1947.59   805.5 1948.19   827.4 1942.86   851.5 1939.72   953.7 1939.76
   959.6 1941.89   975.4 1959.57   980.3 1962.81  1007.6 1971.65  1030.5 1972.36
  1050.4 1982.91  1066.6 1987.04  1134.3 2013.02  1166.1 2028.46  1209.8 2055.94
  1230.9 2072.29  1238.3 2076.15  1258.6 2092.77  1274.9 2098.54  1290.5 2097.21
#Mann= 8 ,-1,0
       0      .1       0  373.34     .06       0  486.81      .1       0
  526.81     .06       0  726.81      .1       0   851.5    .045       0
   953.7     .06       0 1058.85      .1       0
Bank Sta=851.5,953.7
XS Rating Curve= 0 ,0
Exp/Cntr(USF)=0,0
Exp/Cntr=0.3,0.1

Type RM Length L Ch R = 1 ,36195   ,55.6,56.5,57.9
BEGIN DESCRIPTION:
Structure XS 3
END DESCRIPTION:
XS GIS Cut Line= 6
2328611.29205042 724939.299791592329070.78036154724583.979236473
2329273.87648299 724623.130296032329462.29095711724571.744530361
2329773.05249234724420.0341745772329902.43644255724476.989374223
#Sta/Elev= 30
       0 2088.69    23.1 2080.35   112.4 2054.06   183.1 2036.17   289.3 2014.49
   385.4 2003.25   415.4 1997.27   557.3 1951.37   671.9 1946.41   724.8 1948.82
   769.7 1948.45   800.9 1945.56   819.1 1939.51   823.7 1939.44   937.7 1939.44
   986.3 1948.61  1028.6 1948.94  1046.3 1946.29  1072.6 1946.34  1129.6 1948.19
  1155.8 1953.64  1173.3 1954.56    1296 1956.44  1338.6 1959.29  1381.1  1957.2
  1408.4 1963.98  1419.1 1969.26    1442 1984.54  1463.8 2003.78  1470.7    2008
#Mann= 7 ,-1,0
       0      .1       0  600.85     .06       0  807.68    .025       0
   819.1    .045       0   937.7      .1       0 1002.98     .06       0
 1329.32      .1       0
Bank Sta=819.1,937.7
XS Rating Curve= 0 ,0
Exp/Cntr(USF)=0,0
Exp/Cntr=0.3,0.1

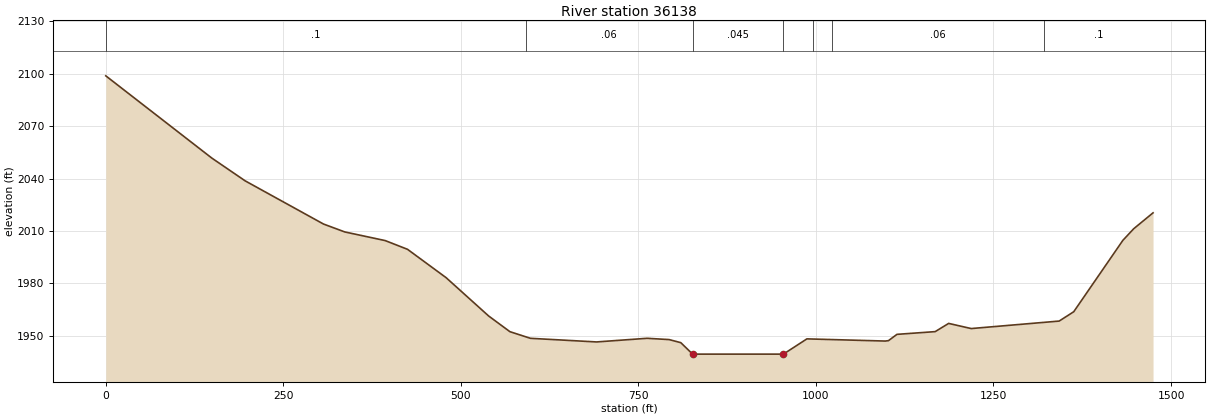
Type RM Length L Ch R = 1 ,36138   ,225.3,237.2,251.2
BEGIN DESCRIPTION:
Structure XS 2
END DESCRIPTION:
XS GIS Cut Line= 6
2328610.96555505724986.8162825122329076.23344346724637.601800051
2329286.67038858724676.7528596082329487.31956881 724625.36709394
2329763.82392693 724488.338385492329913.08734149724554.405798493
#Sta/Elev= 30
       0 2098.86   149.3 2051.74   196.3 2038.68   306.6 2013.94   336.6 2009.41
   393.4 2004.47   424.9 1999.46   479.2 1983.23   539.1 1961.27   569.1 1952.27
     598 1948.47   691.1 1946.39   762.1 1948.48   793.3 1947.74   809.7 1945.98
   826.2 1939.47   830.4 1939.41   954.2 1939.41   987.3 1948.15  1097.6  1946.9
  1102.1 1947.12  1114.1 1950.74  1167.9  1952.3  1186.9 1957.01  1218.6 1954.06
  1342.5 1958.35    1363 1963.69  1432.2 2004.59  1447.5 2011.26  1474.7 2020.36
#Mann= 7 ,-1,0
       0      .1       0  591.74     .06       0   826.2    .045       0
   954.2     .06       0  995.79      .1       0 1022.92     .06       0
 1321.51      .1       0
Bank Sta=826.2,954.2
XS Rating Curve= 0 ,0
Exp/Cntr(USF)=0,0
Exp/Cntr=0.3,0.1