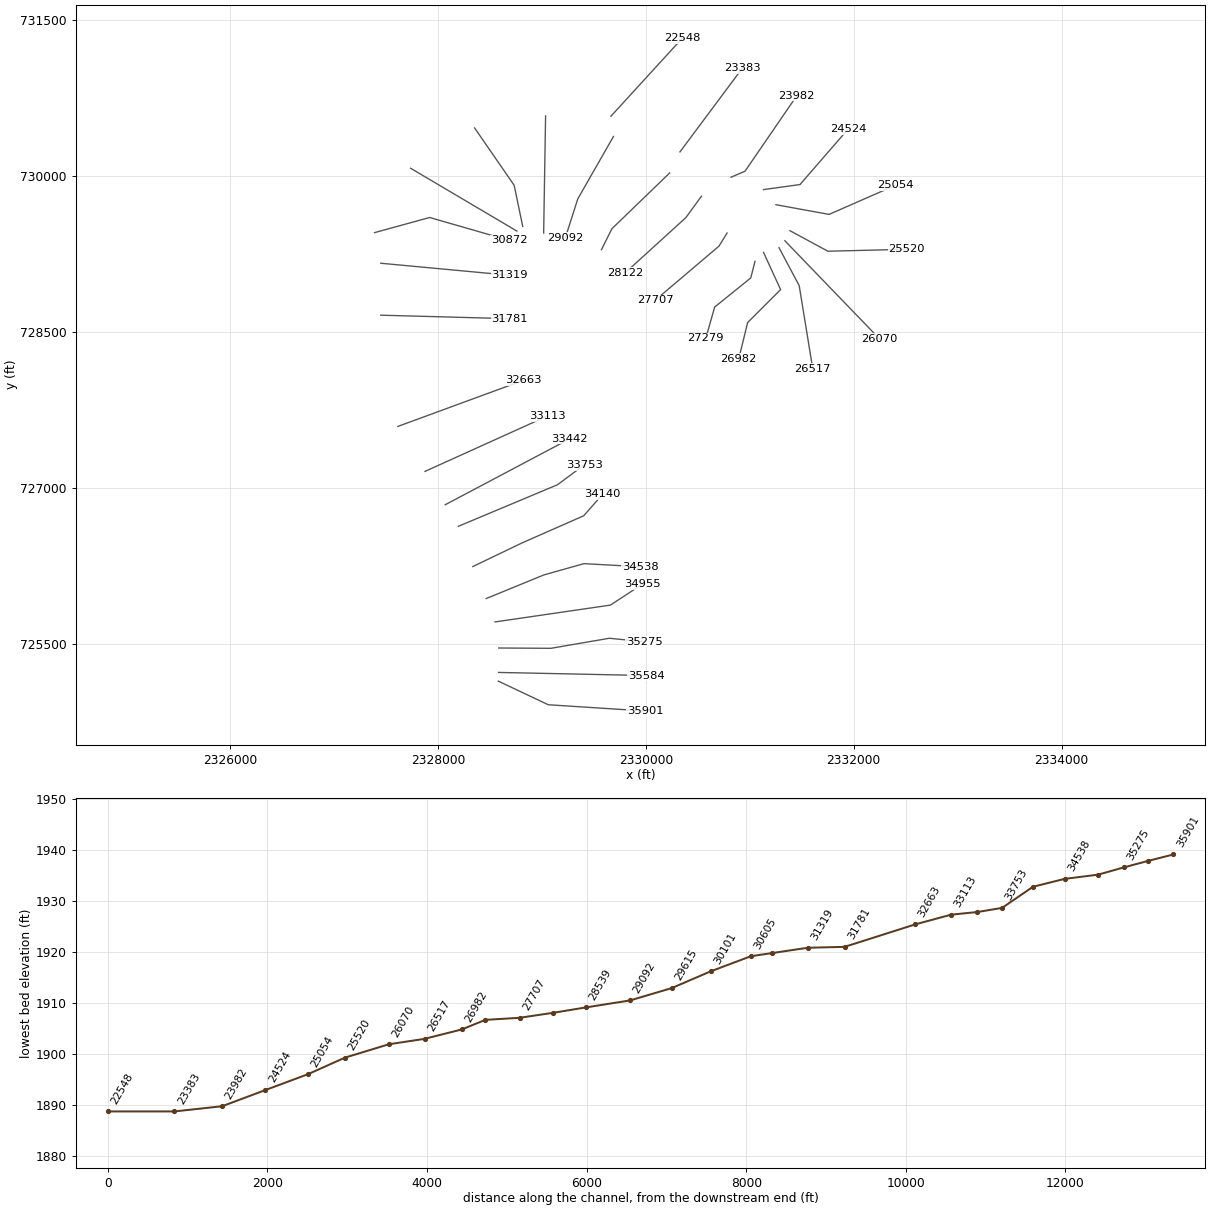
HEC-RAS study SHAVERSFK.prj: SHAVERSFK

--- SHAVERSFK.g01 (geometry) --- (continued)

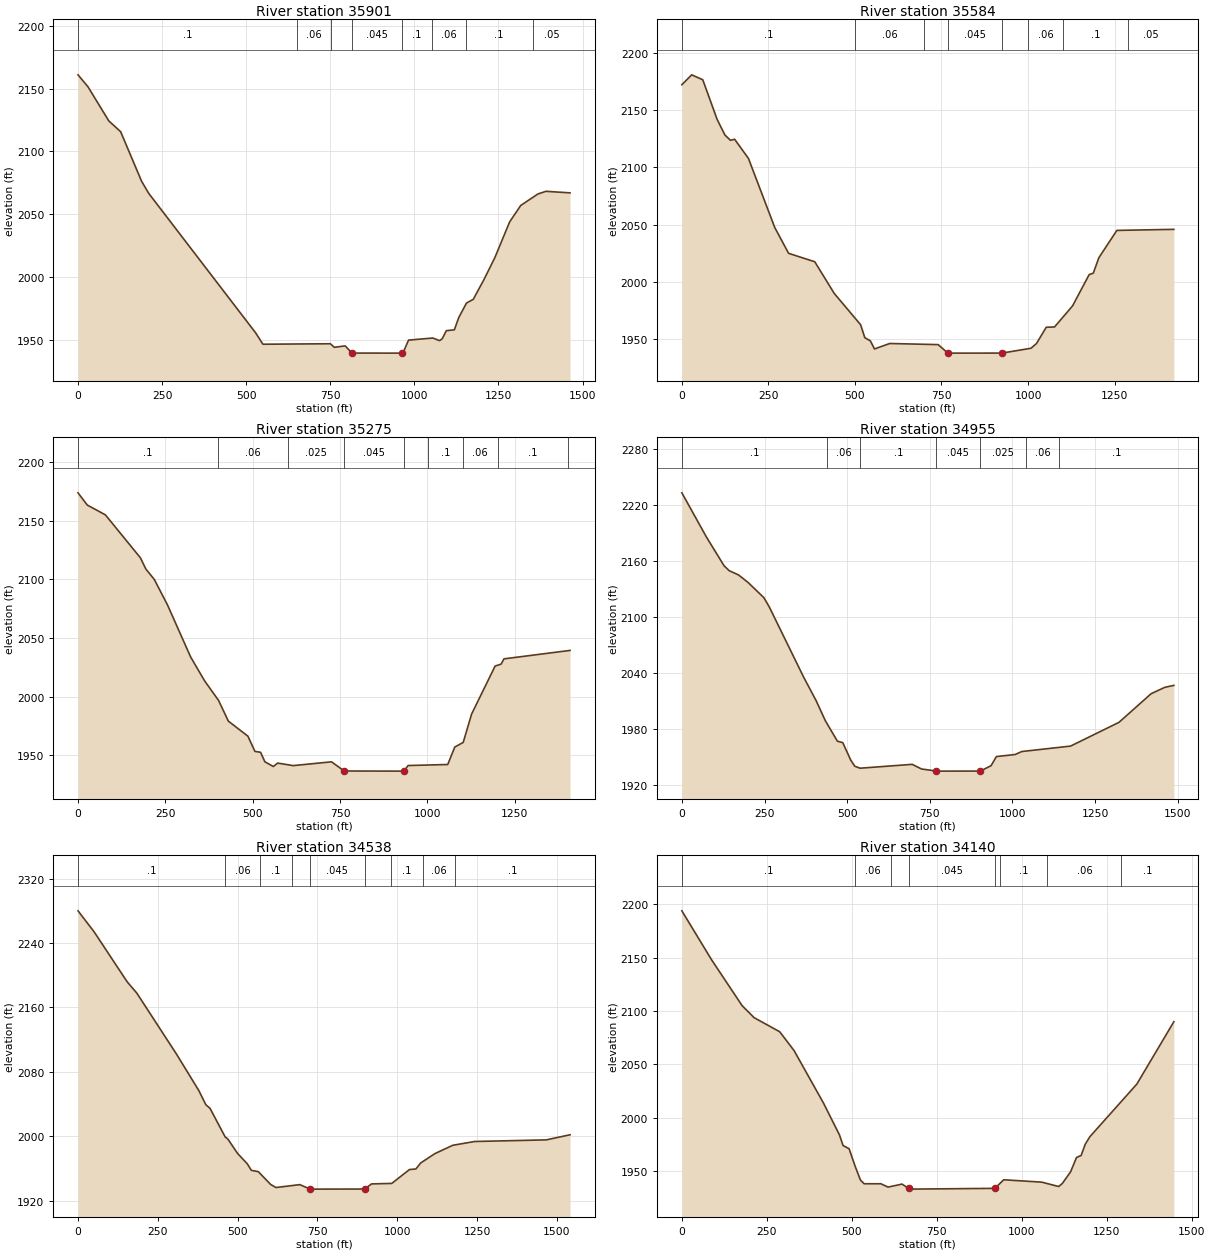
Type RM Length L Ch R = 1 ,35901   ,313.2,316.5,319.7
BEGIN DESCRIPTION:
Structure XS 1
END DESCRIPTION:
XS GIS Cut Line= 3
2328581.51385582725138.1924769212329062.62255522724910.691464025
2329991.27423082  724851.0190672
#Sta/Elev= 30
       0 2160.93    29.5 2151.47    91.4 2124.26   126.8 2115.58     189 2076.14
     210 2066.56   528.5 1955.18   549.8 1946.25   750.2 1946.63   762.2 1943.78
   794.3 1944.93   814.3  1939.2   962.6 1939.16   966.6  1939.6   982.7 1949.53
  1054.8 1951.19  1074.9 1949.12  1082.9 1950.61  1094.9 1957.05  1118.9 1957.74
  1131.9 1967.45    1155 1979.08  1175.1 1982.02  1207.1 1997.84  1239.4 2015.33
  1283.3 2043.72  1316.1 2056.79  1367.5 2066.01  1391.5 2068.11  1462.8 2066.87
#Mann= 8 ,-1,0
       0      .1       0  652.19     .06       0  752.19    .025       0
   814.3    .045       0   962.6      .1       0 1052.19     .06       0
 1152.19      .1       0 1352.19     .05       0
Bank Sta=814.3,962.6
XS Rating Curve= 0 ,0
Exp/Cntr(USF)=0,0
Exp/Cntr=0.3,0.1

Type RM Length L Ch R = 1 ,35584   ,292.5,308.9,324.7
XS GIS Cut Line= 2
 2328583.8261612725221.771127725 2330004.7751106725191.934929312
#Sta/Elev= 30
       0 2172.11    28.4 2180.75    60.4 2176.44   101.9 2141.86   124.4 2128.22
   140.4 2123.61   152.4 2124.55   192.4 2107.78   268.4 2047.49   308.4 2024.98
   383.9 2017.65   440.4 1989.92   516.5 1962.66   528.5 1951.37   544.5 1948.63
   556.5 1941.55   600.5 1946.31   740.5 1945.34   768.5 1937.91   924.6 1937.94
  1008.6 1942.17  1024.6 1946.34  1052.6 1960.46  1076.6 1960.75  1128.6  1979.1
  1176.6 2006.41  1188.6  2007.7  1204.6 2021.15  1256.6 2044.99  1421.3 2045.92
#Mann= 8 ,-1,0
       0      .1       0     500     .06       0     700    .025       0
   768.5    .045       0   924.6    .025       0    1000     .06       0
    1100      .1       0    1290     .05       0
Bank Sta=768.5,924.6
XS Rating Curve= 0 ,0
Exp/Cntr(USF)=0,0
Exp/Cntr=0.3,0.1

Type RM Length L Ch R = 1 ,35275   ,322.8,320.6,318.8
XS GIS Cut Line= 4
 2328585.7431053 725456.773501082329087.21501012 725453.75258599
2329649.10521673725550.4218688472329984.42679164725517.191802865
#Sta/Elev= 30
       0 2173.68    26.4  2163.3    78.4  2154.9   178.4 2118.43   194.4  2108.7
   218.4 2099.91   256.4 2078.06   322.4 2033.89   362.4 2013.51   402.4 1996.85
   430.4 1979.22   486.4 1966.39   506.5 1953.43   522.7 1952.67   534.9 1944.58
   559.3 1940.56   571.5 1943.46   616.1 1941.31   725.7 1944.54   762.2 1936.71
   932.7 1936.61   945.1 1941.38  1058.5 1942.24  1078.7 1957.14  1102.8 1961.08
  1126.8 1985.19  1194.1 2026.09  1211.4 2027.77  1219.4 2032.24  1408.6 2039.44
#Mann= 9 ,-1,0
       0      .1       0     400     .06       0  601.48    .025       0
   762.2    .045       0   932.7    .025       0 1001.48      .1       0
 1101.63     .06       0 1201.63      .1       0 1401.63     .05       0
Bank Sta=762.2,932.7
XS Rating Curve= 0 ,0
Exp/Cntr(USF)=0,0
Exp/Cntr=0.3,0.1

Type RM Length L Ch R = 1 ,34955   ,412.9,417.1,425.8
XS GIS Cut Line= 3
2328550.59609522725707.6163236262329660.05513319725869.589585759
 2329967.1069101726070.946629796
#Sta/Elev= 30
       0 2233.38    74.4 2185.97   127.8 2155.19   143.1 2149.96   171.4 2145.42
   199.7 2137.54   248.2 2121.03   264.4 2111.19   369.2 2035.35   405.8 2011.01
   434.1 1989.19   470.5 1967.27   486.7 1965.75   510.9 1947.02   523.1 1940.45
   539.2 1938.33   696.9 1942.47   725.2 1937.47   769.7 1935.31   773.7  1935.2
   903.1 1935.27   935.4 1941.01   951.6 1950.82  1008.2    1953  1028.4  1956.2
  1175.9 1962.02  1322.3 1987.45  1419.5 2018.13    1461 2024.98  1488.4 2027.09
#Mann= 7 ,-1,0
       0      .1       0     440     .06       0     540      .1       0
   769.7    .045       0   903.1    .025       0    1040     .06       0
 1141.22      .1       0
Bank Sta=769.7,903.1
XS Rating Curve= 0 ,0
Exp/Cntr(USF)=0,0
Exp/Cntr=0.3,0.1

Type RM Length L Ch R = 1 ,34538   ,388.7,397.2,410
XS GIS Cut Line= 4
2328465.71211073725932.8050311452329021.41130617726160.306044042
2329405.55236073726268.4622632882329946.33345696726238.626064875
#Sta/Elev= 30
       0 2279.87    50.2 2253.95   153.9  2191.8   184.2 2177.71   309.5 2101.37
   378.7 2056.53   400.3 2039.19   413.3 2034.82   460.8 1999.28   469.5 1996.48
   499.7 1978.72     530 1965.96   542.9  1957.7   564.6 1956.11   603.3 1940.23
     620 1936.37   694.8 1939.96   726.6 1934.46     728 1934.38   898.4  1934.5
   919.2 1940.84   982.8 1941.47  1038.2 1958.67  1058.3 1959.38  1073.5 1966.91
  1118.3 1978.58  1174.4 1988.87  1242.5 1993.51  1466.9 1995.53  1541.1 2001.86
#Mann= 9 ,-1,0
       0      .1       0     460     .06       0     570      .1       0
  670.47    .025       0   726.6    .045       0   898.4    .025       0
  980.47      .1       0 1079.54     .06       0 1179.54      .1       0
Bank Sta=726.6,898.4
XS Rating Curve= 0 ,0
Exp/Cntr(USF)=0,0
Exp/Cntr=0.3,0.1

Type RM Length L Ch R = 1 ,34140   ,420.4,387.1,412
XS GIS Cut Line= 4
 2328336.5959621726240.378941532 2328810.2456119726467.879954428
2329403.24005535726728.9466905382329584.19659873 726935.11482157
#Sta/Elev= 30
       0 2193.88    87.2 2148.08   177.1 2105.03   212.5 2093.68     288 2080.44
   330.4 2062.68   416.7 2013.57   463.8 1983.67   474.3 1973.72   492.1 1970.72
     510 1954.19   525.5 1941.34   536.3 1937.87   585.6 1937.86   606.8 1934.73
   647.8 1937.56  666.971933.521   671.8 1932.83   920.9 1933.56   947.1 1941.61
  1058.9 1939.37  1108.8 1935.29  1119.6 1938.17  1143.8 1949.07  1161.3 1962.54
  1174.8 1964.39  1186.9 1974.88  1200.3  1981.9  1338.7 2031.35  1447.7 2089.87
#Mann= 8 ,-1,0
       0      .1       0     510     .06       0  615.45    .025       0
  666.97    .045       0   920.9     .12       0  935.45      .1       0
 1075.45     .06       0 1293.37      .1       0
Bank Sta=666.97,920.9
XS Rating Curve= 0 ,0
Exp/Cntr(USF)=0,0
Exp/Cntr=0.3,0.1

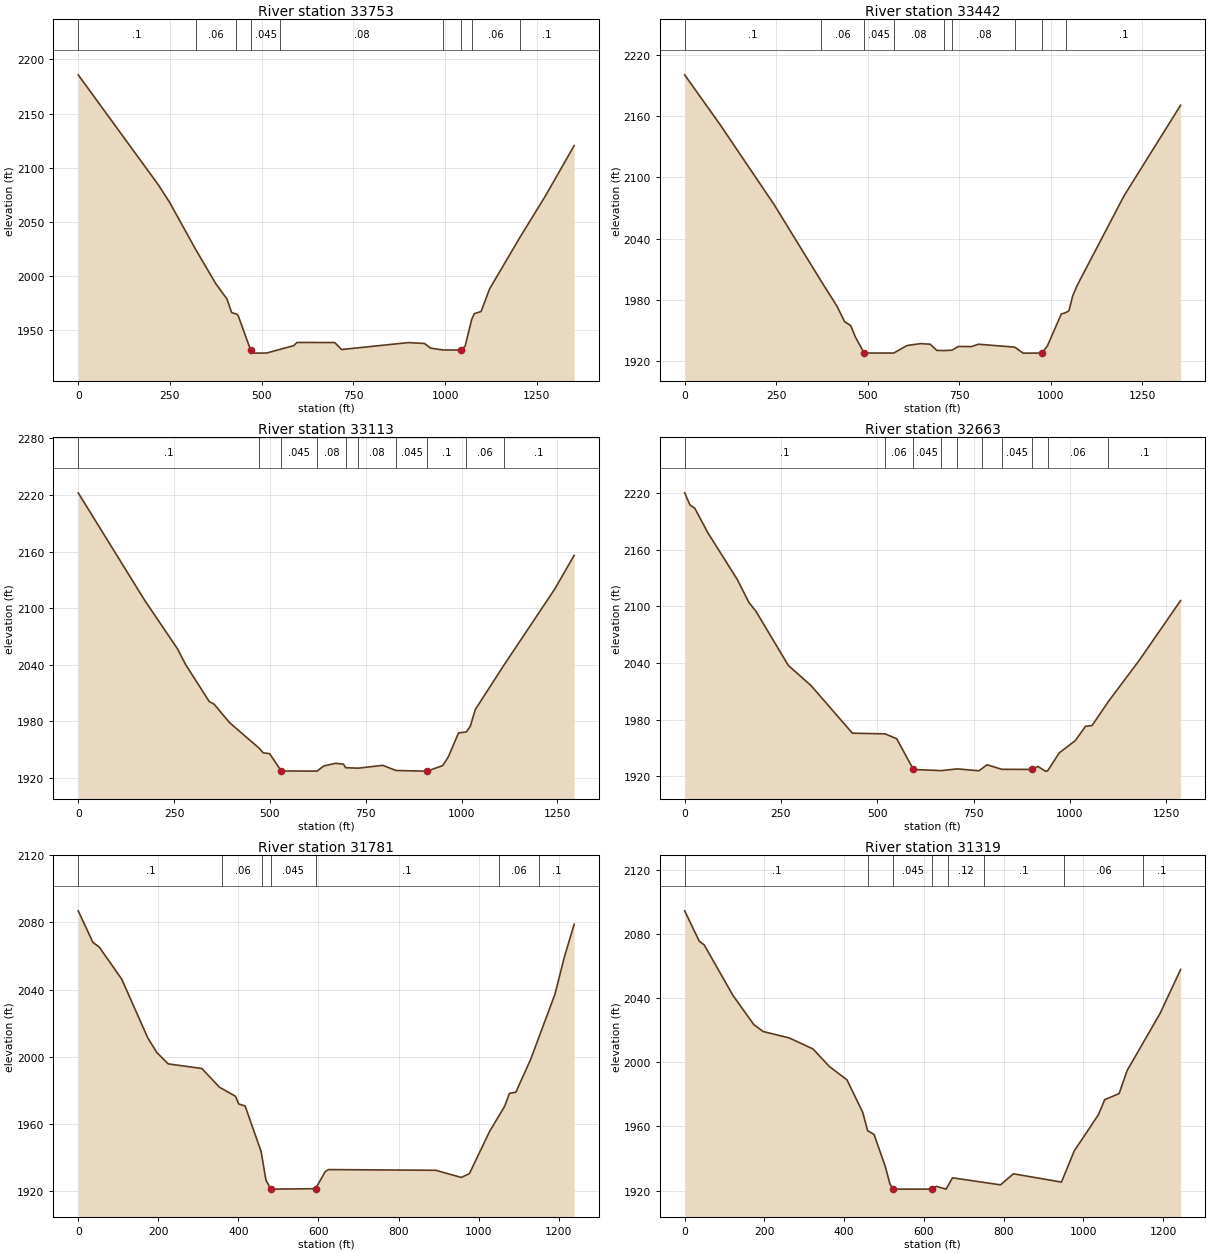
Type RM Length L Ch R = 1 ,33753   ,284.9,311,343.2
XS GIS Cut Line= 3
2328198.36535588 726628.130377752329149.95360901727026.891169535
 2329406.7313916 727217.20882016
#Sta/Elev= 30
       0 2185.83   218.8 2083.98   249.2 2067.93     320 2024.55     375 1992.82
   405.3 1978.73   418.3 1966.05   431.3 1964.77   435.7 1963.53   469.8 1931.56
     479 1928.69   513.7  1928.8   551.2 1932.27   587.5 1935.67   596.1 1938.55
     699 1938.49   717.6 1932.01   899.7 1938.43   943.5 1937.62   960.4  1933.3
   995.1 1931.57  1043.6  1931.6  1054.4 1935.25  1072.2 1959.78  1079.3 1965.16
  1097.9 1967.16  1120.8 1987.93  1203.5 2035.58  1273.5 2074.15  1351.4 2120.42
#Mann= 9 ,-1,0
       0      .1       0     320     .06       0   431.3      .1       0
   469.8    .045       0   551.2     .08       0   995.1    .045       0
  1043.6      .1       0  1072.2     .06       0  1203.5      .1       0
Bank Sta=469.8,1043.6
XS Rating Curve= 0 ,0
Exp/Cntr(USF)=0,0
Exp/Cntr=0.3,0.1

Type RM Length L Ch R = 1 ,33442   ,342.2,329,330.4
XS GIS Cut Line= 2
2328071.38945346726835.2381473832329268.56691477727469.257363652
#Sta/Elev= 30
       0 2200.15    95.9 2151.86   244.7 2072.96   371.7 1998.96   416.3 1973.68
     437 1958.56   453.5 1954.84   466.6 1943.44   490.3 1927.97   571.2 1927.96
   607.4 1935.33   645.2  1937.2   670.8 1936.59   688.5 1930.55   709.3 1930.37
     730 1930.76   747.7 1934.41   783.9  1934.3     802  1936.6   901.6 1933.74
   924.3 1927.88   975.6 1927.94   990.4 1934.63  1028.8 1966.13  1041.9 1967.69
  1049.6 1969.35    1060 1983.98  1072.5 1994.39  1200.5    2082  1354.7 2170.44
#Mann= 9 ,-1,0
       0      .1       0   371.7     .06       0   490.3    .045       0
   571.2     .08       0   709.3    .045       0     730     .08       0
   901.6    .045       0   975.6     .06       0  1041.9      .1       0
Bank Sta=490.3,975.6
XS Rating Curve= 0 ,0
Exp/Cntr(USF)=0,0
Exp/Cntr=0.3,0.1

Type RM Length L Ch R = 1 ,33113   ,458.5,450.7,442.3
XS GIS Cut Line= 2
2327876.63366832727155.8653945752329055.16350562727689.187441201
#Sta/Elev= 30
       0 2222.29   172.9 2108.69   258.5 2057.28   280.5 2040.11     342 2000.98
   354.3  1998.4   394.6 1978.81   472.2 1951.58   482.5 1946.81   499.4 1945.82
   529.6 1927.48   623.3 1927.41   640.5 1932.86   671.2 1935.66     692 1934.75
   697.6 1930.96   730.8 1930.51   794.2 1933.51   828.9 1928.05   901.4 1927.36
   910.7 1927.43   950.8 1933.26   965.4  1942.5   992.1 1967.83  1012.2 1968.82
  1022.5  1974.7  1035.7 1992.59    1110 2039.42    1243 2120.32  1293.6 2156.08
#Mann= 10 ,-1,0
       0      .1       0   472.2     .06       0   529.6    .045       0
   623.3     .08       0   697.6    .045       0   730.8     .08       0
   828.9    .045       0   910.7      .1       0  1012.2     .06       0
    1110      .1       0
Bank Sta=529.6,910.7
XS Rating Curve= 0 ,0
Exp/Cntr(USF)=0,0
Exp/Cntr=0.3,0.1

Type RM Length L Ch R = 1 ,32663   ,891.5,881.7,865.4
XS GIS Cut Line= 2
2327615.56693221727588.4902715582328823.93296792728032.303722946
#Sta/Elev= 30
       0 2220.42    13.4 2207.71    26.2  2204.1    60.2  2178.1     137 2128.23
   166.8  2104.2   184.9 2094.93     269  2037.5   328.3 2016.01   435.3 1965.68
   520.5 1964.93   550.4 1959.77   593.7 1927.21   665.4 1925.99     708 1927.83
   763.4 1925.81   771.9 1928.19   784.7 1932.22   823.1 1927.38   901.7 1927.24
   916.8 1930.42     936 1925.45   941.8 1925.54   972.2 1944.77  1013.9 1957.78
  1040.4 1972.92  1057.4 1973.76  1100.1  1999.4    1181 2043.51  1287.3 2106.28
#Mann= 10 ,-1,0
       0      .1       0   520.5     .06       0   593.7    .045       0
   665.4     .08       0     708    .045       0   771.9     .08       0
   823.1    .045       0   901.7      .1       0   941.8     .06       0
  1100.1      .1       0
Bank Sta=593.7,901.7
XS Rating Curve= 0 ,0
Exp/Cntr(USF)=0,0
Exp/Cntr=0.3,0.1

Type RM Length L Ch R = 1 ,31781   ,466.2,462.2,459.2
XS GIS Cut Line= 2
2327451.46784094728658.8638896112328689.67007507728625.298166397
#Sta/Elev= 30
       0 2086.94    36.7 2068.14    52.7  2065.3   108.7 2046.21   173.7 2011.23
   196.4 2002.47   224.8 1995.71   308.8 1992.98   352.8 1981.79   392.9 1976.39
   400.9 1971.83   416.9 1970.61   456.9 1943.45   468.9 1926.42   480.9 1921.25
   484.9 1921.06   592.9 1921.33   616.9 1931.48   624.9 1932.71     893 1932.29
   956.8 1928.03   977.1 1930.29  1027.2 1955.29  1065.1 1970.45  1077.1 1978.16
  1093.1 1978.81  1130.1 1998.43  1190.6 2037.12  1213.9 2059.07  1238.7 2078.92
#Mann= 7 ,-1,0
       0      .1       0     360     .06       0     460      .1       0
   480.9    .045       0   592.9      .1       0    1050     .06       0
    1150      .1       0
Bank Sta=480.9,592.9
XS Rating Curve= 0 ,0
Exp/Cntr(USF)=0,0
Exp/Cntr=0.3,0.1

Type RM Length L Ch R = 1 ,31319   ,459.4,447.2,438.5
XS GIS Cut Line= 2
2327451.46784094729158.6202130222328689.67007507729043.004944174
#Sta/Elev= 30
       0 2094.34    36.9 2075.27    48.9 2073.14   121.2 2041.56   173.5  2023.4
   196.7 2019.12   261.8 2015.15   322.1  2008.2   362.5 1997.37   406.9 1989.02
   446.6 1968.65   458.7 1957.31   474.8 1954.99   502.9 1935.11   514.9 1923.97
     523 1920.88   619.4 1920.88   631.4 1922.59   655.5 1920.88   671.6 1927.93
     792 1923.55   824.3 1930.44   944.8 1925.26   976.9 1944.71  1037.2 1967.13
  1053.3 1976.65  1089.4 1980.44  1109.5 1994.79  1192.5  2030.6  1243.6 2057.77
#Mann= 8 ,-1,0
       0      .1       0     460     .06       0     523    .045       0
   619.4      .1       0     660     .12       0     750      .1       0
     950     .06       0    1150      .1       0
Bank Sta=523,619.4
XS Rating Curve= 0 ,0
Exp/Cntr(USF)=0,0
Exp/Cntr=0.3,0.1

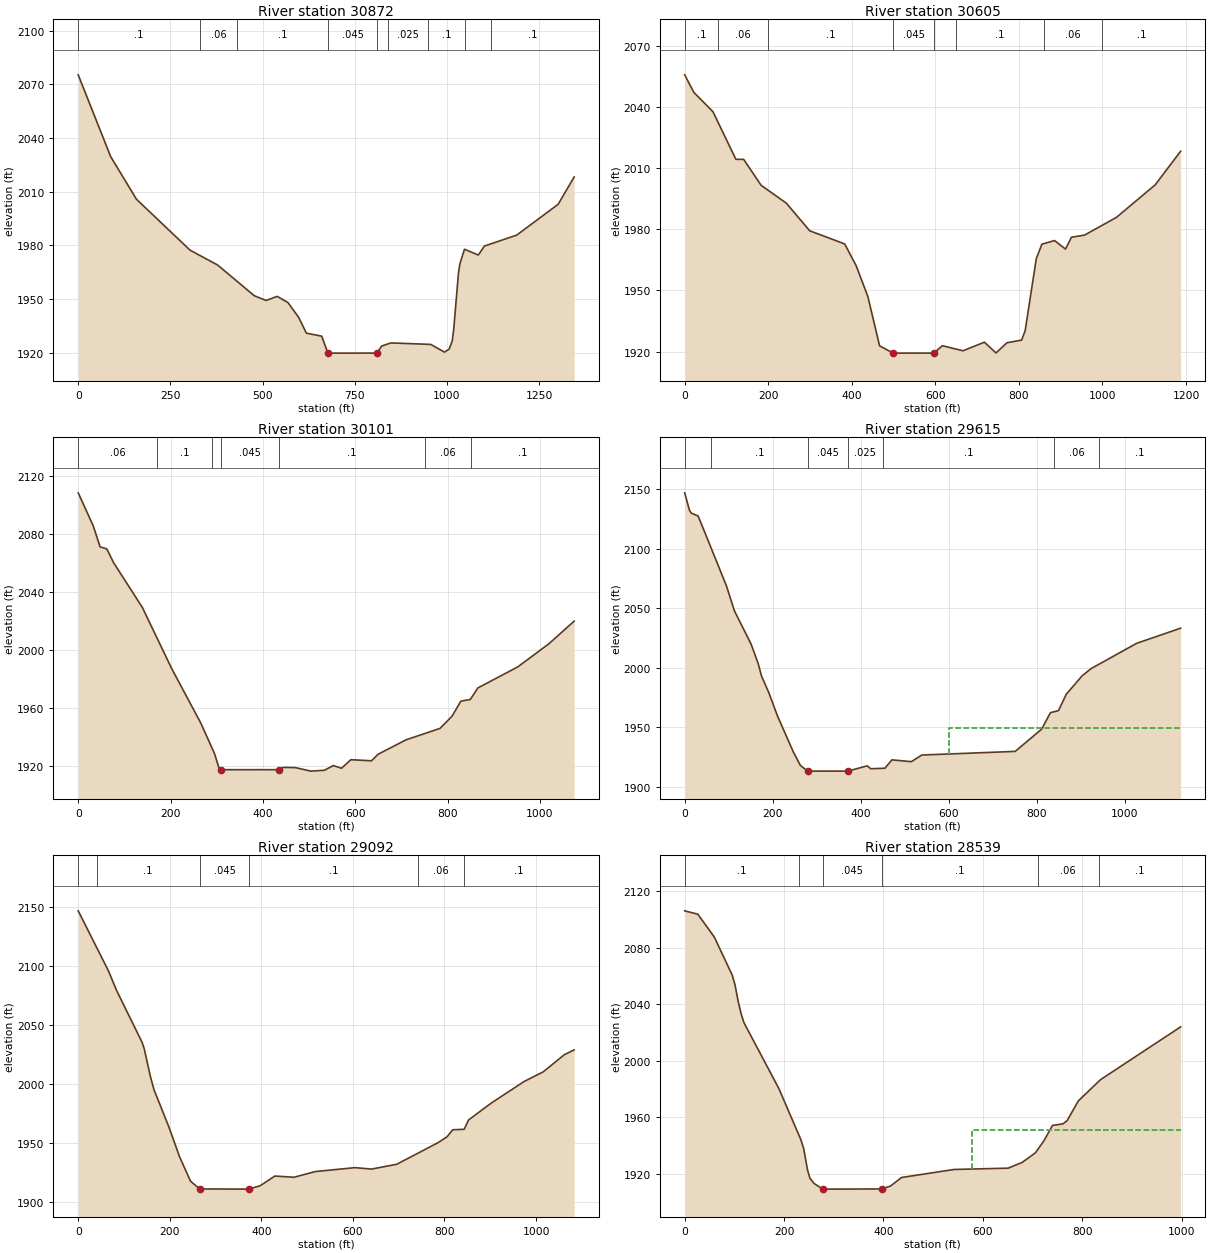
Type RM Length L Ch R = 1 ,30872   ,284.6,266.4,255.9
XS GIS Cut Line= 3
2327391.79544412729453.2526723472327921.38796594729598.704139609
2328685.94055027729378.662176316
#Sta/Elev= 30
       0 2075.39    88.1 2029.65     158 2005.85   303.2 1977.39   377.8 1969.12
   477.4 1951.93   509.6 1949.27   539.6 1951.56   568.8  1948.1   597.9 1939.81
   618.7 1930.99   660.3 1929.32     677 1919.93   681.1 1919.84   810.2 1919.86
   822.7 1923.77   847.6 1925.54   955.9 1924.72   993.3 1920.41  1005.8 1922.08
  1014.1 1926.55  1018.3 1933.31    1031 1964.37  1034.9  1969.7  1047.4 1977.91
  1084.9 1974.66  1101.5 1979.69  1188.9 1985.79  1301.3    2003  1344.8  2018.3
#Mann= 9 ,-1,0
       0      .1       0     330     .06       0     430      .1       0
     677    .045       0   810.2     .12       0   839.2    .025       0
   949.2      .1       0  1049.2     .06       0  1119.2      .1       0
Bank Sta=677,810.2
XS Rating Curve= 0 ,0
Exp/Cntr(USF)=0,0
Exp/Cntr=0.3,0.1

Type RM Length L Ch R = 1 ,30605   ,532.1,504.4,484.8
XS GIS Cut Line= 2
2327738.64125066730072.353789409 2328760.5310463729468.170771553
#Sta/Elev= 30
       0 2055.77      22 2047.14    67.7 2037.67   122.6 2014.32   141.2 2014.28
     183 2001.57   243.4 1992.79   299.2 1979.26   383.1 1972.79   410.7 1962.02
   438.6  1946.9   466.5 1922.81     499 1919.22   596.6 1919.23   616.7 1922.86
   666.3 1920.37   717.4 1924.59   745.2 1919.32   771.5 1924.32   806.5 1925.61
     815 1930.24   841.6 1965.56   855.1 1972.68   885.4 1974.45   911.6 1970.28
   925.8 1976.09   957.2 1977.13  1033.4 1985.82  1126.3 2001.79  1187.1 2018.27
#Mann= 8 ,-1,0
       0      .1       0      80     .06       0     200      .1       0
     499    .045       0   596.6    .025       0     650      .1       0
     860     .06       0    1000      .1       0
Bank Sta=499,596.6
XS Rating Curve= 0 ,0
Exp/Cntr(USF)=0,0
Exp/Cntr=0.3,0.1

Type RM Length L Ch R = 1 ,30101   ,524.9,486.2,453.7
XS GIS Cut Line= 3
2328354.01284292730460.2243687732328734.42437269 729908.25469814
2328816.47391832729512.925069172
#Sta/Elev= 30
       0 2108.63    32.8 2085.59    47.4 2071.27      62 2069.86    76.6 2060.34
   138.9 2029.42   202.9 1986.85   265.5 1949.47   295.2 1928.39   304.9  1918.4
   309.7 1917.24  435.88 1917.24   443.8 1918.84   470.1 1918.69   504.2 1916.25
   533.2 1916.84   552.6 1920.09   570.3 1918.25   590.4 1924.15   635.2  1923.4
   649.8 1927.98   710.3 1937.92   783.8 1945.82   809.8  1954.3   828.7 1964.62
   849.2 1965.78   865.5 1973.74   951.9 1988.28  1019.5 2004.31  1074.1 2019.93
#Mann= 7 ,-1,0
       0     .06       0     170      .1       0     290    .025       0
   309.7    .045       0  435.88      .1       0  750.36     .06       0
  850.36      .1       0
Bank Sta=309.7,435.88
XS Rating Curve= 0 ,0
Exp/Cntr(USF)=0,0
Exp/Cntr=0.3,0.1

Type RM Length L Ch R = 1 ,29615   ,548.6,522.5,499
XS GIS Cut Line= 2
2329036.51588161730575.8396376222329017.86825761729449.523147546
#Sta/Elev= 30
       0 2146.96    10.7 2132.52    14.7 2129.98    30.7 2127.41    94.7 2068.91
   113.1 2047.63   150.7 2019.92   166.7 2003.69   174.7 1992.75   190.7 1979.35
   210.7 1959.47   246.9 1929.08   262.7 1917.84     279    1913   370.7 1912.98
   414.7 1917.45   422.7 1914.99   454.7 1915.41   470.7 1922.45   514.9 1920.94
   538.7 1926.51   750.8 1929.57   810.8 1948.27   830.8 1962.14   849.1 1963.87
   866.8 1977.62   902.8 1993.11   922.8  1999.1  1026.8 2020.46  1126.5 2033.14
#Mann= 7 ,-1,0
       0     .06       0      60      .1       0     279    .045       0
   370.7    .025       0     450      .1       0     840     .06       0
     940      .1       0
#XS Ineff= 2 , 0
                          599.57         1949.14
Permanent Ineff=
       F       F
Bank Sta=279,370.7
XS Rating Curve= 0 ,0
Exp/Cntr(USF)=0,0
Exp/Cntr=0.3,0.1

Type RM Length L Ch R = 1 ,29092   ,568.4,553,535.7
XS GIS Cut Line= 3
2329689.18272189730378.1748231392329346.06644014729777.721330084
2329226.72164649729404.768849927
#Sta/Elev= 30
       0 2146.45      66 2095.58    84.1 2078.72   139.4 2035.08     144 2029.83
   157.8 2005.84   165.6 1994.77   197.9 1963.44   221.3 1938.08   245.3 1917.27
   265.3 1910.72   369.7 1910.56   373.8 1910.74   397.3  1913.4   429.6 1921.66
   471.1 1920.62     518 1925.46   604.7 1928.77   640.6 1927.55   695.7 1931.62
   785.8 1949.92   805.5 1954.88   818.1 1960.88     843 1961.28   852.6 1969.19
   902.1 1983.47   973.5  2001.7  1015.5 2009.93  1061.7 2024.49  1083.2 2028.57
#Mann= 6 ,-1,0
       0     .06       0      40      .1       0   265.3    .045       0
   373.8      .1       0  741.57     .06       0  841.57      .1       0
Bank Sta=265.3,373.8
XS Rating Curve= 0 ,0
Exp/Cntr(USF)=0,0
Exp/Cntr=0.3,0.1

Type RM Length L Ch R = 1 ,28539   ,420.1,417.1,412.2
XS GIS Cut Line= 3
2330229.96381812 730027.599491792329674.26462268729490.547920363
2329573.56745304729289.153581078
#Sta/Elev= 30
       0 2106.21    26.5 2103.82    59.6 2087.67    95.6 2060.78   101.3 2053.84
   107.6 2042.16   113.7 2033.25   119.3 2027.03   189.7 1980.27   233.7 1944.31
   239.5 1937.86   247.2 1922.83   251.9 1917.01   260.4 1913.19   277.4  1909.3
   279.8 1909.19   396.2  1909.3   414.1 1911.35   436.4 1917.42   542.1 1923.11
   650.8 1924.03   679.1  1928.1   705.7 1934.88     723 1943.44   740.2  1954.3
   761.1 1955.38   769.6 1957.65   792.2 1971.66   836.9  1986.7     998 2024.05
#Mann= 6 ,-1,0
       0      .1       0     230     .12       0   277.4    .045       0
   396.2      .1       0     710     .06       0   832.8      .1       0
#XS Ineff= 2 , 0
                          577.62         1950.86
Permanent Ineff=
       F       F
Bank Sta=277.4,396.2
XS Rating Curve= 0 ,0
Exp/Cntr(USF)=0,0
Exp/Cntr=0.3,0.1

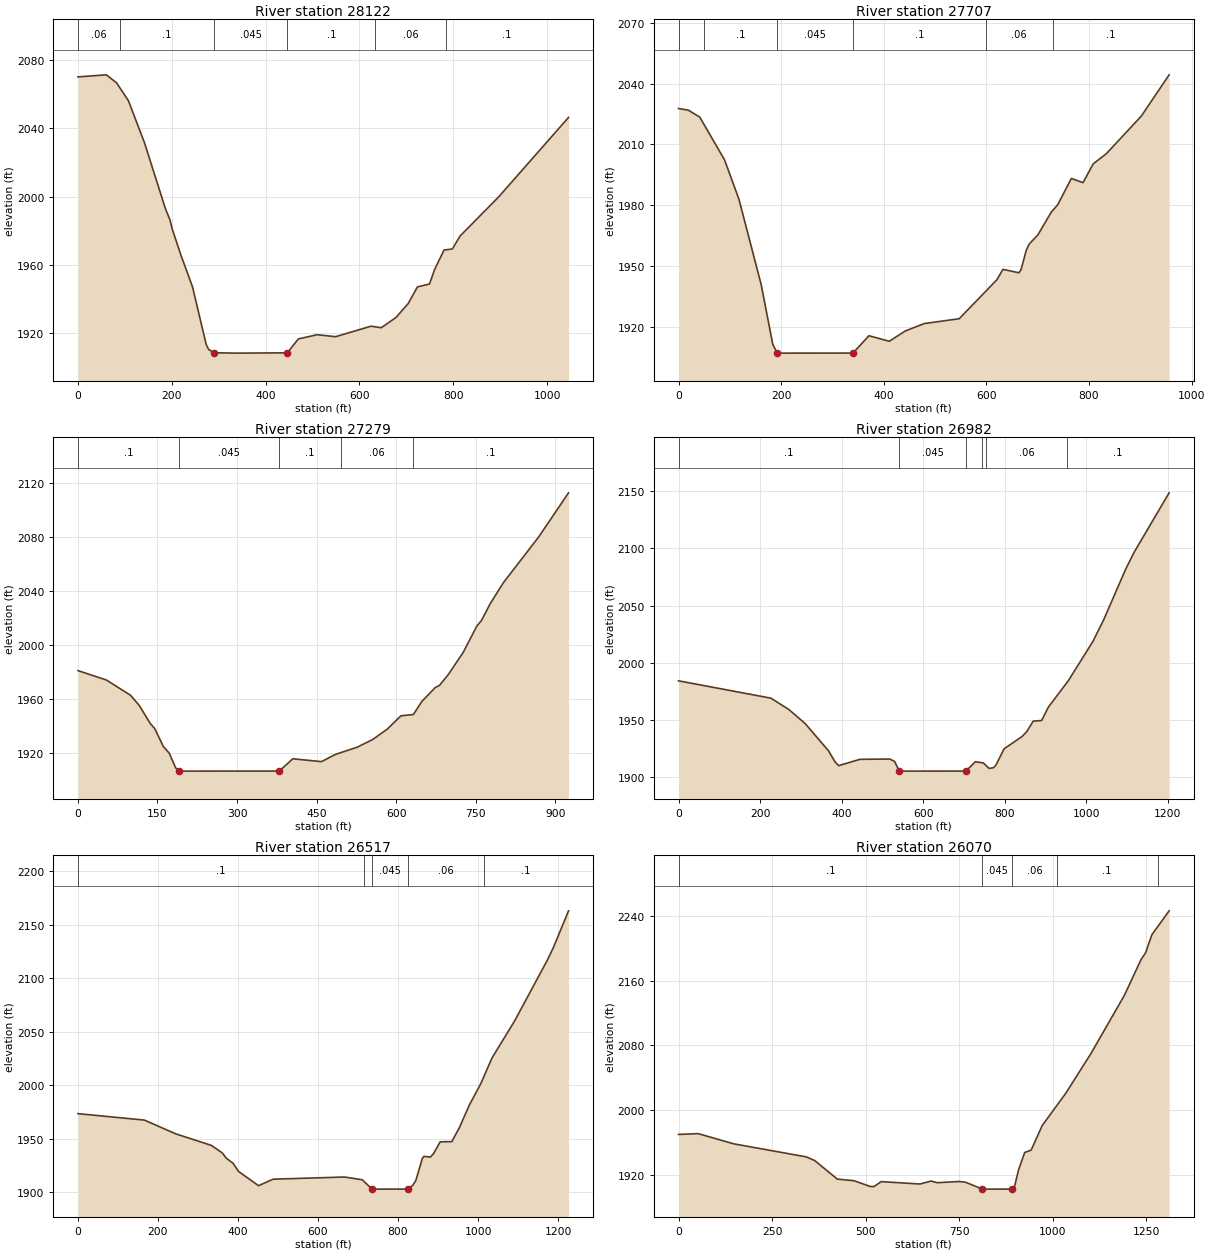
Type RM Length L Ch R = 1 ,28122   ,418.2,414.6,414
XS GIS Cut Line= 3
2330535.78485185729803.8280036952330386.60385978729598.704139609
2329801.06846594729065.382092983
#Sta/Elev= 30
       0 2070.21    60.5 2071.42    82.4  2066.7   107.6 2056.22   141.9 2031.52
   186.3 1992.99   196.2 1986.25   201.1 1980.86   219.2 1965.85   244.2 1946.97
   273.4 1913.14   278.6 1910.26   290.4 1908.32   338.1 1908.12   446.3  1908.3
   469.7 1916.45     510 1918.92   549.1 1917.76   624.5 1923.92   646.5 1923.04
   677.7 1928.99   703.8 1937.18   723.6 1946.99   749.3 1948.69   760.4 1957.36
   780.3 1968.61     798 1969.22   814.2 1976.77   896.4 1999.71  1045.6 2046.43
#Mann= 6 ,-1,0
       0     .06       0      90      .1       0   290.4    .045       0
   446.3      .1       0  633.64     .06       0  783.64      .1       0
Bank Sta=290.4,446.3
XS Rating Curve= 0 ,0
Exp/Cntr(USF)=0,0
Exp/Cntr=0.3,0.1

Type RM Length L Ch R = 1 ,27707   ,433.9,428.1,426
XS GIS Cut Line= 3
2330781.93348875729449.5231475462330703.61346792729322.719304292
2330088.24187566728800.585832071
#Sta/Elev= 30
       0 2027.73    19.2 2026.91    41.4 2023.48    89.7 2002.38   117.8 1982.97
   161.1 1940.89   183.8 1911.33   192.3 1907.23   194.7 1907.16   339.9 1907.19
   371.1 1915.74   410.6 1913.01     442 1918.09   479.1 1921.74     547 1924.12
   620.4 1943.31   632.2 1948.45   663.4 1946.77   667.6 1948.37   677.6 1957.82
   683.4 1960.92   700.3 1965.43   726.4 1976.65   738.8 1980.23   765.6 1993.26
   788.3 1991.19   808.1 2000.44   833.7 2005.45   901.8 2023.97   956.1 2044.33
#Mann= 6 ,-1,0
       0     .12       0      50      .1       0   192.3    .045       0
   339.9      .1       0  599.04     .06       0  729.04      .1       0
Bank Sta=192.3,339.9
XS Rating Curve= 0 ,0
Exp/Cntr(USF)=0,0
Exp/Cntr=0.3,0.1

Type RM Length L Ch R = 1 ,27279   ,285,297.2,306.5
XS GIS Cut Line= 4
2331050.45927447 729177.267837032331009.43450165729016.898270562
 2330662.5886951728737.1839104442330576.80962467728435.092401516
#Sta/Elev= 30
       0 1981.12    53.8 1974.16    99.2 1962.86   115.7 1955.31   136.3 1942.03
   144.6 1938.37   161.1 1924.96   172.3 1919.97   184.2 1909.25   190.6 1906.75
   379.6 1906.79   405.2 1915.89   459.2 1913.77   485.7 1919.14   526.9 1924.51
   555.9 1930.16   583.4 1937.85   609.1 1947.68   632.5 1948.63   648.5 1958.31
   673.5 1968.49   681.8 1970.23   698.4 1978.22   726.4 1994.56   752.3 2014.17
   760.8 2018.11   777.4 2030.63   802.4 2046.27   868.9 2080.06   925.1 2112.65
#Mann= 5 ,-1,0
       0      .1       0   190.6    .045       0   379.6      .1       0
  495.53     .06       0  631.11      .1       0
Bank Sta=190.6,379.6
XS Rating Curve= 0 ,0
Exp/Cntr(USF)=0,0
Exp/Cntr=0.3,0.1

Type RM Length L Ch R = 1 ,26982   ,392.9,465.4,508.1
XS GIS Cut Line= 4
 2331132.5088201729263.0469074672331296.60791137728905.012526515
2330979.59830324728588.002918381 2330893.8192328728237.427587033
#Sta/Elev= 30
       0 1984.01   226.5 1968.81   270.5 1958.88   310.1  1946.7   367.3 1922.91
   384.3 1912.74   392.8 1909.67   444.5  1915.2   518.1 1915.47   529.8 1913.34
   541.5  1904.9   549.6 1904.87   704.7  1904.9   727.8  1913.1   747.6 1912.02
   761.7 1907.24   772.6 1907.88   778.3 1910.15   798.5 1924.48   842.2 1935.12
     854 1939.53   869.8 1948.67   890.4 1949.23   906.8 1960.86   956.3 1984.32
  1016.1 2018.47  1043.1  2037.9  1096.3 2081.67  1116.9 2096.44  1203.1 2148.75
#Mann= 6 ,-1,0
       0      .1       0   541.5    .045       0   704.7    .025       0
  743.85      .1       0  753.85     .06       0  952.17      .1       0
Bank Sta=541.5,704.7
XS Rating Curve= 0 ,0
Exp/Cntr(USF)=0,0
Exp/Cntr=0.3,0.1

Type RM Length L Ch R = 1 ,26517   ,425.3,446.9,474.8
XS GIS Cut Line= 3
2331281.68981216729307.8012050862331475.62510185728942.307774531
 2331606.1584699728140.459942192
#Sta/Elev= 30
       0 1973.54     166 1967.53   244.3  1954.7   333.5 1943.89   360.7 1936.86
   370.6 1932.03   387.9 1927.11   401.5 1919.54   451.4 1906.26   487.9 1912.32
   666.2 1914.34   710.7 1911.77   735.1 1903.03   824.2 1903.08   836.4 1906.33
   844.5 1911.09   860.7 1931.57   864.7 1933.62     881 1933.02   889.1 1936.34
   905.3 1947.23   934.5 1947.39   953.9 1960.89   978.2 1981.57  1006.6 2001.36
    1035 2025.62  1091.4 2060.14  1172.7 2116.59    1189 2129.25  1226.2 2163.02
#Mann= 5 ,-1,0
       0      .1       0  713.76    .025       0   735.1    .045       0
   824.2     .06       0 1013.76      .1       0
Bank Sta=735.1,824.2
XS Rating Curve= 0 ,0
Exp/Cntr(USF)=0,0
Exp/Cntr=0.3,0.1

Type RM Length L Ch R = 1 ,26070   ,519.9,549.6,595.6
XS GIS Cut Line= 2
2331337.63268419729374.9326515142332247.63673577728431.362876715
#Sta/Elev= 30
       0 1969.63    52.5 1970.62   147.7 1957.99   341.4 1941.86   363.7 1937.36
   424.3 1914.38   469.2 1912.34   512.2 1905.23   522.3 1905.16   541.5 1911.25
   645.2 1908.29   674.9 1911.96   691.5 1909.89   749.9 1911.42   766.8 1910.52
   812.1 1902.03   813.8 1901.97   891.6    1902     897 1903.64   908.3 1925.41
   924.9 1947.26   942.2 1950.26   971.7 1980.58  1035.1 2020.83  1102.8  2070.3
  1191.7 2142.04  1236.1 2186.19  1247.8 2194.12  1264.7 2216.58  1310.9 2246.22
#Mann= 5 ,-1,0
       0      .1       0   812.1    .045       0   891.6     .06       0
    1010      .1       0    1280     .12       0
Bank Sta=812.1,891.6
XS Rating Curve= 0 ,0
Exp/Cntr(USF)=0,0
Exp/Cntr=0.3,0.1

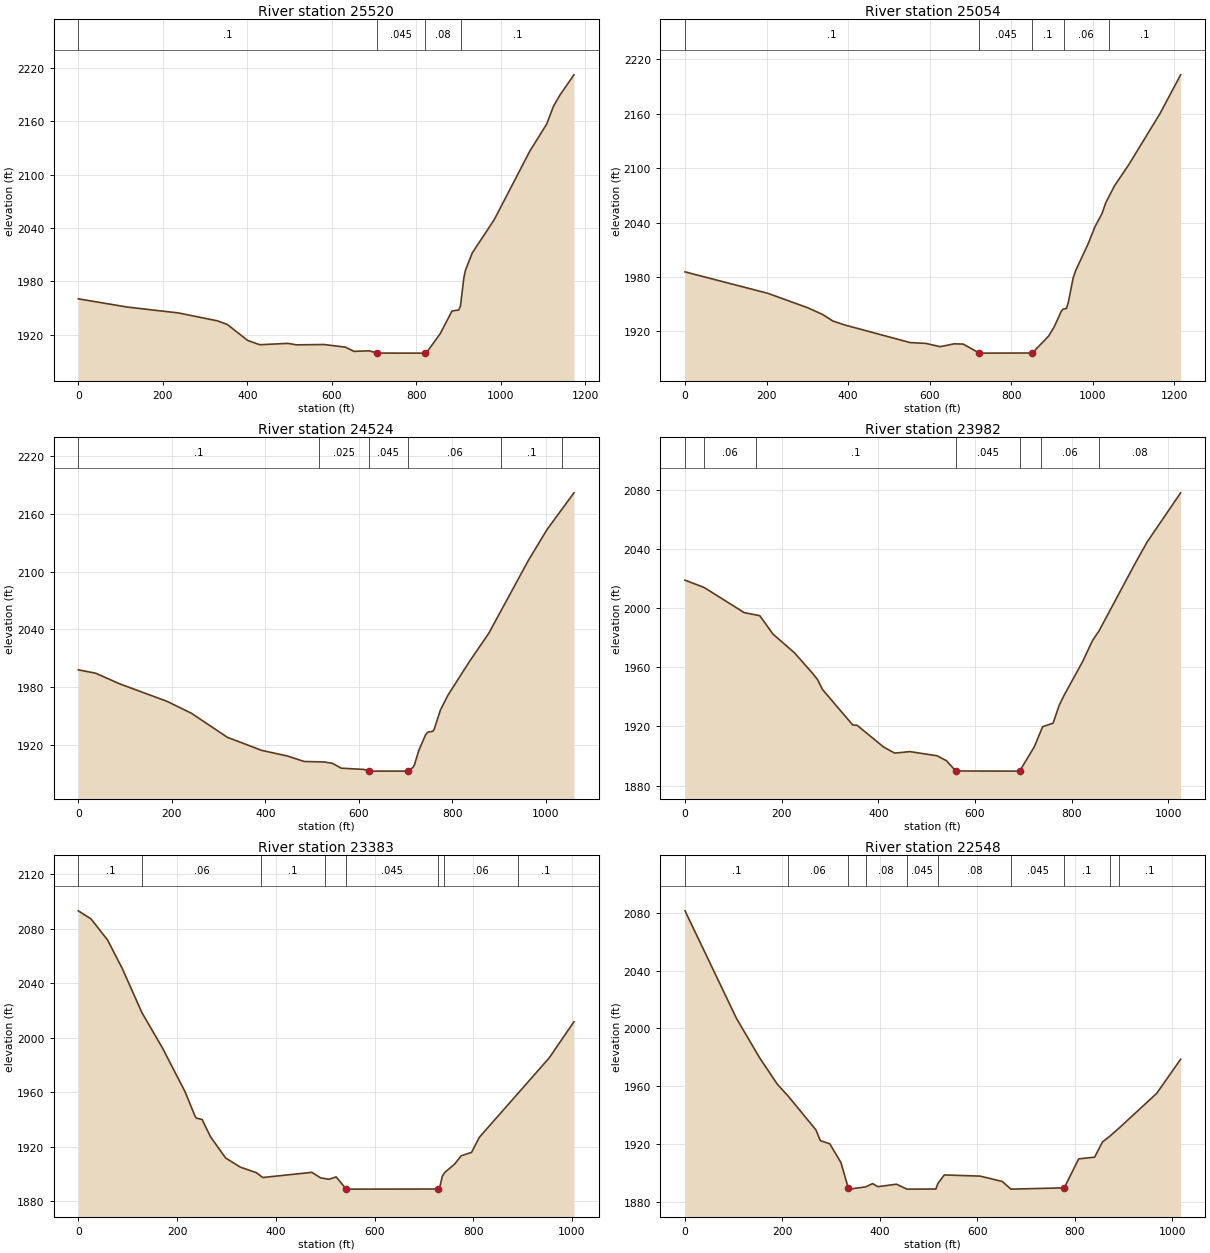
Type RM Length L Ch R = 1 ,25520   ,442,466.5,489.3
XS GIS Cut Line= 3
2331386.11650661729471.9002963552331751.60993716729274.235481871
2332508.70347188729292.883105879
#Sta/Elev= 30
       0 1960.42     116 1951.15   236.7 1944.56   329.8 1935.61   352.5 1931.57
   400.9 1913.58   429.5 1908.78   496.1 1910.33   516.1 1908.65   581.3 1909.04
   632.2 1906.06   652.2 1901.34   688.2 1901.93   707.9 1899.41   813.4 1899.35
   820.2  1899.4   828.2 1902.71   856.3 1921.21   884.2 1946.73   900.2 1947.85
   904.2 1952.18   912.2  1983.9   916.2 1992.74   932.2 2012.06   984.3 2049.59
  1068.3 2126.49  1108.3    2157  1124.3 2177.01  1140.3 2190.09  1172.8 2212.38
#Mann= 4 ,-1,0
       0      .1       0   707.9    .045       0   820.2     .08       0
  905.52      .1       0
Bank Sta=707.9,820.2
XS Rating Curve= 0 ,0
Exp/Cntr(USF)=0,0
Exp/Cntr=0.3,0.1

Type RM Length L Ch R = 1 ,25054   ,505.7,530.2,554.4
XS GIS Cut Line= 3
2331251.85361375729721.7784580612331762.79851157729628.540338021
2332400.54725264 729908.25469814
#Sta/Elev= 30
       0 1985.65   203.7 1961.93   301.2 1946.06   337.9 1938.62   362.2 1931.59
   390.7 1927.26   551.9 1907.75   590.7 1906.82   625.7 1903.18   660.6 1906.37
   682.5 1906.06   721.8 1896.19   726.2 1896.09   851.9 1896.23   892.2 1914.99
   905.3 1924.71   922.7 1941.92   927.1 1944.48   935.8  1945.4   940.2 1951.91
     952 1978.67   958.1 1986.87   988.5 2016.14  1005.7 2035.39  1023.2 2050.21
  1031.9 2061.61  1053.8 2080.64  1088.7 2103.84  1164.6 2159.66  1215.8 2202.81
#Mann= 5 ,-1,0
       0      .1       0   721.8    .045       0   851.9      .1       0
  929.38     .06       0 1039.38      .1       0
Bank Sta=721.8,851.9
XS Rating Curve= 0 ,0
Exp/Cntr(USF)=0,0
Exp/Cntr=0.3,0.1

Type RM Length L Ch R = 1 ,24524   ,540.9,542,548.3
XS GIS Cut Line= 3
 2331132.5088201729867.2299253222331483.08415145729915.713747743
2331945.54522684730449.035794369
#Sta/Elev= 30
       0 1998.08    36.9 1994.58    88.5 1983.54   189.5 1965.41   241.9    1953
   318.7  1928.1   392.2  1914.5   446.5 1908.77   482.9    1903   525.3 1902.51
   542.9 1901.17   562.3 1896.07   610.9 1894.75   620.6 1893.15   624.2    1893
   705.3 1893.04   715.9 1897.04   718.7 1899.53     728 1914.31   742.3 1930.47
     747 1933.32   758.2  1934.4   761.2 1936.75   774.1 1956.18     790 1971.47
   837.6 2007.61   877.5 2035.82   962.5  2111.7  1002.2 2143.51  1059.8 2181.67
#Mann= 6 ,-1,0
       0      .1       0  513.91    .025       0   620.6    .045       0
   705.3     .06       0  903.91      .1       0 1033.91     .08       0
Bank Sta=620.6,705.3
XS Rating Curve= 0 ,0
Exp/Cntr(USF)=0,0
Exp/Cntr=0.3,0.1

Type RM Length L Ch R = 1 ,23982   ,604.8,598.2,593.6
XS GIS Cut Line= 3
2330819.48696128729986.0561287422330954.20453051 730043.79222984
2331451.37651218730768.701054739
#Sta/Elev= 30
       0 2018.86    39.5 2013.91   122.6  1996.9   154.7 1994.84   182.2 1982.34
   226.7 1969.72   263.2 1956.17   274.4 1951.64   284.4 1945.04   347.1 1920.98
   356.1 1920.82   410.8 1906.15   433.8 1902.01   465.5 1903.01   521.7 1900.19
   541.1 1896.86   560.2 1889.93   691.5 1889.83   692.8 1890.04   722.9 1906.32
     740 1919.83   761.8 1922.24   773.9 1933.99   783.6 1940.54   822.5 1963.66
   843.1 1977.98   856.8 1984.61   931.7  2030.3   956.3 2044.64  1025.6 2077.84
#Mann= 7 ,-1,0
       0      .1       0      40     .06       0  146.57      .1       0
   560.2    .045       0   692.8      .1       0  736.57     .06       0
  856.57     .08       0
Bank Sta=560.2,692.8
XS Rating Curve= 0 ,0
Exp/Cntr(USF)=0,0
Exp/Cntr=0.3,0.1

Type RM Length L Ch R = 1 ,23383   ,791.3,835.3,665
XS GIS Cut Line= 2
2330328.73010194730229.8307778232330928.54404113731034.928632025
#Sta/Elev= 30
       0 2092.98    25.9 2086.99    59.2 2071.63      89 2050.67   128.9 2018.23
   170.6 1992.26   216.4 1960.13   236.4 1942.38   239.2  1940.9   250.7 1939.93
   267.8  1927.2   298.5 1911.62   328.4  1904.9   360.6  1900.9   373.6 1897.34
   473.1 1901.12   490.8 1897.07   507.9 1896.06   522.2 1897.76   542.9 1888.81
   728.8 1888.89   732.4 1890.45   737.4 1898.36   742.2 1900.99   762.4 1907.23
   775.7 1913.31   796.6 1915.76   812.2 1926.76   953.9  1985.1    1004 2011.61
#Mann= 8 ,-1,0
       0      .1       0     130     .06       0     370      .1       0
     500    .025       0   542.9    .045       0   728.8    .025       0
     740     .06       0     890      .1       0
Bank Sta=542.9,728.8
XS Rating Curve= 0 ,0
Exp/Cntr(USF)=0,0
Exp/Cntr=0.3,0.1

Type RM Length L Ch R = 1 ,22548   ,415.6,409.9,390
XS GIS Cut Line= 2
2329664.76493931730573.0398232392330351.18303015731323.609137515
#Sta/Elev= 30
       0 2081.29   105.8  2006.8   153.2 1979.59   189.4 1961.39   211.6  1953.2
   268.6 1929.83   277.7 1922.35     297  1920.2     320 1907.17  335.151889.527
     337 1888.81   370.6 1890.37     385 1892.62   395.9  1890.5   433.8 1892.22
   455.5 1888.81   514.8 1888.87   518.9 1892.65     532 1898.62   605.6 1897.81
   651.1  1894.1   668.9 1888.81   778.3 1889.69   807.8 1909.72   840.6 1910.92
   856.6 1921.38   871.7 1925.39   891.5 1931.25     968 1955.05  1017.1 1978.62
#Mann= 10 ,-1,0
       0      .1       0   211.6     .06       0  335.15    .045       0
   370.6     .08       0   455.5    .045       0   518.9     .08       0
   668.9    .045       0   778.3      .1       0   871.7     .06       0
   891.5      .1       0
Bank Sta=335.15,778.3
XS Rating Curve= 0 ,0
Exp/Cntr(USF)=0,0
Exp/Cntr=0.3,0.1