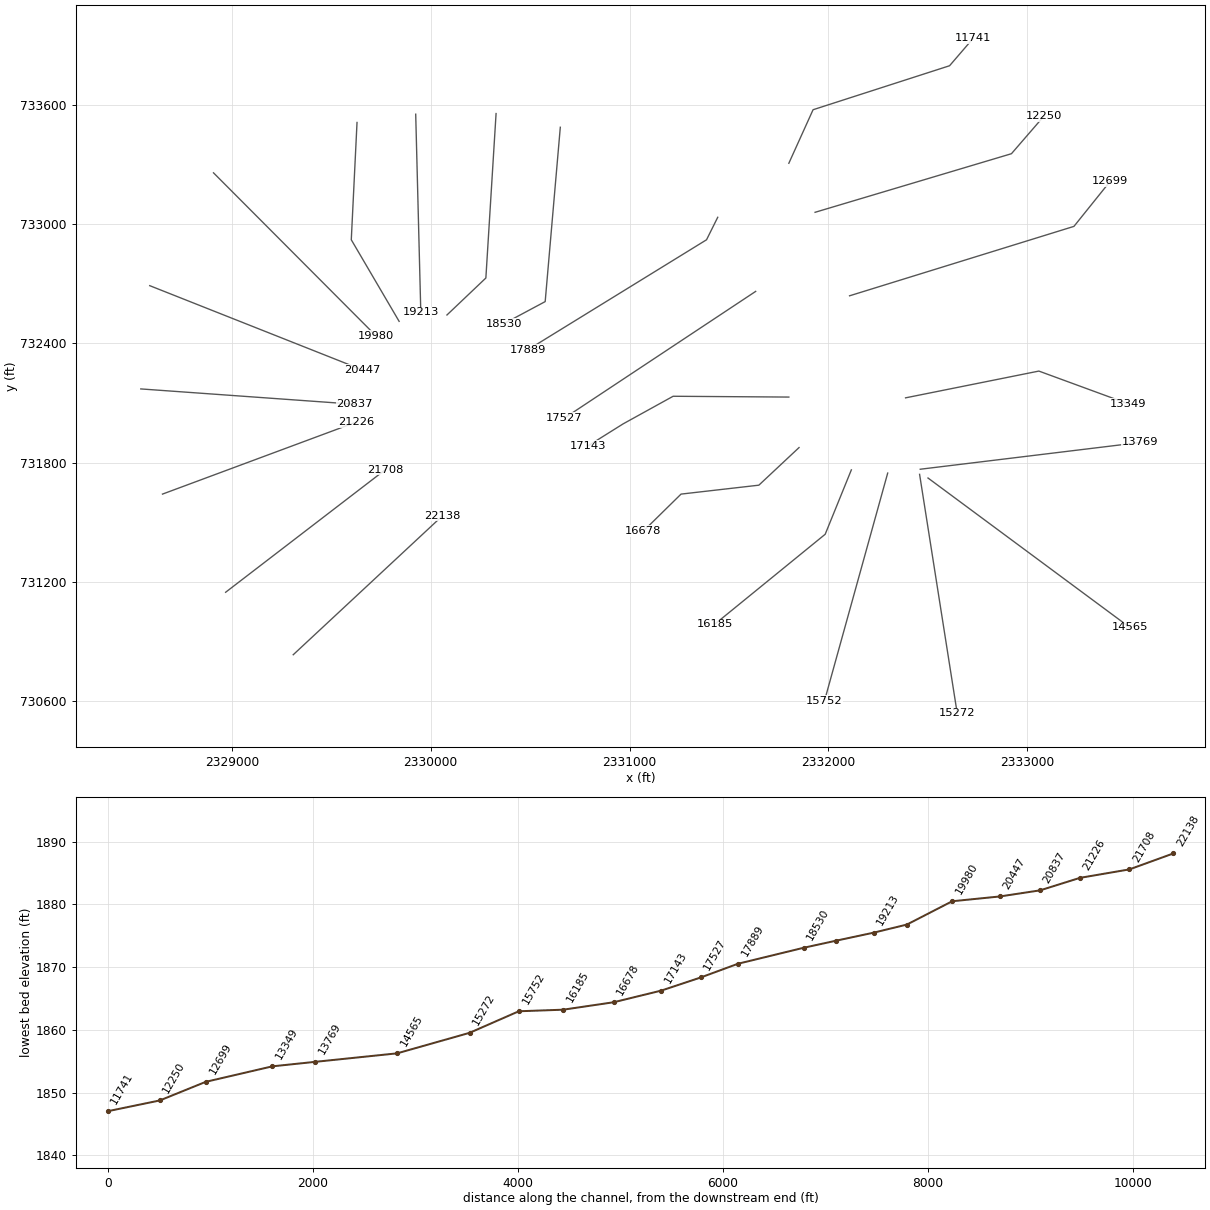
HEC-RAS study SHAVERSFK.prj: SHAVERSFK

--- SHAVERSFK.g01 (geometry) --- (continued)

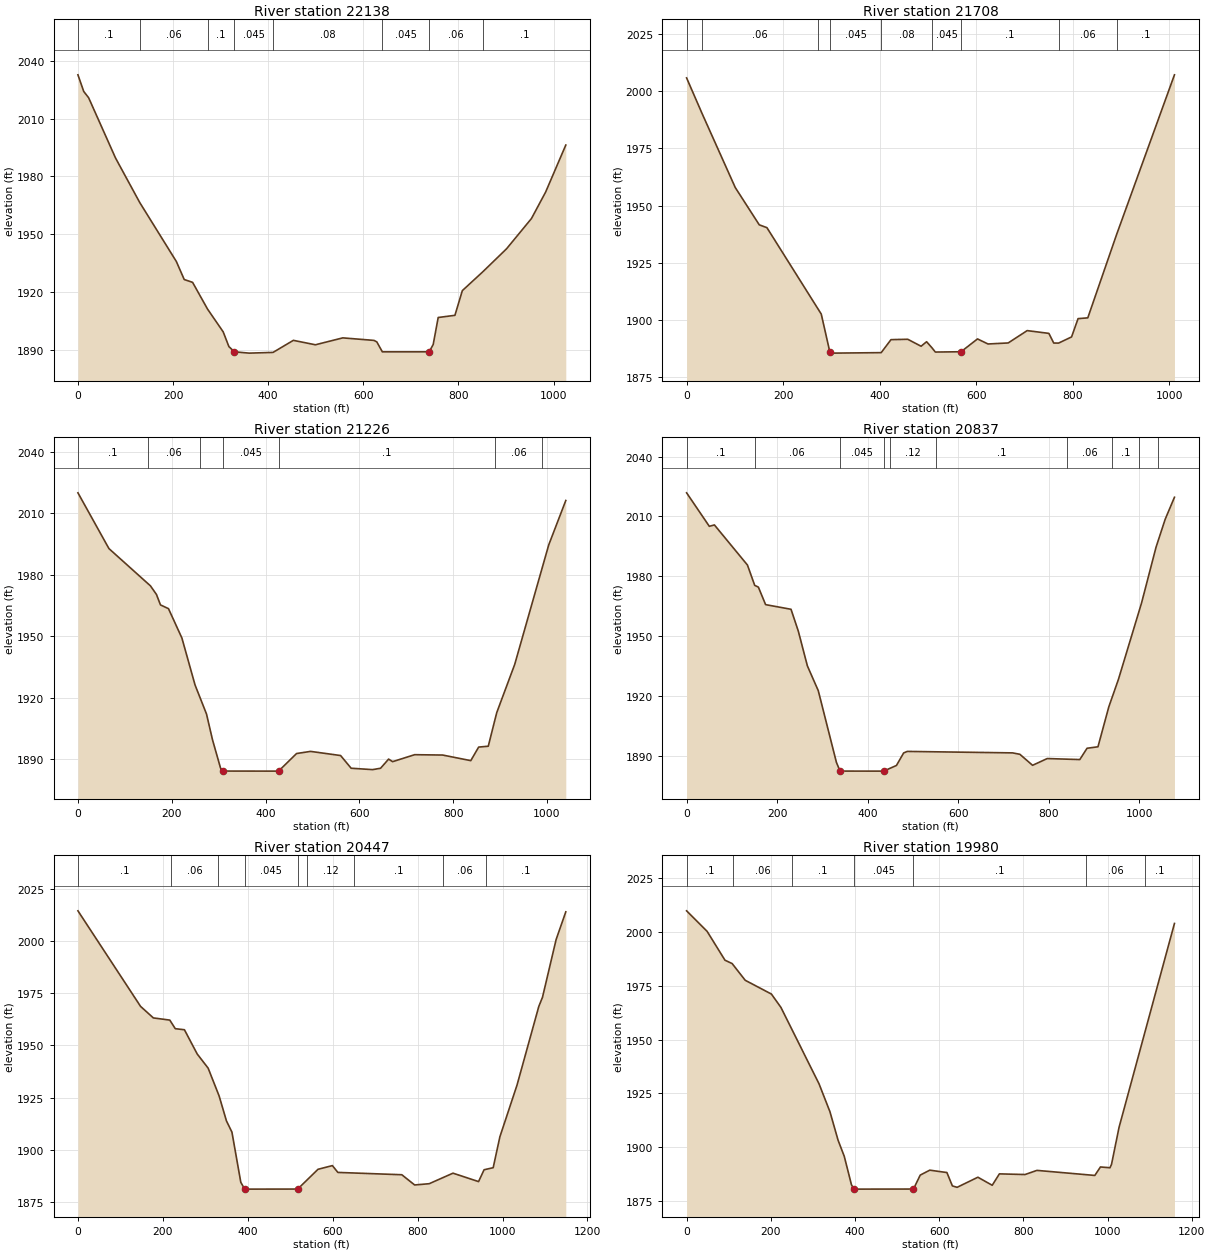
Type RM Length L Ch R = 1 ,22138   ,439.4,429.9,458.9
XS GIS Cut Line= 2
2329308.72564921730832.8522781812330059.29496348731532.100613703
#Sta/Elev= 30
       0 2032.69    12.2 2024.05    22.5 2020.79    79.1 1989.46     130 1966.35
     207 1935.71   223.5 1926.36   241.1  1924.9   272.6 1910.99   305.5 1899.16
   317.4 1891.54   329.1 1888.82   360.1 1888.14   410.2 1888.51     453 1894.78
   499.3 1892.47   556.9 1896.06   622.5 1894.75   628.4 1893.98   640.1 1888.81
   738.5 1888.82     747 1892.62   757.5 1906.64   792.7 1907.78   808.3 1920.61
   851.4 1930.41   901.3 1942.35   953.6 1958.05   983.3 1971.74  1025.8 1996.21
#Mann= 8 ,-1,0
       0      .1       0     130     .06       0   272.6      .1       0
   329.1    .045       0   410.2     .08       0   640.1    .045       0
   738.5     .06       0   851.4      .1       0
Bank Sta=329.1,738.5
XS Rating Curve= 0 ,0
Exp/Cntr(USF)=0,0
Exp/Cntr=0.3,0.1

Type RM Length L Ch R = 1 ,21708   ,501.5,482.6,474.6
XS GIS Cut Line= 2
2328968.72416496731147.1932730492329770.61445799731763.045018096
#Sta/Elev= 30
       0 2005.72    32.4 1990.03   100.9 1957.85   150.6 1941.59   166.5 1940.35
   271.7 1905.11   279.1 1902.64   296.9 1886.07   301.9 1885.59   403.3  1885.8
   423.6 1891.47   458.3 1891.64     486  1888.6   497.4 1890.56   508.7 1887.88
   515.5 1886.06     568 1886.19   569.2 1886.26   602.9 1891.79   624.7 1889.58
   666.5 1890.03   705.9 1895.42   750.8 1894.21   760.9    1890     771 1889.97
   797.9 1892.67   811.3 1900.64   831.5 1900.99   891.1 1937.29  1011.1 2007.06
#Mann= 9 ,-1,0
       0      .1       0    32.4     .06       0   271.7      .1       0
   296.9    .045       0   403.3     .08       0   508.7    .045       0
   569.2      .1       0     771     .06       0   891.1      .1       0
Bank Sta=296.9,568
XS Rating Curve= 0 ,0
Exp/Cntr(USF)=0,0
Exp/Cntr=0.3,0.1

Type RM Length L Ch R = 1 ,21226   ,410.4,388.3,365.3
XS GIS Cut Line= 2
2328651.17560892731641.1576935552329626.27420525732003.612106005
#Sta/Elev= 30
       0 2019.92    66.1 1992.74   154.7 1974.55   167.5 1970.34     176 1965.28
   193.1 1963.45   221.7 1949.14   249.7 1926.27   274.2 1912.06   286.9 1899.58
   304.1 1885.72   308.3 1884.27   427.8 1884.24   466.2 1892.82   496.1 1893.86
   560.1 1891.84   582.6 1885.65   628.4 1884.97   645.4 1885.65   662.5 1890.11
     671 1888.85     718 1892.25   777.7 1892.08   837.7 1889.35   854.5 1895.96
     875 1896.38     893 1912.72   931.4 1936.29  1003.9 1994.52  1040.3 2016.17
#Mann= 7 ,-1,0
       0      .1       0     150     .06       0     260      .1       0
   308.3    .045       0   427.8      .1       0     890     .06       0
     990      .1       0
Bank Sta=308.3,427.8
XS Rating Curve= 0 ,0
Exp/Cntr(USF)=0,0
Exp/Cntr=0.3,0.1

Type RM Length L Ch R = 1 ,20837   ,406.7,390.1,372.4
XS GIS Cut Line= 2
2328542.11852907732170.4052869552329616.65152173732093.423818824
#Sta/Elev= 30
       0 2021.86    50.2 2005.06    61.4 2005.76   134.4 1985.63   150.4 1975.45
   158.5 1974.56   174.5 1965.77   230.6 1963.44   246.7 1952.48   266.7 1935.06
   290.8  1922.6   330.9  1886.6   338.9 1882.27   435.2 1882.25   463.4 1885.09
   479.3 1891.37   487.3 1892.14   719.9  1891.4   735.9  1890.7     764 1885.17
   796.4 1888.56   868.3 1888.05   884.3 1893.72   908.4 1894.46   932.4 1914.53
   953.6 1928.29  1004.6 1966.57  1036.7 1994.63  1056.8 2008.58  1077.3 2019.63
#Mann= 10 ,-1,0
       0      .1       0     150     .06       0   338.9    .045       0
   435.2      .1       0     450     .12       0     550      .1       0
     840     .06       0     940      .1       0    1000     .06       0
    1040      .1       0
Bank Sta=338.9,435.2
XS Rating Curve= 0 ,0
Exp/Cntr(USF)=0,0
Exp/Cntr=0.3,0.1

Type RM Length L Ch R = 1 ,20447   ,495.5,467.6,439.8
XS GIS Cut Line= 2
2328587.02438548732690.030196838 2329655.1422558732266.632122118
#Sta/Elev= 30
       0 2014.37   147.5 1968.67   177.7 1963.15   216.4 1962.11   229.3    1958
   250.8 1957.51   280.9 1945.91   306.7 1939.13   332.6 1925.79   349.8  1913.9
   362.7 1908.55   383.6 1884.53   392.8 1881.28   517.6 1881.31   565.4 1890.76
   599.3 1892.53   612.2 1889.27   762.8 1888.16     793 1883.27   827.3 1883.87
   883.3 1888.91   943.6 1884.88   956.5 1890.54     978 1891.53   993.7 1906.25
  1034.2 1931.08  1085.5 1968.69  1094.1 1973.01  1126.2 2000.63    1149 2013.88
#Mann= 9 ,-1,0
       0      .1       0     220     .06       0     330      .1       0
   392.8    .045       0   517.6      .1       0     540     .12       0
     650      .1       0     860     .06       0     960      .1       0
Bank Sta=392.8,517.6
XS Rating Curve= 0 ,0
Exp/Cntr(USF)=0,0
Exp/Cntr=0.3,0.1

Type RM Length L Ch R = 1 ,19980   ,501.7,442.3,397.9
XS GIS Cut Line= 2
2328907.78050269733257.7685243032329725.70860158732436.632864241
#Sta/Elev= 30
       0 2009.85    48.8  2000.3    91.2  1986.9   108.2 1985.34   139.3 1977.57
   201.5 1971.17   224.1 1964.97   314.7 1929.42   340.6 1916.46   359.9 1903.23
   374.6 1895.74   391.6  1882.6   397.3 1880.51     539 1880.55   555.1 1887.03
   577.7 1889.32   618.4 1888.22   631.4 1882.01   642.7 1881.35     692 1886.04
   726.1  1882.3   743.1  1887.6     804 1887.29   832.3 1889.22   969.8 1886.87
   983.2 1890.81  1005.8 1890.44  1009.5 1892.04  1027.4 1909.24    1159 2003.97
#Mann= 7 ,-1,0
       0      .1       0     110     .06       0     250      .1       0
   397.3    .045       0     539      .1       0     950     .06       0
    1090      .1       0
Bank Sta=397.3,539
XS Rating Curve= 0 ,0
Exp/Cntr(USF)=0,0
Exp/Cntr=0.3,0.1

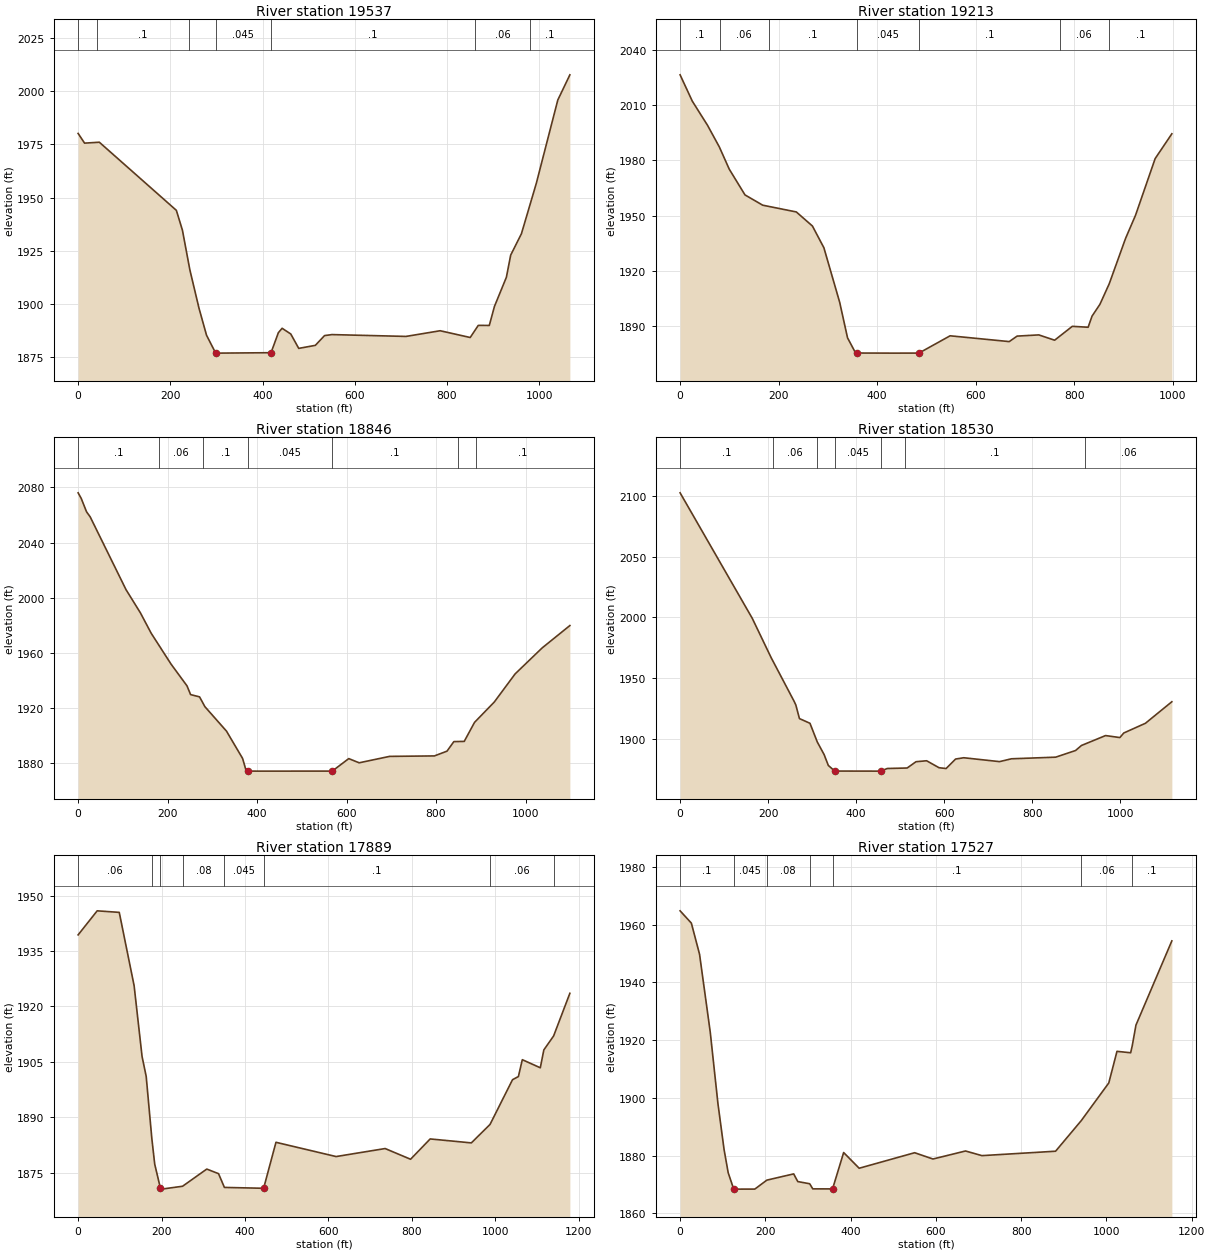
Type RM Length L Ch R = 1 ,19537   ,319.9,324.5,329.3
XS GIS Cut Line= 3
2329629.48176642733511.1658569012329600.61371587732920.974601231
2329841.18080378  732510.4067712
#Sta/Elev= 30
       0 1980.16      14 1975.59      46 1976.02   213.1 1943.97   226.3 1934.62
   242.3 1916.07   262.3 1897.86   278.6 1885.19   298.3 1876.85   302.3 1876.79
   418.5 1876.99   434.4  1886.4   442.5 1888.48   461.3  1885.8   478.6 1879.02
   514.6 1880.45   534.6 1885.04   550.6 1885.51   711.2 1884.65   785.4 1887.32
   850.6 1884.14   868.1 1889.84     892 1889.82   903.2 1898.77   929.1  1912.5
   938.4  1922.9   961.7 1932.97     994 1956.68  1040.6 1995.86  1066.8 2007.73
#Mann= 7 ,-1,0
       0     .06       0      40      .1       0     240    .025       0
   298.3    .045       0   418.5      .1       0   860.9     .06       0
   980.9      .1       0
Bank Sta=298.3,418.5
XS Rating Curve= 0 ,0
Exp/Cntr(USF)=0,0
Exp/Cntr=0.3,0.1

Type RM Length L Ch R = 1 ,19213   ,371.8,366.3,365.5
XS GIS Cut Line= 2
2329924.57739426733552.8641521382329950.23788363732555.312627609
#Sta/Elev= 30
       0 2026.31    24.7 2012.07    55.7 1998.94    79.7 1987.18    99.7 1975.21
   131.7 1961.23   167.7 1955.66   235.8 1952.01   268.5 1944.39   291.8  1932.6
   323.8 1903.09   339.8 1883.77   355.8 1875.74   359.8 1875.55   432.3  1875.5
   484.7 1875.52   547.9 1884.89   667.9 1881.75   683.9 1884.72   727.9 1885.38
     760  1882.5   795.9 1890.02     828 1889.52     836 1895.57     852 1901.98
   870.8 1913.06     904 1937.68   924.2 1950.21     964 1980.91   997.9 1994.36
#Mann= 7 ,-1,0
       0      .1       0      80     .06       0     180      .1       0
   359.8    .045       0   484.7      .1       0     770     .06       0
     870      .1       0
Bank Sta=359.8,484.7
XS Rating Curve= 0 ,0
Exp/Cntr(USF)=0,0
Exp/Cntr=0.3,0.1

Type RM Length L Ch R = 1 ,18846   ,318.8,316.9,322.7
XS GIS Cut Line= 3
2330328.73010194 733556.071713312330277.40912319732728.520930904
2330081.74789169732542.482382921
#Sta/Elev= 30
       0 2076.11     6.9 2072.09    18.9 2062.29    26.9 2058.71   107.1 2005.84
   139.2 1989.05   163.2 1974.31   207.6  1951.9   243.4 1936.05   251.4 1929.73
   271.4 1928.09   283.4 1920.96   331.6 1903.24   367.6 1883.43   375.6 1874.47
   379.6 1874.24   407.7 1874.22     568 1874.24   604.9  1883.3   628.1 1880.26
   696.2 1884.92   796.4 1885.25   824.5 1888.72   839.8 1895.63     863 1895.79
     886 1909.58   930.2 1924.36   976.7 1944.74  1037.2 1963.61  1099.1 1979.83
#Mann= 7 ,-1,0
       0      .1       0     180     .06       0     280      .1       0
   379.6    .045       0     568      .1       0  849.14     .06       0
  889.14      .1       0
Bank Sta=379.6,568
XS Rating Curve= 0 ,0
Exp/Cntr(USF)=0,0
Exp/Cntr=0.3,0.1

Type RM Length L Ch R = 1 ,18530   ,774.6,640.8,593.3
XS GIS Cut Line= 3
2330651.75742505733487.099348923 2330575.7123122732609.841167535
2330367.24043438 732498.25375101
#Sta/Elev= 30
       0 2102.75     164 1999.13   206.7 1966.81   258.9 1930.77   262.9 1927.64
   271.1 1916.44     295 1912.57   311.7 1897.08   327.1 1886.77   336.7 1877.77
   351.2 1873.14   455.6 1873.09   470.6 1875.26   515.8 1875.67   535.9 1880.86
     560 1881.64   588.1 1875.92   604.2 1875.23   625.8 1883.06   644.3 1884.13
   725.6 1880.93   752.7 1883.27   853.1 1884.61   898.2 1890.09   911.8 1894.27
   966.4 1902.43   998.9 1900.79  1007.8 1904.56    1057 1912.58    1117 1930.34
#Mann= 7 ,-1,0
       0      .1       0     210     .06       0     310      .1       0
   351.2    .045       0   455.6    .025       0     510      .1       0
  920.55     .06       0
Bank Sta=351.2,455.6
XS Rating Curve= 0 ,0
Exp/Cntr(USF)=0,0
Exp/Cntr=0.3,0.1

Type RM Length L Ch R = 1 ,17889   ,355.5,361.7,364.4
XS GIS Cut Line= 3
2331443.41906797 733034.094480422331387.11153129732920.928266191
2330491.06004638732368.743111902
#Sta/Elev= 30
       0 1939.39    45.7  1945.9    98.6 1945.48   134.2 1925.65   153.3 1906.45
   163.2 1901.06   176.8 1884.16   183.6 1877.31  197.19 1870.83   200.3 1870.54
   250.4 1871.32   308.4 1875.97   336.6 1874.73   350.7    1871   444.7 1870.77
   474.3 1883.22   618.5 1879.36     736 1881.53     797 1878.63     844 1884.13
   942.7 1883.06   987.5 1888.06  1041.4 1900.17  1055.5 1901.02  1064.9 1905.59
    1108  1903.4  1116.5 1908.24    1140 1912.03    1140 1912.04  1178.9 1923.57
#Mann= 8 ,-1,0
       0     .06       0   176.8      .1       0  197.19    .045       0
   250.4     .08       0   350.7    .045       0   444.7      .1       0
   987.5     .06       0    1140      .1       0
Bank Sta=197.19,444.7
XS Rating Curve= 0 ,0
Exp/Cntr(USF)=0,0
Exp/Cntr=0.3,0.1

Type RM Length L Ch R = 1 ,17527   ,474.7,384.2,361.7
XS GIS Cut Line= 2
2331634.20749899732661.1621462892330672.90695554732023.825281215
#Sta/Elev= 30
       0 1964.83    26.4 1960.57    45.6 1949.79    70.7 1922.79    88.8 1897.94
   103.2 1882.02   112.8 1874.04   125.5 1868.47   127.2 1868.36   175.2 1868.37
   203.5 1871.48   266.4 1873.64     276 1870.98     304 1870.22   311.2 1868.45
   357.6 1868.44   383.6 1881.04     420  1875.6   550.1 1880.98   593.1  1878.8
   669.5 1881.58   707.9 1879.97   880.7  1881.5     941 1892.12  1005.5 1905.17
  1024.7 1916.12  1056.8 1915.63  1060.6 1918.13  1069.2 1925.21  1153.4 1954.41
#Mann= 7 ,-1,0
       0      .1       0   125.5    .045       0   203.5     .08       0
     304    .045       0   357.6      .1       0     941     .06       0
  1060.6      .1       0
Bank Sta=125.5,357.6
XS Rating Curve= 0 ,0
Exp/Cntr(USF)=0,0
Exp/Cntr=0.3,0.1

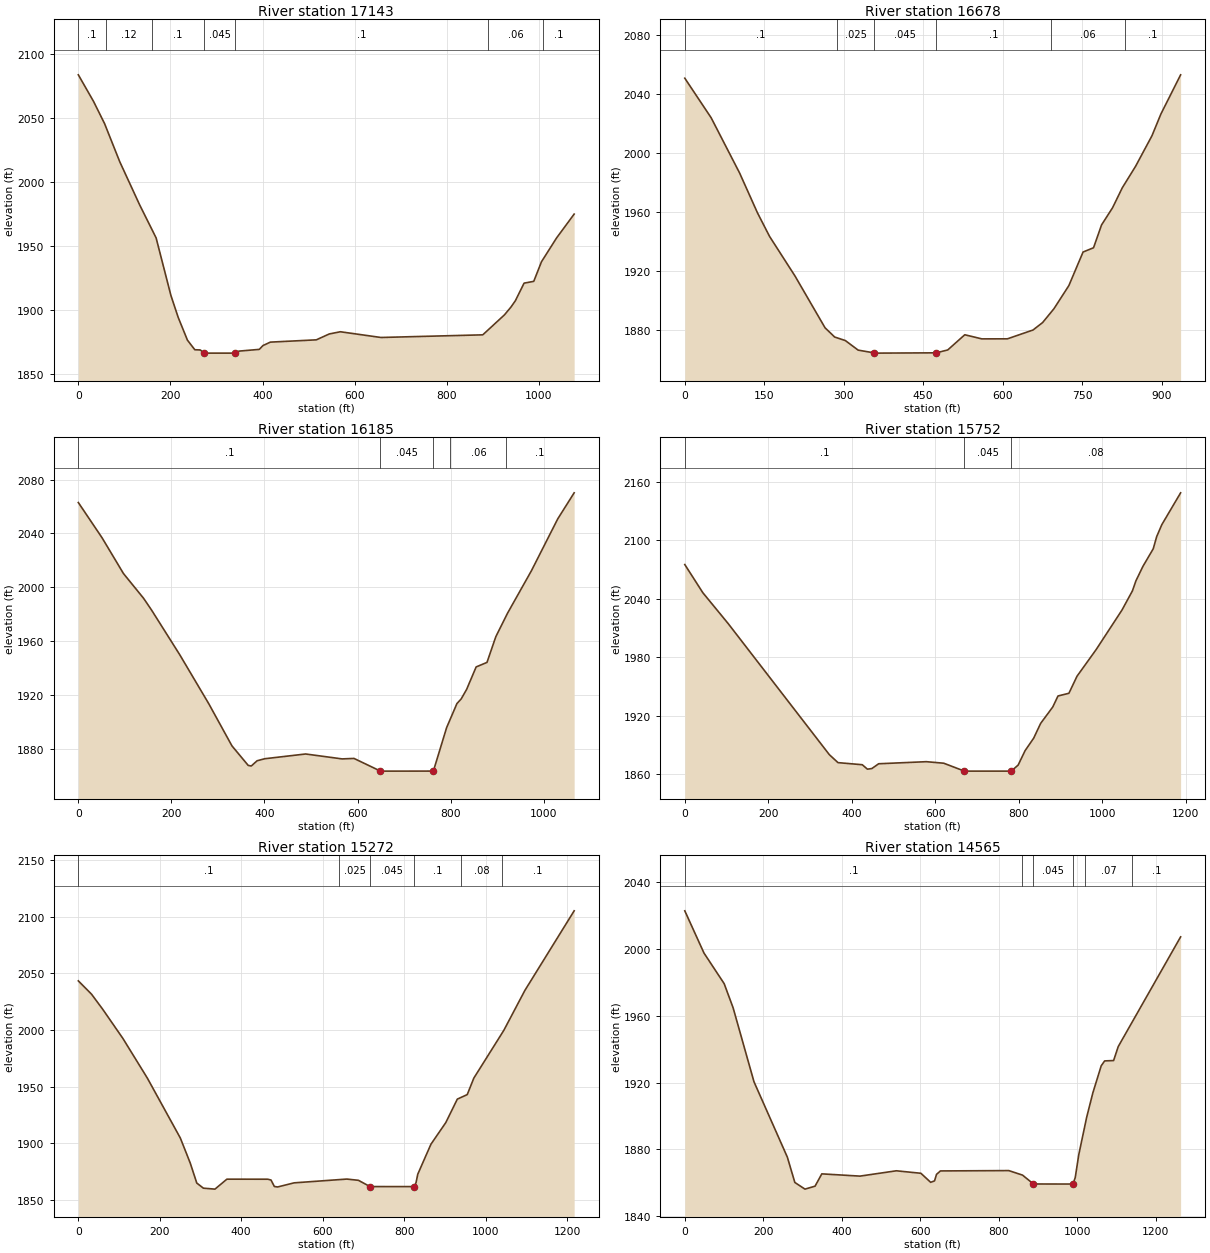
Type RM Length L Ch R = 1 ,17143   ,460.7,464.8,472.6
XS GIS Cut Line= 4
2331801.06800251732129.405652446  2331219.078946732133.465471654
2330967.81347606731994.6334782382330792.04166734731884.502972136
#Sta/Elev= 30
       0 2084.03    32.9 2063.31    56.9 2045.93    89.7 2016.23   132.9 1982.46
   168.9 1956.41   200.9 1911.54   216.9 1894.15   236.9 1876.42   252.9 1868.92
   264.9 1868.73   272.9 1866.27   340.9 1866.27   348.9 1867.85   392.9  1869.2
   400.9 1872.21   416.9 1874.88   516.7 1876.66   544.9 1881.28   568.9 1882.99
     657 1878.51   878.1 1880.58   925.3 1896.25   939.5 1902.41   948.9 1907.29
   967.8 1921.04   988.8 1922.43  1005.5 1937.72  1038.2 1956.33  1076.5 1975.06
#Mann= 7 ,-1,0
       0      .1       0      60     .12       0     160      .1       0
   272.9    .045       0   340.9      .1       0  889.07     .06       0
 1009.07      .1       0
Bank Sta=272.9,340.9
XS Rating Curve= 0 ,0
Exp/Cntr(USF)=0,0
Exp/Cntr=0.3,0.1

Type RM Length L Ch R = 1 ,16678   ,469.5,493.6,533.9
XS GIS Cut Line= 4
 2331852.3216587 731875.309659122331650.24530486731686.063549965
2331258.92284186731641.157693555 2331069.6767327731455.119145572
#Sta/Elev= 30
       0 2050.57    49.7 2023.81   103.5 1986.35   137.4 1959.26   160.1  1943.4
   208.2 1916.55   264.8 1881.56     283  1875.3   303.1 1872.92   327.3 1866.44
  357.491864.576   359.5 1864.41   474.6 1864.61   496.4 1866.55   528.6 1876.85
   560.8 1874.06   609.1 1874.09   657.4 1880.06   675.5 1885.09     697  1894.5
   725.1 1910.13   751.9 1932.86   771.7 1935.76   786.8  1951.2   807.7 1962.91
     826 1976.38   850.9 1990.81     882  2011.6   898.9 2026.34   936.1 2052.85
#Mann= 6 ,-1,0
       0      .1       0  286.86    .025       0  357.49    .045       0
   474.6      .1       0  690.75     .06       0  830.75      .1       0
Bank Sta=357.49,474.6
XS Rating Curve= 0 ,0
Exp/Cntr(USF)=0,0
Exp/Cntr=0.3,0.1

Type RM Length L Ch R = 1 ,16185   ,400.6,432.5,469.2
XS GIS Cut Line= 3
2332115.34167481731763.0450180962331983.83166676731439.081339712
2331428.92358398730986.815214443
#Sta/Elev= 30
       0 2062.98      51 2036.76      97 2010.17   140.2 1991.77   157.4 1982.99
   217.9 1949.81   280.2 1913.42   330.1 1882.02     365  1867.5   371.6 1867.03
   384.3 1870.95   400.8 1872.44   488.5 1875.97   566.8 1872.31   592.4 1872.66
   649.3 1863.24   650.2 1863.22     762 1863.25   764.2 1864.64   791.4 1895.53
   813.6 1913.49   822.7  1916.9   834.3 1923.91   854.9 1940.71   878.2 1944.09
   897.1 1963.15   922.2 1980.59   973.6 2012.21  1030.2  2050.8  1065.5  2070.2
#Mann= 5 ,-1,0
       0      .1       0   649.3    .045       0     762      .1       0
  799.64     .06       0  919.64      .1       0
Bank Sta=649.3,762
XS Rating Curve= 0 ,0
Exp/Cntr(USF)=0,0
Exp/Cntr=0.3,0.1

Type RM Length L Ch R = 1 ,15752   ,459.4,480.5,506.1
XS GIS Cut Line= 2
2332298.17266162731747.0072122352331980.62410558730601.907873789
#Sta/Elev= 30
       0 2075.18    43.4 2046.17   103.9 2014.59   346.4  1879.9   367.2 1871.69
   425.3 1869.55   437.7 1864.99   448.3 1865.61   464.6 1870.54   578.9 1872.67
   620.6  1871.1   670.2 1862.98   782.3 1862.97   798.9 1869.18   815.5 1883.96
   836.2 1896.89   852.8 1911.99   881.9 1928.88   894.4 1940.17   920.6 1942.95
     940 1960.48   985.7 1987.74  1047.9 2028.55  1072.8 2048.18  1081.1 2058.38
  1097.7 2073.14  1122.7 2091.42    1131 2104.01  1143.4  2116.3  1188.3 2148.88
#Mann= 3 ,-1,0
       0      .1       0   670.2    .045       0   782.3     .08       0
Bank Sta=670.2,782.3
XS Rating Curve= 0 ,0
Exp/Cntr(USF)=0,0
Exp/Cntr=0.3,0.1

Type RM Length L Ch R = 1 ,15272   ,677.4,706.8,755.1
XS GIS Cut Line= 2
2332458.55072023731740.5920898912332647.79682938730537.756650346
#Sta/Elev= 30
       0  2043.4    32.4 2031.64    60.1 2018.21   109.4 1992.58   169.5 1957.55
   250.5 1904.64   274.8 1882.56   290.9 1864.88   307.1 1860.38   335.5 1859.53
   364.8 1868.32   465.1 1868.28   473.2 1867.57   481.3 1861.87   489.4 1861.43
   529.9 1865.07   659.4 1868.41   687.8 1867.31   716.3 1861.78   825.4 1861.76
   829.5 1865.53   833.5 1872.64   865.9 1899.17   902.4 1918.28   930.7 1938.99
     955 1942.97   971.2 1957.52  1044.9 1999.73  1096.7 2035.02  1217.6 2105.23
#Mann= 6 ,-1,0
       0      .1       0     640    .025       0   716.3    .045       0
   825.4      .1       0     940     .08       0    1040      .1       0
Bank Sta=716.3,825.4
XS Rating Curve= 0 ,0
Exp/Cntr(USF)=0,0
Exp/Cntr=0.3,0.1

Type RM Length L Ch R = 1 ,14565   ,794,796.3,850.8
XS GIS Cut Line= 2
2332500.84906101731722.151396245  2333515.876531730969.943539015
#Sta/Elev= 30
       0 2022.95    48.8  1997.7   100.3 1979.34   123.2 1964.81   176.3 1920.56
   261.3 1875.43   280.4 1860.25   306.2 1856.26   331.9 1858.03   349.1  1865.4
   446.3 1864.05   539.1 1867.24   601.6 1865.75   626.5 1860.34   636.4 1861.21
   641.4 1865.09   651.4 1867.16   825.6 1867.36   860.5 1864.66   888.4 1859.34
   989.2  1859.3   994.9 1863.21  1003.9 1876.92  1023.9  1899.2  1039.7 1913.87
  1061.1 1930.15  1069.8 1933.06  1092.6 1933.27  1104.4 1941.63  1263.4 2007.35
#Mann= 6 ,-1,0
       0      .1       0     860    .025       0   888.4    .045       0
   989.2      .1       0    1020     .07       0    1140      .1       0
Bank Sta=888.4,989.2
XS Rating Curve= 0 ,0
Exp/Cntr(USF)=0,0
Exp/Cntr=0.3,0.1

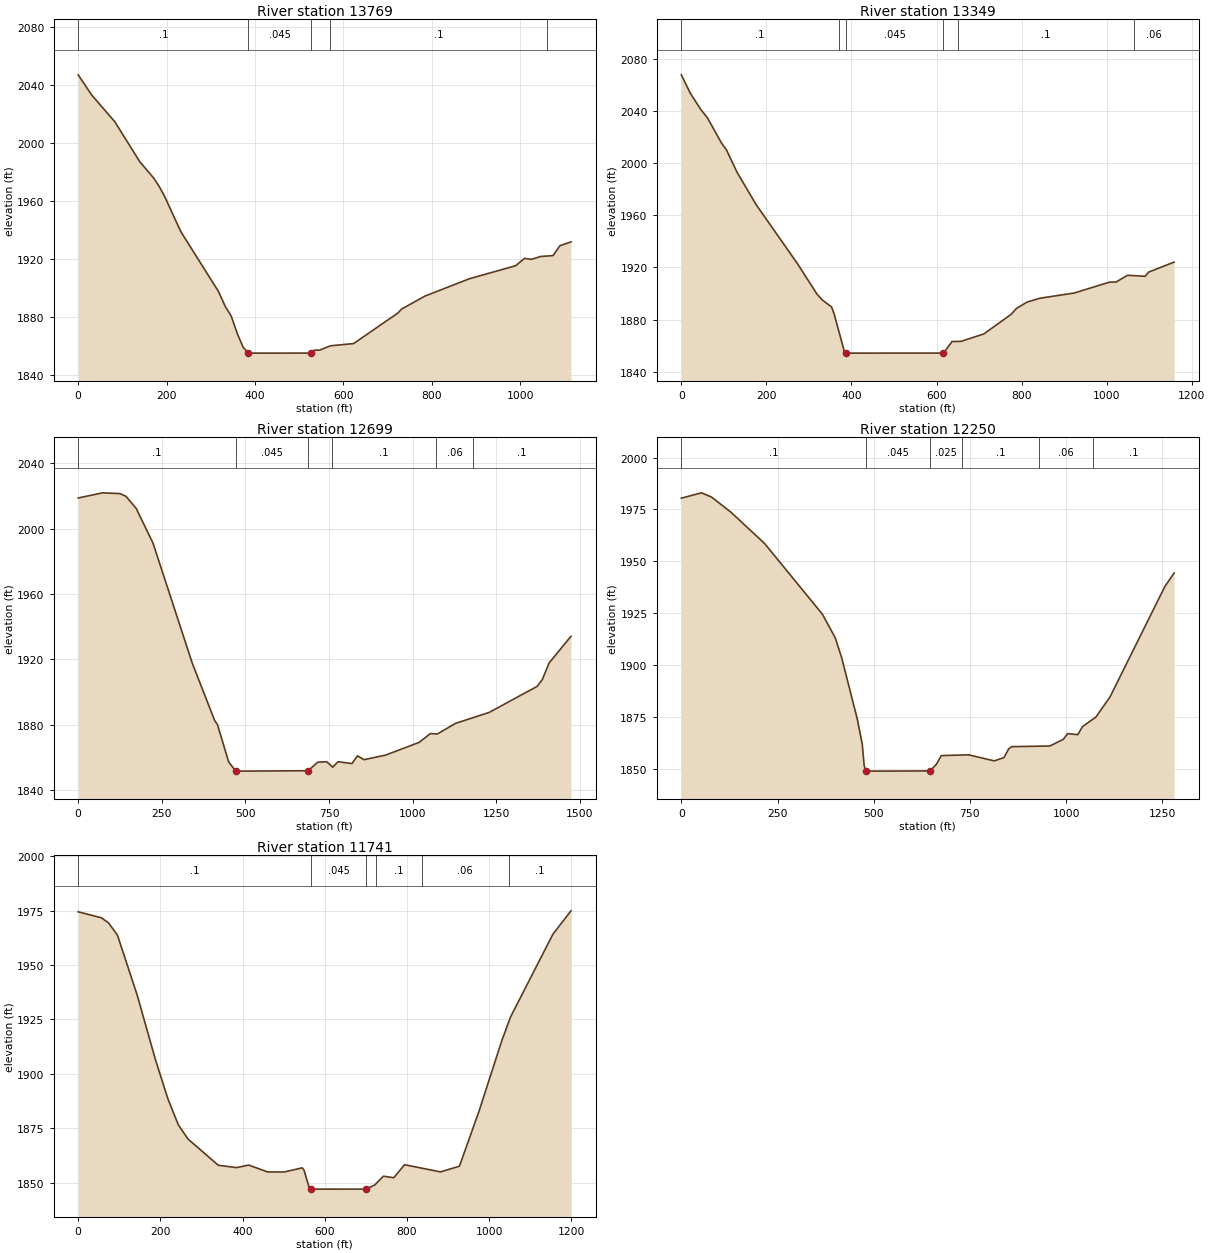
Type RM Length L Ch R = 1 ,13769   ,402.5,420,425.9
XS GIS Cut Line= 2
 2332461.7582814731766.2525792682333568.36688578731900.970148497
#Sta/Elev= 30
       0 2047.01    30.6 2033.07      83 2014.58   139.4 1987.02   171.7 1975.42
   183.8 1969.67   195.9 1962.88   232.1  1938.8   317.3 1897.49   332.9 1887.03
   346.1 1880.55   360.4 1868.02   373.2 1858.97   385.2 1854.91   526.3 1854.94
   534.3 1856.95   546.4 1856.99   570.6 1859.97     623  1861.5   723.2 1882.56
   731.8 1885.36   784.3 1894.27   884.8 1906.24   989.7 1915.25  1009.8 1920.32
    1025 1919.64  1046.1 1921.62  1074.3 1922.23  1089.6 1929.02  1114.8 1931.73
#Mann= 5 ,-1,0
       0      .1       0   385.2    .045       0   526.3    .025       0
     570      .1       0    1060     .06       0
Bank Sta=385.2,526.3
XS Rating Curve= 0 ,0
Exp/Cntr(USF)=0,0
Exp/Cntr=0.3,0.1

Type RM Length L Ch R = 1 ,13349   ,615.3,649.8,639
XS GIS Cut Line= 3
2332387.98437444732125.4994305452333058.36465942732260.216999774
2333504.21566234732096.631379996
#Sta/Elev= 30
       0  2067.8    20.6 2053.99    45.1 2041.47    61.4 2034.81      94 2015.68
   106.3  2010.1   130.8 1993.13   175.6 1968.31   273.6 1922.61   318.4 1899.77
   330.7 1895.19   353.2 1889.64   359.2 1884.39   383.7 1854.97   387.8 1854.19
   616.3 1854.25   636.7 1863.11   657.1 1863.18   711.3 1868.92   775.2  1883.9
     788 1888.51   813.5 1893.47   843.2 1896.33   924.3 1900.37  1006.1 1908.64
  1022.3 1908.78  1049.1 1913.95  1090.5 1913.17    1099 1916.44  1158.7 1924.04
#Mann= 6 ,-1,0
       0      .1       0     370    .025       0   387.8    .045       0
   616.3     .12       0     650      .1       0 1063.78     .06       0
Bank Sta=387.8,616.3
XS Rating Curve= 0 ,0
Exp/Cntr(USF)=0,0
Exp/Cntr=0.3,0.1

Type RM Length L Ch R = 1 ,12699   ,449.9,448.9,455.1
XS GIS Cut Line= 3
2332106.41731206732638.9884077322333234.78052388732988.333385845
2333417.61151069733216.070229066
#Sta/Elev= 30
       0 2018.66      73 2021.81   124.7 2021.35   142.7  2019.7   173.5 2012.27
   223.8 1991.03     341 1917.76     408 1882.65   416.4 1880.14   449.9 1857.36
  470.351851.928   479.6 1851.72   687.4 1851.97   716.2 1857.18     743 1857.45
   760.9 1854.15   776.9 1857.48   818.4 1856.34   835.1 1861.06   854.5 1858.71
   918.9 1861.51  1019.4 1869.29  1052.9 1874.68  1073.8 1874.42  1128.2 1880.92
  1228.5 1887.58  1372.1 1903.52  1387.5 1907.66    1408 1917.86  1473.3 1934.16
#Mann= 6 ,-1,0
       0      .1       0  470.35    .045       0   687.4    .025       0
     760      .1       0    1070     .06       0    1180      .1       0
Bank Sta=470.35,687.4
XS Rating Curve= 0 ,0
Exp/Cntr(USF)=0,0
Exp/Cntr=0.3,0.1

Type RM Length L Ch R = 1 ,12250   ,508.8,508.8,517.5
XS GIS Cut Line= 3
2331932.92981912733059.1789212792332920.43952902733353.995359467
2333084.02514879733543.241468622
#Sta/Elev= 30
       0 1980.42    52.4    1983    78.5 1980.96   128.6  1973.7   216.3 1958.58
   366.6 1924.45     400 1913.06   416.7 1903.46   457.5 1873.71   470.3 1861.62
   475.1 1851.54   479.3 1848.78     496 1848.75   646.3 1848.85     663 1852.07
   675.5 1856.24   746.4 1856.62   813.2 1853.69   838.3 1855.28   850.8  1859.5
   859.1 1860.56   957.8 1860.88   992.7 1864.09    1004 1866.84  1030.3 1866.35
  1042.4  1870.2  1077.1 1874.78  1114.1 1884.56  1256.5 1937.79  1280.7 1944.34
#Mann= 6 ,-1,0
       0      .1       0   479.3    .045       0   646.3    .025       0
     730      .1       0     930     .06       0 1070.58      .1       0
Bank Sta=479.3,646.3
XS Rating Curve= 0 ,0
Exp/Cntr(USF)=0,0
Exp/Cntr=0.3,0.1

Type RM Length L Ch R = 1 ,11741   ,508.9,517.1,521.5
XS GIS Cut Line= 4
2331801.00067995733305.8819418852331922.88800449733575.317080343
2332609.30609532733796.6388012192332727.98585869 733934.56393162
#Sta/Elev= 30
       0 1974.47    56.3 1971.72    73.9 1969.38    95.6 1963.71   143.6 1936.16
     188 1906.49   218.7  1888.3   243.7 1876.55     267 1870.09   340.9 1857.99
   385.3 1856.92   414.8 1858.08     461 1854.92   501.6 1854.92     545 1856.81
   549.3 1855.82   561.8 1847.86   566.1 1847.03   700.5 1847.04   721.6 1848.95
   742.6 1852.97   767.8 1852.26     794 1858.25   881.3 1854.95   927.5 1857.56
   975.2 1882.86  1030.7 1915.31    1052  1926.2  1154.9 1964.16  1198.9 1974.91
#Mann= 6 ,-1,0
       0      .1       0   566.1    .045       0   700.5    .025       0
  725.72      .1       0  835.72     .06       0 1046.94      .1       0
Bank Sta=566.1,700.5
XS Rating Curve= 0 ,0
Exp/Cntr(USF)=0,0
Exp/Cntr=0.3,0.1