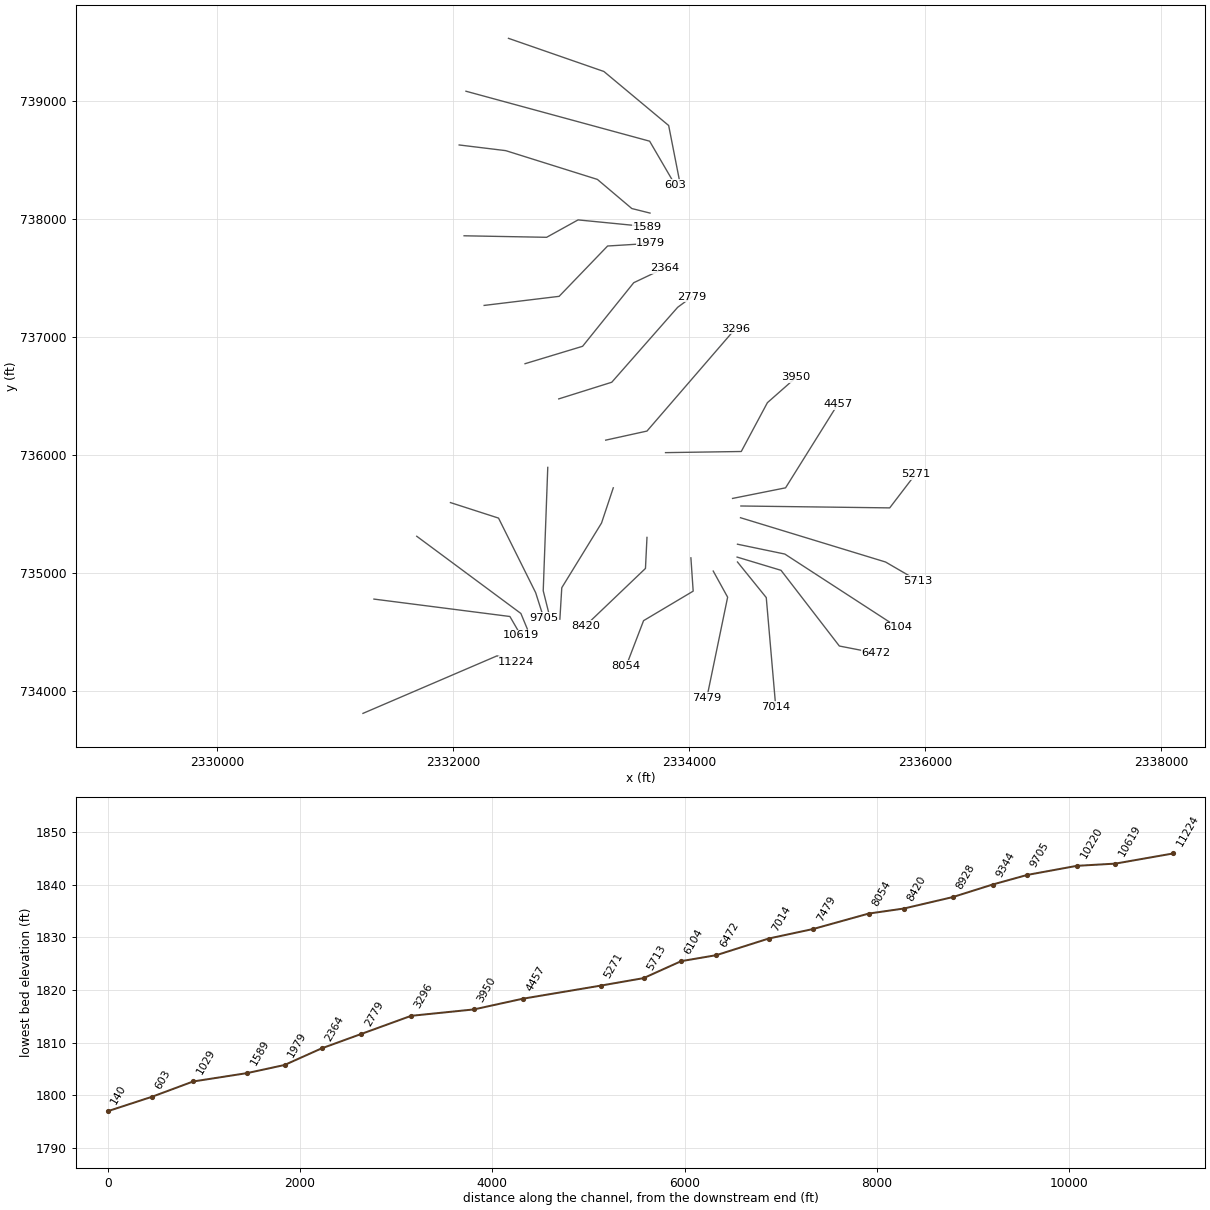
HEC-RAS study SHAVERSFK.prj: SHAVERSFK

--- SHAVERSFK.g01 (geometry) --- (continued)

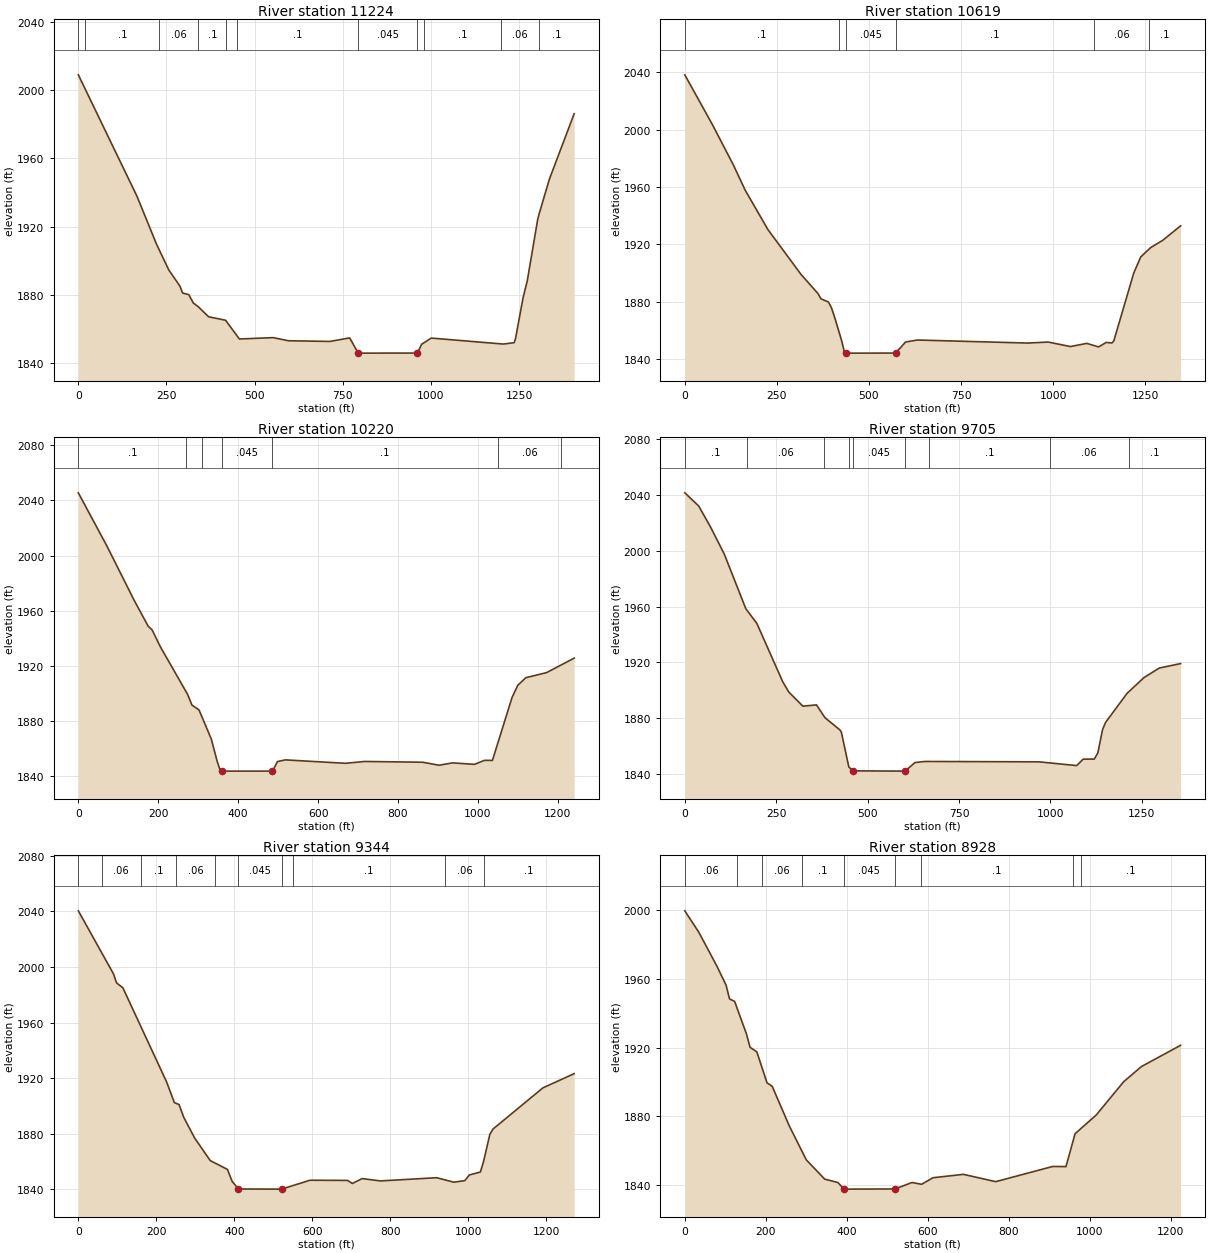
Type RM Length L Ch R = 1 ,11224   ,646.5,604.6,575.8
XS GIS Cut Line= 3
2331236.46991365733806.2614847362332371.94656858734293.810782898
2332535.53218836734245.697365316
#Sta/Elev= 30
       0 2008.87   166.5 1937.71   221.7 1909.75   256.5 1894.66   288.3 1885.13
   295.7 1881.13   313.1 1880.22   326.2 1875.27     340 1873.12   369.7  1867.2
   417.6 1865.19   456.8 1854.22   552.5 1855.01   595.9 1853.18   713.6 1852.79
   769.5 1854.84   793.8 1845.98     809 1845.94   961.7 1845.98   973.5 1851.09
  1000.9 1854.75  1205.5 1851.25    1236 1852.05  1240.1 1854.62    1261 1878.04
  1273.5 1888.56  1302.7 1924.14  1306.8 1927.42    1336 1947.82  1406.2 1986.09
#Mann= 11 ,-1,0
       0     .08       0      20      .1       0     230     .06       0
     340      .1       0     420     .06       0     450      .1       0
   793.8    .045       0   961.7    .025       0     980      .1       0
    1200     .06       0 1305.72      .1       0
Bank Sta=793.8,961.7
XS Rating Curve= 0 ,0
Exp/Cntr(USF)=0,0
Exp/Cntr=0.3,0.1

Type RM Length L Ch R = 1 ,10619   ,438.7,399.7,371.5
XS GIS Cut Line= 3
2331329.48918764734774.9449587162332481.00364843734627.397144798
2332574.02292243734467.019086192
#Sta/Elev= 30
       0  2038.2    75.3 2003.31   131.8 1975.37     164  1957.7   225.6 1930.27
   315.6 1898.92   361.6 1885.59   369.7 1881.88   389.8 1879.73   397.9 1875.88
     406 1869.77   425.8 1852.77   432.9 1845.29   438.2    1844   572.4 1844.03
   599.5 1851.77   631.8 1853.15   930.2 1851.03     987 1851.72  1047.2 1848.58
  1091.5  1850.8  1123.8 1848.33    1144 1851.45  1160.1  1851.1  1164.9 1852.56
    1219 1899.84    1238 1911.15  1265.2 1917.68  1297.6 1922.71  1346.3 1932.84
#Mann= 6 ,-1,0
       0      .1       0     420     .06       0   438.2    .045       0
   572.4      .1       0    1110     .06       0 1260.93      .1       0
Bank Sta=438.2,572.4
XS Rating Curve= 0 ,0
Exp/Cntr(USF)=0,0
Exp/Cntr=0.3,0.1

Type RM Length L Ch R = 1 ,10220   ,544.6,514.4,482.7
XS GIS Cut Line= 3
2331691.94360009735307.4001132872332574.02292243734653.057634175
2332628.55146235734521.547626118
#Sta/Elev= 30
       0 2045.54    70.9 2007.28   139.7 1967.57   174.6 1948.83   184.8 1945.99
   205.1 1933.89   273.4 1899.32   284.2 1891.53     302    1888   332.7  1866.9
   347.7 1850.42   353.9 1845.15   358.9 1843.58   483.4 1843.59   487.8  1844.6
   498.3 1850.54   518.3 1851.75   668.4 1849.25   716.6  1850.6   861.9 1850.03
   902.4 1847.86   936.6 1849.56   991.1  1848.5  1016.3  1851.4  1036.2 1851.36
  1085.4 1897.13  1099.8 1905.92  1119.8 1911.37  1171.8 1915.09  1240.7 1925.57
#Mann= 7 ,-1,0
       0      .1       0     270     .06       0     310    .025       0
   358.9    .045       0   483.4      .1       0    1050     .06       0
 1208.28      .1       0
Bank Sta=358.9,483.4
XS Rating Curve= 0 ,0
Exp/Cntr(USF)=0,0
Exp/Cntr=0.3,0.1

Type RM Length L Ch R = 1 ,9705    ,394.2,361.3,329.5
XS GIS Cut Line= 4
2331977.41654441735592.8730576062332384.77681327735461.363049549
2332699.11780814734829.4734986422332766.47659275734617.774461282
#Sta/Elev= 30
       0  2041.6    38.1 2032.12    70.2 2017.16     108 1997.64   166.8  1958.5
   197.2 1947.81   267.7 1906.08   284.5  1898.6   322.9 1888.49   360.2 1889.39
   383.2 1880.23   424.6 1871.36   428.3 1869.73   448.6 1844.81   460.6 1842.07
   600.8 1841.86   602.5 1841.86   629.3 1847.99   656.1  1848.8   968.8 1848.52
  1071.6 1845.83  1089.5 1850.46  1119.9 1850.51  1129.7 1855.04  1142.5 1871.64
  1150.8 1876.84  1209.7 1897.73  1255.9 1909.01  1297.8 1915.86    1356 1919.05
#Mann= 9 ,-1,0
       0      .1       0     170     .06       0     380      .1       0
  448.06    .025       0   460.6    .045       0   602.5    .025       0
  668.06      .1       0  998.06     .06       0 1213.82      .1       0
Bank Sta=460.6,602.5
XS Rating Curve= 0 ,0
Exp/Cntr(USF)=0,0
Exp/Cntr=0.3,0.1

Type RM Length L Ch R = 1 ,9344    ,450.7,415.8,390.1
XS GIS Cut Line= 3
2332801.75976565735891.1762466132332763.26903158734845.511304502
2332817.79757151734627.397144798
#Sta/Elev= 30
       0 2040.42    90.1 1995.04    98.1 1988.47   114.1 1985.07   226.2  1917.3
   246.2 1902.34   258.2 1900.94   270.5 1891.61   298.2 1876.84   338.2 1860.58
   382.3 1854.22   394.3 1845.67   410.3 1840.13   518.3 1840.03   522.4 1840.16
   594.1 1846.44   690.3  1846.3   702.5 1844.09   727.7 1847.62   774.5 1845.94
   918.8 1848.25   962.6 1845.03   990.7 1846.14  1002.7 1850.25  1030.7 1852.33
  1038.7 1859.61    1055 1879.47  1063.2  1883.3    1191 1912.93  1271.2 1923.19
#Mann= 10 ,-1,0
       0      .1       0      60     .06       0     160      .1       0
     250     .06       0     350    .025       0   410.3    .045       0
   522.4    .025       0     550      .1       0     940     .06       0
    1040      .1       0
Bank Sta=410.3,522.4
XS Rating Curve= 0 ,0
Exp/Cntr(USF)=0,0
Exp/Cntr=0.3,0.1

Type RM Length L Ch R = 1 ,8928    ,520.9,507.8,489.8
XS GIS Cut Line= 4
2333356.66784842735717.9679433192333257.23345209735419.664754312
2332920.43952901734871.1717938792332904.40172315734604.944216593
#Sta/Elev= 30
       0 1999.58    34.6 1987.14    80.1 1967.03     102 1956.31   110.5 1948.35
   123.1 1946.88   152.3 1927.95   161.1 1920.18   177.9 1917.52   203.2 1899.45
   215.9  1897.5     258 1874.48   300.2 1854.67   345.5 1843.48   378.4 1841.47
   392.6 1837.75   397.2 1837.64   519.2 1837.73   561.3  1841.5   584.9 1840.45
   613.1 1844.27   688.2 1846.24     768 1841.99   908.8 1850.83   941.6 1850.75
   964.1 1869.89  1016.2 1880.74  1084.3 1900.18  1128.4 1909.02  1224.8 1921.33
#Mann= 9 ,-1,0
       0     .06       0     130      .1       0     190     .06       0
     290      .1       0   392.6    .045       0   519.2    .025       0
  584.44      .1       0  958.08     .06       0  978.08      .1       0
Bank Sta=392.6,519.2
XS Rating Curve= 0 ,0
Exp/Cntr(USF)=0,0
Exp/Cntr=0.3,0.1

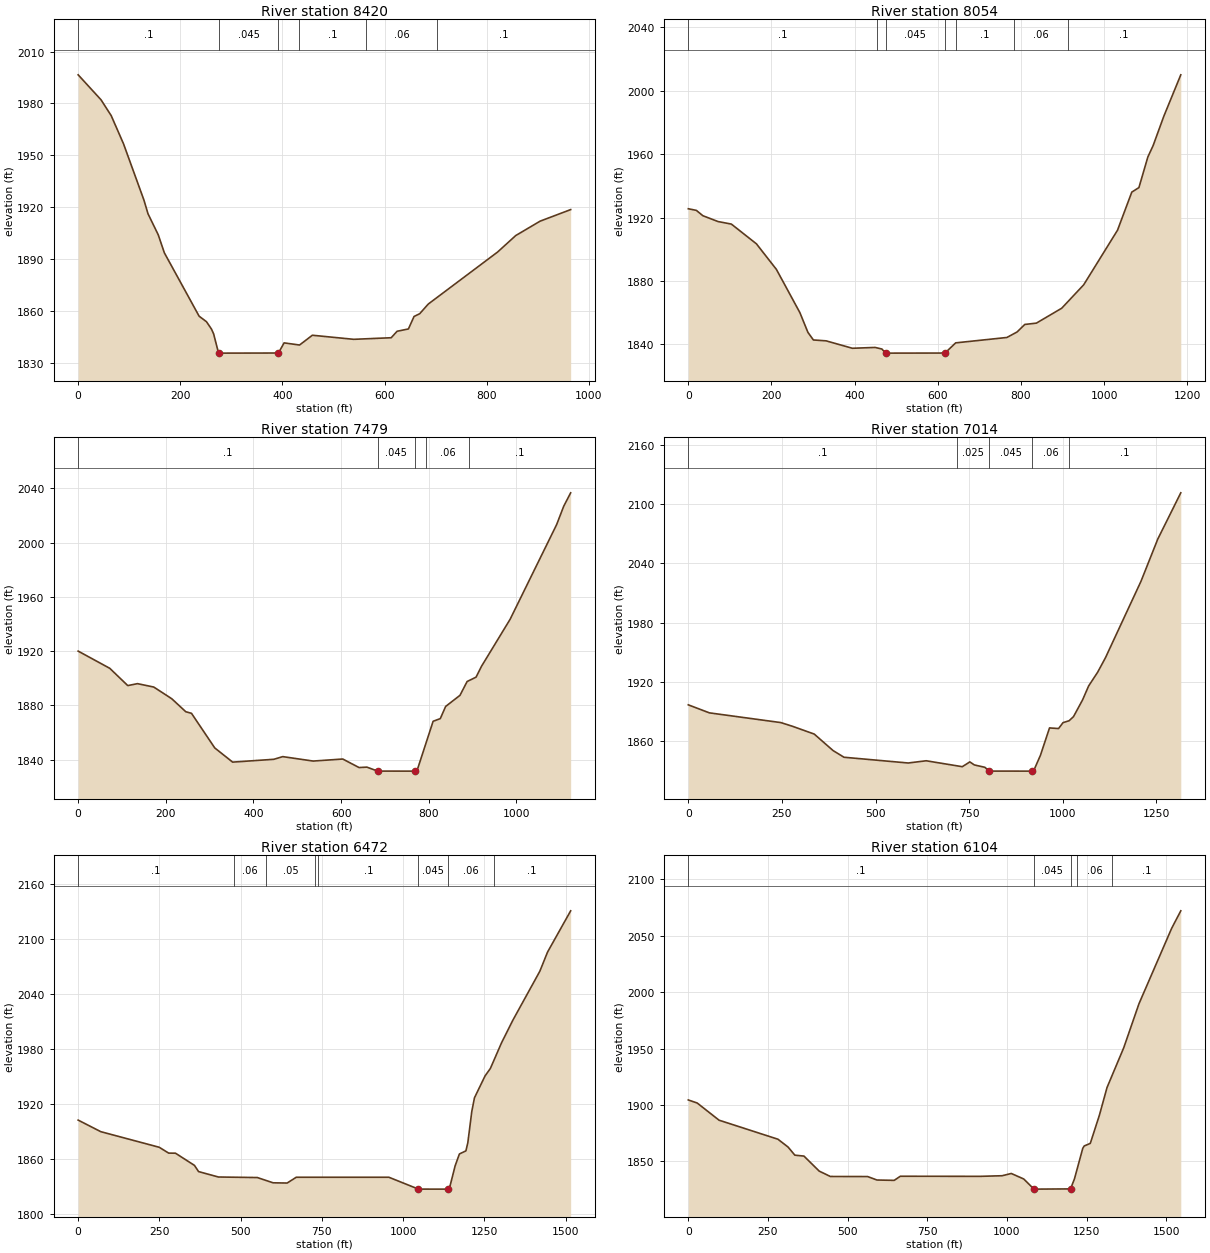
Type RM Length L Ch R = 1 ,8420    ,377.1,366.4,346.9
XS GIS Cut Line= 3
2333642.14079274735297.7774297712333629.31054805735034.757413657
2333122.51588286734550.415676667
#Sta/Elev= 30
       0 1996.54    44.7 1982.11    64.7 1972.92    88.7  1956.7   128.8 1924.03
   136.8  1916.1   156.8 1903.96   168.8 1893.51   236.9 1856.83   251.2 1853.67
   260.9 1849.47   265.3 1846.58   273.7 1836.89   276.71835.548   279.4 1835.47
   392.2 1835.53   403.2  1841.4   433.5 1840.16   458.6 1845.82   539.7 1843.46
     613 1844.38   624.5 1848.12   646.7 1849.46   657.7 1856.68   668.8 1858.29
   685.4 1863.83   821.4    1894   856.9 1903.53   904.6 1911.85   964.4 1918.54
#Mann= 6 ,-1,0
       0      .1       0   276.7    .045       0   392.2    .025       0
  433.33      .1       0  563.33     .06       0  703.33      .1       0
Bank Sta=276.7,392.2
XS Rating Curve= 0 ,0
Exp/Cntr(USF)=0,0
Exp/Cntr=0.3,0.1

Type RM Length L Ch R = 1 ,8054    ,542.2,575.1,628.2
XS GIS Cut Line= 4
2334014.21788871735124.5691264772334033.46325574 734842.30374333
2333613.27274219734592.1139719052333465.72492828 734207.20663125
#Sta/Elev= 30
       0 1925.54    19.4 1924.52      35 1921.16    71.6 1917.47   103.6 1915.87
   163.8 1903.44   211.9  1887.3   268.3 1860.07   287.6 1847.63   300.8 1842.81
   331.4 1842.25   394.6 1837.57   449.3  1838.1   465.6 1837.09   474.3 1834.51
   617.3 1834.56   642.9 1840.98   766.1 1844.38   790.6 1847.86   809.1 1852.59
     837 1853.43   897.9 1862.82   950.7 1877.58  1032.1 1912.03  1066.4 1936.04
  1083.5 1938.88    1105 1958.19  1117.8 1965.45  1143.3 1983.81  1184.2 2009.99
#Mann= 7 ,-1,0
       0      .1       0  452.92    .025       0   474.3    .045       0
   617.3    .025       0  642.92      .1       0  781.96     .06       0
  911.96      .1       0
Bank Sta=474.3,617.3
XS Rating Curve= 0 ,0
Exp/Cntr(USF)=0,0
Exp/Cntr=0.3,0.1

Type RM Length L Ch R = 1 ,7479    ,452.7,464.6,480.3
XS GIS Cut Line= 3
2334203.46399786735012.304485453 2334325.3513224734790.982764576
2334148.93545794733937.771492793
#Sta/Elev= 30
       0 1920.08    72.1  1907.4   113.2 1894.66   135.3 1896.09   172.5 1893.58
   213.6 1884.96   245.6 1875.38   258.6 1874.22   311.7  1848.7   352.5 1838.23
   446.5 1840.31   466.9 1842.28   536.3 1839.01   603.8 1840.51     641 1834.23
   658.9 1834.54   683.4 1831.61   769.2 1831.59   773.3 1831.94     810 1868.34
   826.4 1870.31   838.6 1879.28   871.3 1887.47   887.6 1897.66     908 1900.88
   920.3 1908.81   985.7 1943.53  1091.9 2013.36  1108.1 2026.94  1123.9 2036.78
#Mann= 5 ,-1,0
       0      .1       0   683.4    .045       0   769.2    .025       0
  792.67     .06       0  892.67      .1       0
Bank Sta=683.4,769.2
XS Rating Curve= 0 ,0
Exp/Cntr(USF)=0,0
Exp/Cntr=0.3,0.1

Type RM Length L Ch R = 1 ,7014    ,515.7,542.6,570.8
XS GIS Cut Line= 3
2334408.74791288735089.2859535842334652.52256196734787.775203404
2334732.71159126733863.997585834
#Sta/Elev= 30
       0 1896.88    56.3 1888.76   247.1 1878.91   277.9  1875.2   336.3 1867.28
   386.5 1850.62   415.7 1843.82   587.1    1838   635.3 1840.25   731.6 1834.26
   751.7 1839.11   763.7 1836.05   791.8 1833.65   803.9 1829.81   916.3 1829.77
   918.1 1829.88   924.3 1831.96   940.3 1845.83   964.5 1873.52   988.6 1872.86
  1000.6 1878.87  1016.7 1880.75  1028.5 1884.91  1052.8 1901.91  1068.9 1915.95
    1093 1929.89  1113.9 1944.59  1208.8 2022.01  1253.6 2064.72    1315  2111.5
#Mann= 5 ,-1,0
       0      .1       0  717.73    .025       0   803.9    .045       0
   918.1     .06       0 1017.73      .1       0
Bank Sta=803.9,918.1
XS Rating Curve= 0 ,0
Exp/Cntr(USF)=0,0
Exp/Cntr=0.3,0.1

Type RM Length L Ch R = 1 ,6472    ,353.2,368.1,384.8
XS GIS Cut Line= 4
2334405.54035171735130.9842488212334777.61744767735018.719607797
2335271.58186818734377.2073733732335582.71530187734316.263711103
#Sta/Elev= 30
       0 1901.97    69.6 1889.34   249.3 1872.32   278.5 1865.94   299.4 1865.85
   357.9 1852.51   370.4 1845.78   431.5 1839.85   551.3 1839.26   599.8 1833.52
     643 1833.26   671.1  1839.6     956 1839.59  1046.9 1826.64  1127.2 1826.62
  1137.8 1826.68  1144.5 1830.55  1159.9 1852.13    1173    1865    1193 1868.39
  1198.9  1877.3  1211.1  1911.4  1219.3 1926.29  1251.9 1950.19  1268.2  1958.3
  1302.5 1986.27  1337.5 2011.07  1420.4 2064.43  1444.2  2085.4  1515.3 2130.42
#Mann= 8 ,-1,0
       0      .1       0  478.64     .06       0  578.64     .05       0
  728.64     .12       0  738.64      .1       0  1046.9    .045       0
  1137.8     .06       0  1278.3      .1       0
Bank Sta=1046.9,1137.8
XS Rating Curve= 0 ,0
Exp/Cntr(USF)=0,0
Exp/Cntr=0.3,0.1

Type RM Length L Ch R = 1 ,6104    ,377.1,390.8,405.7
XS GIS Cut Line= 3
2334408.74791288735240.0413286732334809.69305939735156.644738198
2335762.33872751734537.585431979
#Sta/Elev= 30
       0 1904.45      28 1901.73    96.6 1886.52   281.3 1869.68   313.1 1862.75
   334.4 1855.56     363 1854.73   410.9 1841.42   445.9 1836.67   562.7 1836.61
   592.1 1833.54   646.2 1833.23   665.4 1836.87   916.9  1836.8   984.9 1837.33
  1013.6 1839.33  1052.8 1834.44  1084.6 1825.54  1085.1 1825.47  1199.6 1825.67
  1211.9 1834.55  1237.9 1861.54  1242.5  1863.7  1261.6 1865.98  1290.2 1890.97
  1314.1 1915.44  1366.6 1950.72  1414.3 1989.61    1517  2056.5  1545.6 2071.96
#Mann= 5 ,-1,0
       0      .1       0  1084.6    .045       0  1199.6      .1       0
 1219.53     .06       0 1329.53      .1       0
Bank Sta=1084.6,1199.6
XS Rating Curve= 0 ,0
Exp/Cntr(USF)=0,0
Exp/Cntr=0.3,0.1

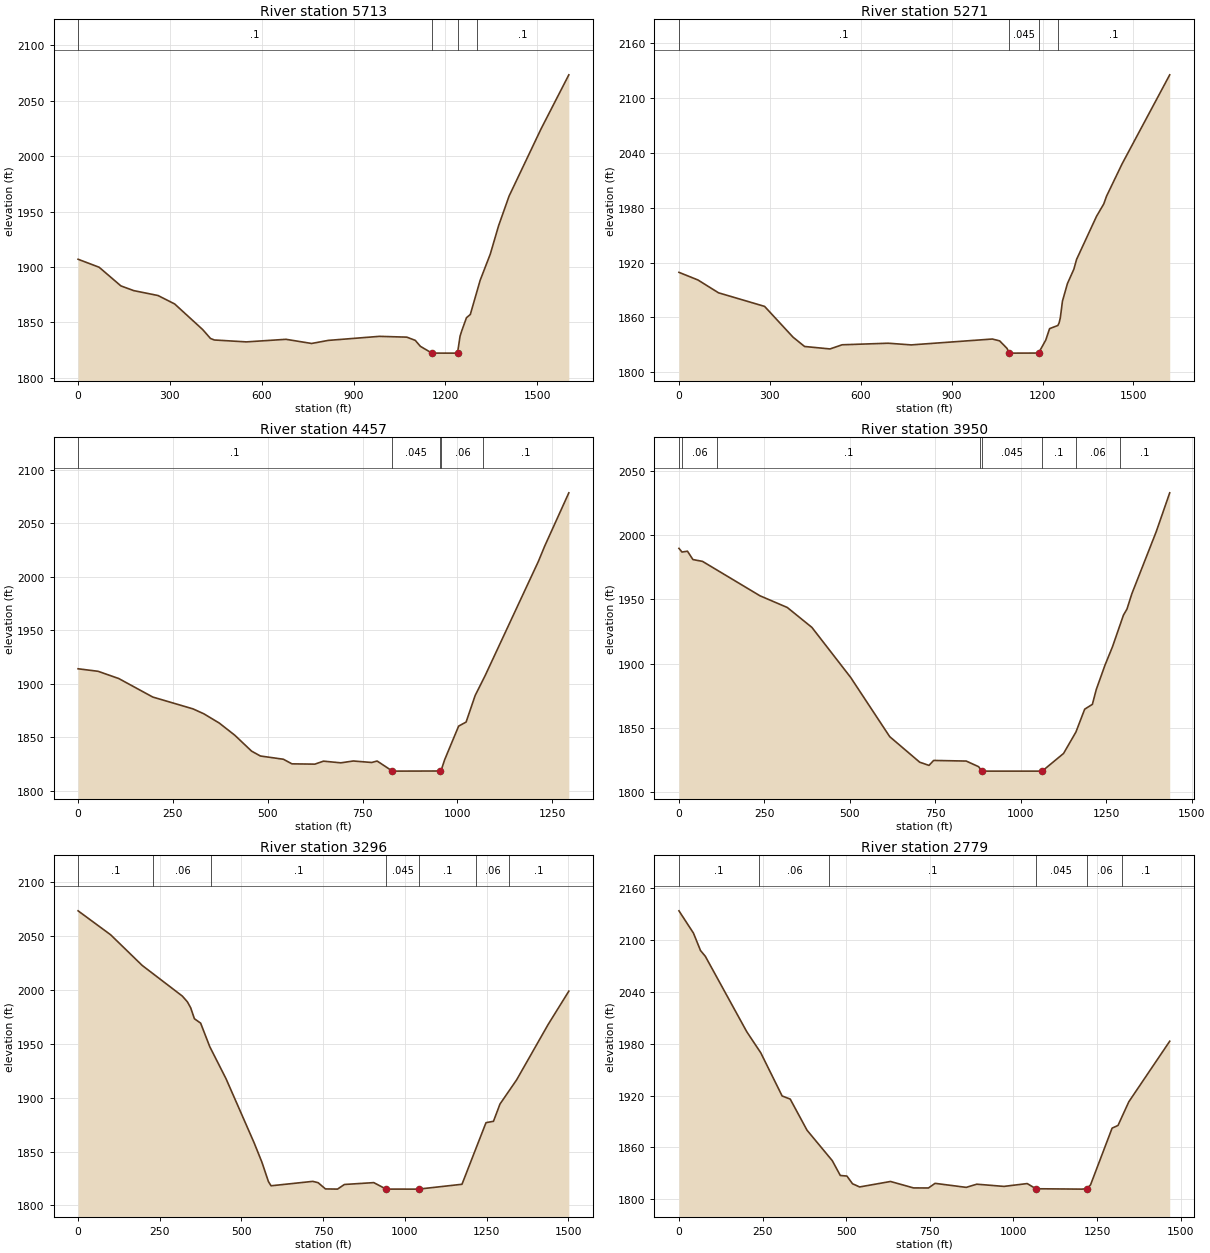
Type RM Length L Ch R = 1 ,5713    ,430.3,441.6,453.4
XS GIS Cut Line= 3
2334434.40840226735464.5706107212335662.90433118735089.285953584
2335938.75459198734928.907894978
#Sta/Elev= 30
       0 1906.98    68.8 1899.76   139.9 1882.93   181.7 1878.68   261.2 1874.24
   315.5 1866.65   407.1 1843.53   432.6  1835.5   445.2 1834.11   549.8 1832.39
   679.4 1834.72   763.1 1830.97   817.4 1833.73   984.7 1837.39  1074.2 1836.68
  1101.8 1833.77  1118.6 1828.36  1156.2 1822.27  1232.1 1822.25  1239.9 1822.33
  1248.2 1837.59  1253.6 1842.29  1269.1  1854.2  1281.7 1857.14  1313.8 1887.95
    1347 1911.68  1373.9 1937.08  1408.4 1964.02  1512.7 2024.57  1603.6 2073.43
#Mann= 4 ,-1,0
       0      .1       0  1156.2    .045       0  1239.9     .06       0
 1304.54      .1       0
Bank Sta=1156.2,1239.9
XS Rating Curve= 0 ,0
Exp/Cntr(USF)=0,0
Exp/Cntr=0.3,0.1

Type RM Length L Ch R = 1 ,5271    ,733.4,814.5,838.4
XS GIS Cut Line= 3
2334437.61596343735564.0050070572335698.18750407735547.967201197
2335916.30166377735833.440145515
#Sta/Elev= 30
       0 1909.31    62.6 1900.95   130.6 1886.89   282.6 1872.03   376.6  1838.3
   414.6 1828.12   498.6 1825.42   538.6 1829.97   690.6 1831.69   766.6 1829.85
  1034.6 1836.28  1058.6 1834.24  1082.6 1826.11  1090.6 1820.99  1094.6 1820.84
  1186.9 1820.91  1210.7 1835.13  1223.4 1847.66  1250.7 1851.12  1254.7 1853.84
  1258.7 1859.34  1265.8  1877.7  1282.3 1897.03  1303.5 1912.74  1312.5  1923.5
    1378 1970.46  1402.3 1984.28  1411.3 1992.66  1462.7 2028.11  1619.9 2125.58
#Mann= 4 ,-1,0
       0      .1       0  1090.6    .045       0  1186.9     .06       0
    1250      .1       0
Bank Sta=1090.6,1186.9
XS Rating Curve= 0 ,0
Exp/Cntr(USF)=0,0
Exp/Cntr=0.3,0.1

Type RM Length L Ch R = 1 ,4457    ,501.9,507.1,510.1
XS GIS Cut Line= 3
2334367.04961764  735628.15623052334816.10818174735717.967943319
2335258.75162349736426.838962357
#Sta/Elev= 30
       0 1913.95    52.8 1911.59   107.2 1904.84   196.9 1887.55     303 1876.48
   331.6 1871.88   372.4 1863.19   413.2 1851.87   457.3 1837.04   480.6 1832.48
   541.2 1829.44   563.8 1825.14   624.2 1824.87   646.9 1827.65   692.6  1826.1
   725.8 1827.81   773.9 1826.41   788.4 1827.77  828.34 1818.42     829 1818.34
   953.8 1818.46   956.9 1818.83   966.3 1828.94  1003.2 1860.39  1022.9 1864.18
  1046.7 1888.93  1072.9 1907.44  1213.3 2014.16  1230.4 2028.82  1293.7 2078.32
#Mann= 5 ,-1,0
       0      .1       0  828.34    .045       0   953.8      .1       0
  957.95     .06       0 1067.95      .1       0
Bank Sta=828.34,953.8
XS Rating Curve= 0 ,0
Exp/Cntr(USF)=0,0
Exp/Cntr=0.3,0.1

Type RM Length L Ch R = 1 ,3950    ,668.6,653.9,638.6
XS GIS Cut Line= 4
2333799.31129018736016.271132326 2334440.8235246736025.893815842
2334662.14524548736439.6692070462334905.91989456736654.575805578
#Sta/Elev= 30
       0 1989.58     8.9 1986.73    24.9 1987.38    40.9 1980.89    68.9 1979.47
   236.9 1952.72   316.9 1943.61   388.9 1928.12   502.3 1889.21   616.6 1843.12
   704.3 1823.26   731.5 1820.77   745.1 1824.62   840.4 1824.14   876.7 1819.77
   886.2 1816.34   890.3 1816.31  1062.6 1816.31  1125.2 1830.06  1161.5 1846.77
    1187  1864.5  1209.5 1868.26    1221 1879.86  1246.5  1898.8  1268.2 1912.94
  1300.4 1937.66  1310.8 1942.39  1324.8 1954.13  1396.2 2002.48  1435.8 2032.79
#Mann= 8 ,-1,0
       0      .1       0      10     .06       0     110      .1       0
  881.58    .025       0   886.2    .045       0  1062.6      .1       0
 1160.83     .06       0 1290.83      .1       0
Bank Sta=886.2,1062.6
XS Rating Curve= 0 ,0
Exp/Cntr(USF)=0,0
Exp/Cntr=0.3,0.1

Type RM Length L Ch R = 1 ,3296    ,513.9,516.4,528.9
XS GIS Cut Line= 3
2333292.51662498736122.1206510062333642.14079274736199.102119137
2334389.50254585737065.143635609
#Sta/Elev= 30
       0 2073.41    99.6 2051.19   196.2 2022.74   319.1 1994.27   334.6 1988.91
   344.7 1983.35     356 1973.26   375.1 1969.15     403 1947.32   452.9 1917.51
   538.7 1858.13   562.3 1840.35   582.6 1822.07   590.6 1818.19   718.3 1822.29
   734.6 1821.07     757 1815.28     794 1815.12   815.1  1819.4   904.9 1821.13
   942.7 1815.12  1042.3 1815.09  1044.4 1815.18  1174.9  1819.6  1248.4 1876.78
  1271.3 1878.05  1291.1 1894.02  1342.2 1916.57  1438.6 1967.93  1501.9 1998.84
#Mann= 7 ,-1,0
       0      .1       0     230     .06       0     408      .1       0
   942.7    .045       0  1044.4      .1       0    1218     .06       0
    1318      .1       0
Bank Sta=942.7,1044.4
XS Rating Curve= 0 ,0
Exp/Cntr(USF)=0,0
Exp/Cntr=0.3,0.1

Type RM Length L Ch R = 1 ,2779    ,412.5,415.6,418.3
XS GIS Cut Line= 4
2332894.77903964736471.7448187672333343.83760373 736612.87751034
2333901.95324768 737247.974622422334023.84057222737337.786335239
#Sta/Elev= 30
       0 2133.94    43.4 2108.08    64.4    2088    78.8  2081.3   202.7 1993.97
   244.7 1969.48   308.5 1919.56   332.7 1915.91     383 1879.87   458.5 1844.62
   482.5 1827.45   502.3  1826.8     519 1817.87   540.3 1814.19   632.7 1820.52
   701.5 1813.05   746.1    1813   765.9 1818.35     859  1813.7   890.6 1817.37
   971.7 1814.82  1041.4 1818.09  1067.5  1812.1  1205.3 1811.66  1219.4 1812.13
  1230.8 1816.59  1295.3  1882.3    1313 1885.43  1345.2 1912.75  1467.6 1982.95
#Mann= 6 ,-1,0
       0      .1       0     240     .06       0     450      .1       0
  1067.5    .045       0  1219.4     .06       0  1326.2      .1       0
Bank Sta=1067.5,1219.4
XS Rating Curve= 0 ,0
Exp/Cntr(USF)=0,0
Exp/Cntr=0.3,0.1

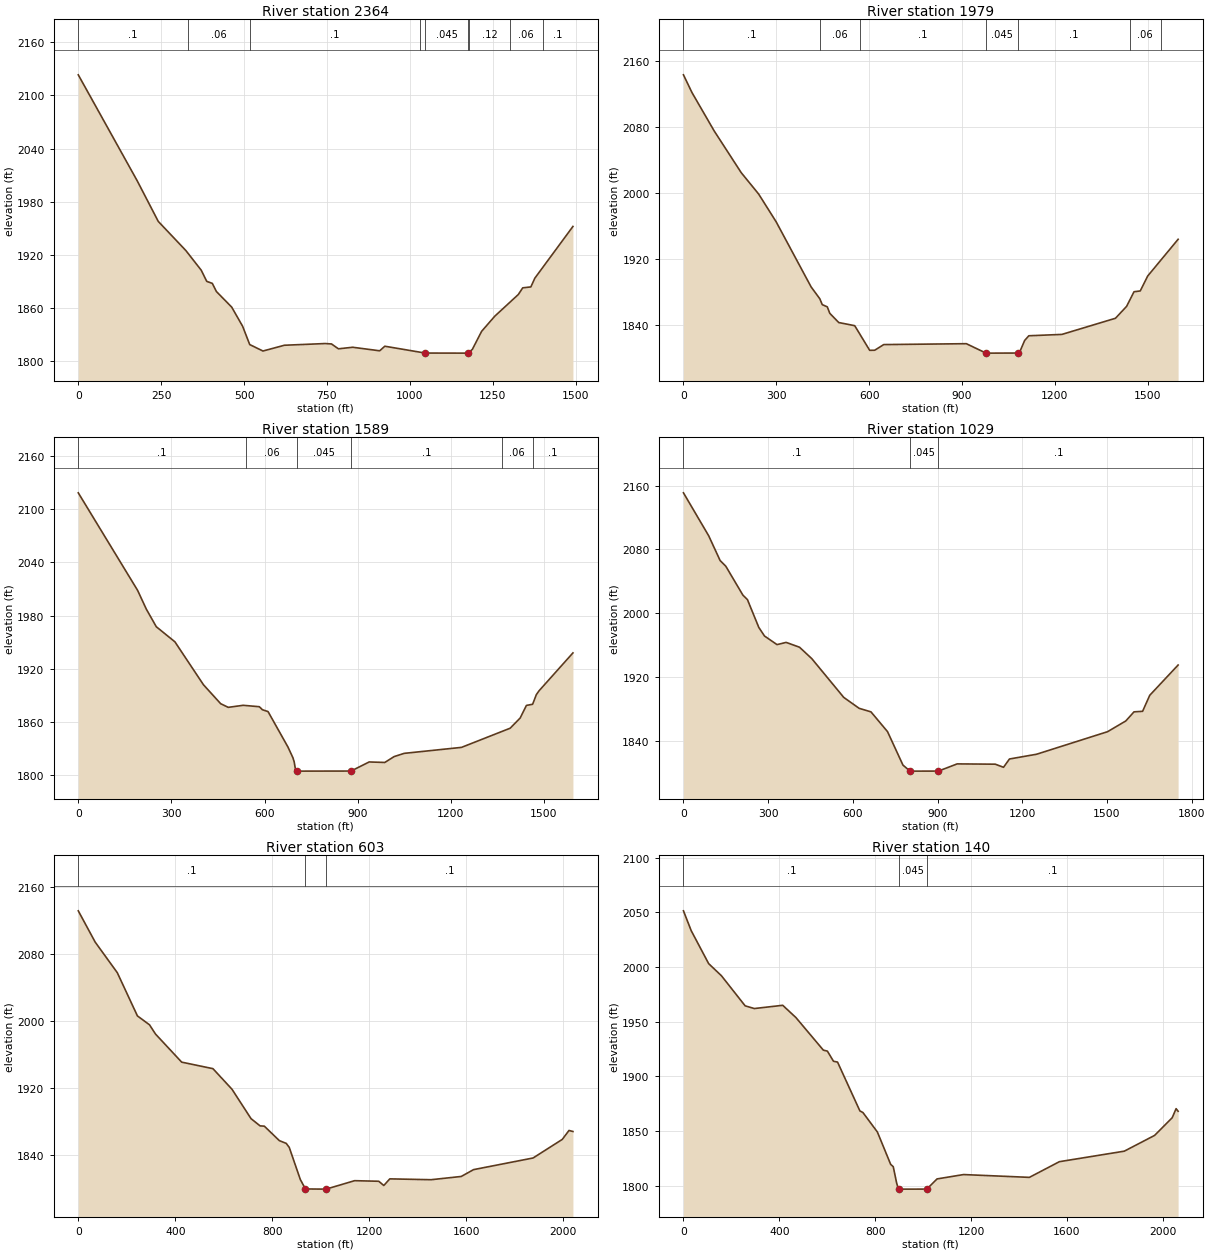
Type RM Length L Ch R = 1 ,2364    ,390.2,384.8,381.5
XS GIS Cut Line= 4
2332609.30609532736770.0480077742333096.85539348736917.595821691
2333529.87615172737456.4660986072333792.89616783 737581.56098432
#Sta/Elev= 30
       0 2123.31   178.1 2003.36   241.2 1957.74   324.8 1924.66   370.8 1902.59
   387.5 1889.96   404.2 1887.72   416.7 1878.47   462.7  1860.9   495.7 1839.24
   517.1 1818.58     557 1811.28   621.7  1817.8   744.6 1819.72   763.7 1819.27
   784.6 1813.77   827.6 1815.53   909.1 1811.53   924.5  1816.7  1046.3 1808.97
  1168.7  1808.9  1175.9 1808.99  1188.6 1813.18  1216.5 1833.53  1256.4  1850.7
  1327.2 1875.13  1340.5 1882.66    1365  1883.7    1377 1893.56  1491.9 1952.02
#Mann= 9 ,-1,0
       0      .1       0     330     .06       0  519.39      .1       0
 1029.39     .12       0  1046.3    .045       0  1175.9    .025       0
 1179.39     .12       0 1300.68     .06       0 1400.68      .1       0
Bank Sta=1046.3,1175.9
XS Rating Curve= 0 ,0
Exp/Cntr(USF)=0,0
Exp/Cntr=0.3,0.1

Type RM Length L Ch R = 1 ,1979    ,426.1,389.7,371.5
XS GIS Cut Line= 4
2332262.88948873 737264.012428282332897.98660081737340.993896411
2333308.55443084737767.5995323032333674.21640446737790.052460508
#Sta/Elev= 30
       0 2143.69    27.6 2122.11    99.2 2075.61   186.6 2024.92   243.1 1998.86
   299.5 1965.21   412.3 1886.26   440.5 1871.77   448.5 1864.61   464.7 1861.97
   472.7 1854.14   501.7  1842.9   553.3 1839.08   601.7 1809.16   617.8 1809.25
   647.1 1816.12     914 1817.21  977.271805.822   994.8 1805.75  1081.3 1805.86
  1087.1 1807.73  1102.5  1821.2  1115.9 1826.83  1222.9 1828.49  1395.8 1848.09
  1431.8 1862.55  1455.7 1880.29  1475.9 1881.24  1499.9 1899.38  1598.2 1943.98
#Mann= 7 ,-1,0
       0      .1       0     440     .06       0     570      .1       0
  977.27    .045       0  1081.3      .1       0 1441.83     .06       0
 1541.83      .1       0
Bank Sta=977.27,1081.3
XS Rating Curve= 0 ,0
Exp/Cntr(USF)=0,0
Exp/Cntr=0.3,0.1

Type RM Length L Ch R = 1 ,1589    ,632.6,560.6,512.9
XS GIS Cut Line= 4
2332092.88874661 737854.203683952332792.13708213737841.373439262
2333058.36465942737988.9212531792333645.34835391737931.185152081
#Sta/Elev= 30
       0  2118.6   191.3 2008.31   219.3 1987.18   251.3 1967.35   311.3  1950.3
   403.4 1901.75   458.8 1880.37   483.2 1876.26   531.4 1878.57   583.4 1876.96
   593.2 1873.57   611.4 1871.47   675.4 1831.52   691.4 1819.45   695.4 1814.96
   699.4 1806.79     704 1804.21   878.7  1804.3   937.2 1814.58   987.5    1814
  1017.6 1820.63  1049.8 1824.28  1234.7 1831.04  1391.4 1852.69  1423.6 1864.21
  1443.7 1878.43  1463.8 1879.76  1475.8 1890.69  1484.5 1894.98  1593.6 1937.76
#Mann= 6 ,-1,0
       0      .1       0     540     .06       0     704    .045       0
   878.7      .1       0 1363.75     .06       0 1463.75      .1       0
Bank Sta=704,878.7
XS Rating Curve= 0 ,0
Exp/Cntr(USF)=0,0
Exp/Cntr=0.3,0.1

Type RM Length L Ch R = 1 ,1029    ,421.6,425.8,423.8
XS GIS Cut Line= 5
2332051.19045137738624.0183652592332445.72047554738575.904947677
2333221.95027919738332.1302985962333513.83834586738085.148088343
2333667.80128212738046.657354277
#Sta/Elev= 30
       0 2150.91    89.6 2097.03   129.9 2066.15   150.1 2059.01   210.5  2022.9
   226.7 2017.23   266.9 1982.48     287 1971.75   331.4 1960.95   363.7 1963.73
   411.2 1957.67   454.5 1943.42   567.7 1894.91   622.2 1881.24   664.2 1876.78
   722.9 1852.02   777.4 1810.21   802.5 1802.62   903.1 1802.66   969.5 1811.67
  1104.4 1811.31  1133.7 1807.42  1154.7  1817.8  1250.7 1823.75  1502.2 1851.97
  1566.7 1865.39  1595.8  1876.8  1626.3  1877.5  1651.6 1897.52  1752.1  1935.4
#Mann= 3 ,-1,0
       0      .1       0   802.5    .045       0   903.1      .1       0
Bank Sta=802.5,903.1
XS Rating Curve= 0 ,0
Exp/Cntr(USF)=0,0
Exp/Cntr=0.3,0.1

Type RM Length L Ch R = 1 ,603     ,487.5,463.3,451.8
XS GIS Cut Line= 3
2332108.92655247  739079.49205172333664.59372095 738656.09397698
2333879.50031948738287.224442186
#Sta/Elev= 30
       0 2131.93    69.7 2094.61   160.9 2058.09   243.8 2006.51   293.6 1995.89
   318.4 1984.86   426.2 1951.32   555.2 1943.52   633.6 1918.99   712.2 1883.87
   749.6 1875.22     767 1874.88     829 1857.61   857.3 1854.32   869.8 1849.51
   915.4  1811.2   936.5 1799.94    1018 1799.73  1023.2 1799.87  1139.2 1809.81
  1238.7 1809.12  1259.5 1804.07  1284.3 1811.98  1454.3 1810.97  1578.7 1814.84
  1629.5    1823  1874.9 1836.89  1995.2 1859.06    2023 1869.77  2039.2 1868.52
#Mann= 3 ,-1,0
       0      .1       0   936.5    .045       0  1023.2      .1       0
Bank Sta=936.5,1023.2
XS Rating Curve= 0 ,0
Exp/Cntr(USF)=0,0
Exp/Cntr=0.3,0.1

Type RM Length L Ch R = 1 ,140     ,,,
XS GIS Cut Line= 4
2332469.00418148739527.7853309622333277.06693957739246.907901678
2333825.85822448738788.8616323842333920.92443131738304.888215771
#Sta/Elev= 30
       0 2051.32    32.3 2033.19   105.1 2003.07   158.5 1991.97   257.4 1964.48
   295.6 1962.01   414.1 1964.98   469.2 1953.76   583.5 1924.01   600.5  1923.1
   625.9 1913.82   642.8 1913.09     736 1868.46   748.7 1866.96     809 1849.18
   864.4 1819.61   875.2 1817.47   889.4 1802.48   895.8 1797.64   901.2 1796.97
  1015.1 1796.99  1057.9 1806.29  1168.5 1810.28  1443.1 1807.72  1568.1 1822.04
    1839 1831.66  1965.4 1846.06  2038.8 1862.21  2055.1  1870.5  2063.5 1868.15
#Mann= 3 ,-1,0
       0      .1       0   901.2    .045       0  1015.1      .1       0
Bank Sta=901.2,1015.1
XS Rating Curve= 0 ,0
Exp/Cntr(USF)=0,0
Exp/Cntr=0.3,0.1
LCMann Table=0

Chan Stop Cuts=-1
Use User Specified Reach Order=0
Composite Channel Slope=5